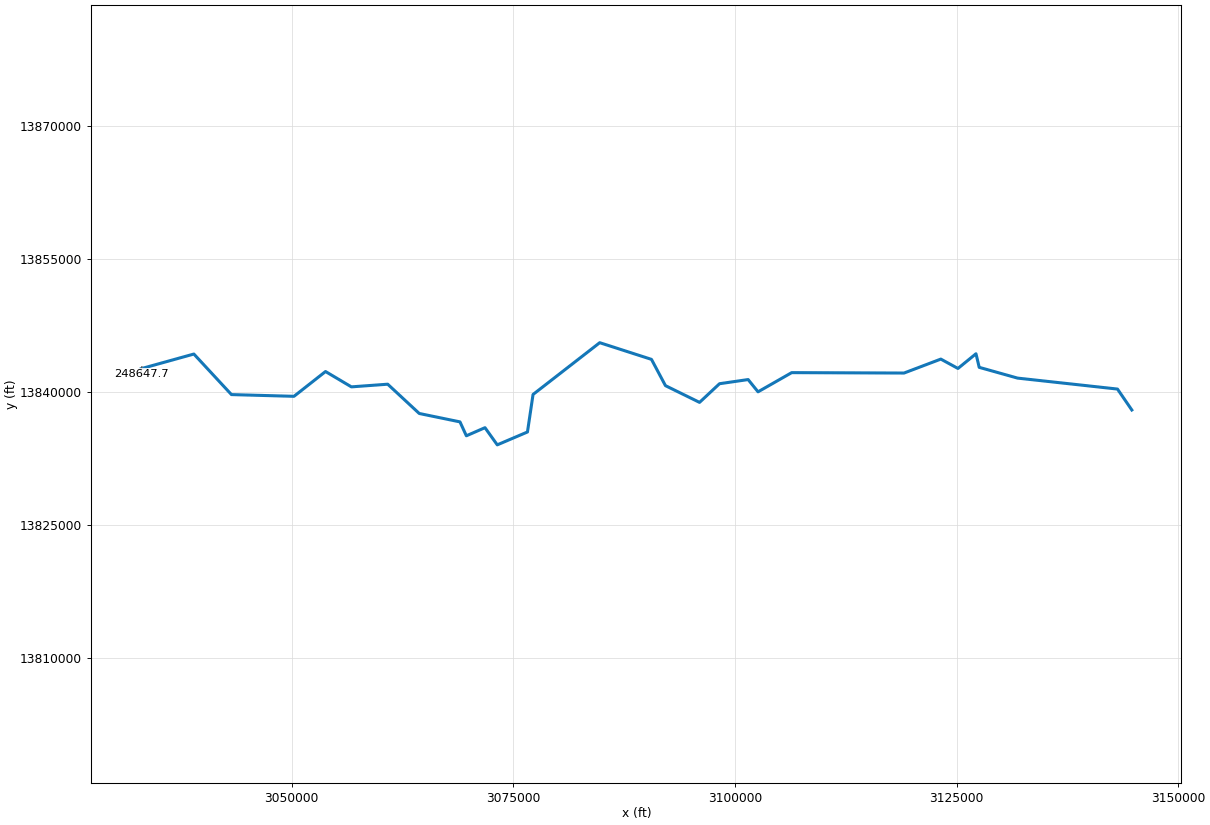
--- W100-00-00.prj (project) ---

Proj Title=W100-00-00
Current Plan=p01
Default Exp/Contr=.3,.1
English Units
Geom File=g01
Flow File=f01
Flow File=f02
Plan File=p01
Plan File=p02
Y Axis Title=Elevation
X Axis Title(PF)=Main Channel Distance
X Axis Title(XS)=Station
BEGIN DESCRIPTION:
Buffalo Bayou Watershed
Buffalo Bayou
HCFCD Unit W100-00-00
Flood Hazard Model
10, 2, 1, 0.2% Event
Filename W100-00-00.prj
Prepared by:  Watershed Concepts  Date:
Reviewed by:                      Date:
STATUS FINAL
Update4:
The effective FEMA hydraulic model for unit number W100-00-00 has been updated by FEMA LOMR 20-06-3136P with an effective date of 01/14/2021.
END DESCRIPTION:
DSS Export Rating Curves= 0
DSS Export Rating Curve Sorted= 0
DSS Export Volume Flow Curves= 0
DXF Filename=..\..\..\..\..\5-02 Calculations\Drainage\LOMR\08-103 Tolerance Bridge\CD\Prop Pedestrian Bridge over Buffalo Bayou\Models\Hydraulics\PedestrianBridge.
DXF OffsetX= 0
DXF OffsetY= 0
DXF ScaleX= 1
DXF ScaleY= 10

--- W100-00-00.p01 (plan) ---

Plan Title=Effective Multi-Profile 2021
Version=Version 3.0.1  May 2012
Short Identifier=Post_ProjMP
Geom File=g01
Flow File=f01
Subcritical Flow
K Sum by GR= 0
Std Step Tol= 0.01
Critical Tol= 0.01
Num of Std Step Trials= 20
Max Error Tol= 0.3
Flow Tol Ratio= 0.001
Split Flow NTrial= 30
Split Flow Tol= 0.02
Split Flow Ratio= 0.02
Log Output Level= 0
Friction Slope Method= 1
Unsteady Friction Slope Method= 2
Parabolic Critical Depth
Global Vel Dist= 0 , 0 , 0
Global Log Level= 0
CheckData=True
Encroach Param=-1 ,0,0, 0
BEGIN DESCRIPTION:
FEMA Effective Multi-Profile 2007 + LOMR 12-06-1071P + LOMR 14-06-2581P + LOMR 20-06-3136P
END DESCRIPTION:
Computation Interval=1HOUR
Output Interval=1HOUR
Run HTab= 0
Run UNet= 0
Run PostProcess= 0
UNET Theta= 1
UNET ZTol= 0.02
UNET ZSATol= 0.05
UNET MxIter= 20
UNET MaxInSteps= 0
UNET DtIC= 0
UNET DtMin= 0
UNET MaxCRTS= 20
UNET WFStab= 2
UNET SFStab= 1
UNET WFX= 1
UNET SFX= 1
UNET Convert EG Bridges= 0
UNET Use Existing IB Tables=-1
Instantaneous Interval=1HOUR
Write IC File= 0
IC Time=0
Write Velocity= 0
Write Detailed= 0

--- W100-00-00.p02 (plan) ---

Plan Title=Effective FW 2021
Version=Version 3.0.1  May 2012
Short Identifier=Post-Proj FW
Geom File=g01
Flow File=f02
Subcritical Flow
K Sum by GR= 0
Std Step Tol= 0.01
Critical Tol= 0.01
Num of Std Step Trials= 20
Max Error Tol= 0.3
Flow Tol Ratio= 0.001
Split Flow NTrial= 30
Split Flow Tol= 0.02
Split Flow Ratio= 0.02
Log Output Level= 0
Friction Slope Method= 1
Unsteady Friction Slope Method= 2
Parabolic Critical Depth
Global Vel Dist= 0 , 0 , 0
Global Log Level= 0
CheckData=True
Encroach Param=-1 ,0,0, 2
Encroach River=W100-00-00
Encroach Reach=Reach - 1
Encroach Node=248647.7
       1  4923.3  5071.9
Encroach Node=248547.8
       1  4923.3  5071.9
Encroach Node=248481.1
       1  4923.3  5071.9
Encroach Node=248414.4
       1  4923.3  5071.9
Encroach Node=247502.0
       1  4915.1  5075.5
Encroach Node=246449.8
       1  4922.3  5095.7
Encroach Node=245413.7
       1  4894.2  5070.5
Encroach Node=244345.5
       1 4934.91  5116.1
Encroach Node=243452.9
       1  4897.5  5113.5
Encroach Node=242655.3
       1  4915.9  5074.6
Encroach Node=241917.5
       1    4855  5076.8
Encroach Node=241646.1
       1    4930    5090
Encroach Node=241632.7
       1    4930    5090
Encroach Node=241619.3
       1    4930    5090
Encroach Node=241079.0
       1  4881.6  5132.6
Encroach Node=240579.0
       1    4863    5115
Encroach Node=240376.3
       1    4863  5110.8
Encroach Node=240315.3
       1    4863  5110.8
Encroach Node=240254.3
       1    4863  5110.8
Encroach Node=239993.6
       1    4895    5100
Encroach Node=239036.8
       1    4925    5110
Encroach Node=238060.4
       1  4902.5    5105
Encroach Node=237276.3
       1    4880    5080
Encroach Node=236611.0
       1    4870    5080
Encroach Node=235706.9
       1    4890  5088.1
Encroach Node=234807.9
       1    4885    5195
Encroach Node=233698.4
       1  4891.8    5330
Encroach Node=233029.3
       1 4900.17 5097.77
Encroach Node=232816.9
       1 4900.17 5097.77
Encroach Node=232805.9
       1 4900.17 5097.77
Encroach Node=232794.9
       1 4900.17 5097.77
Encroach Node=232790.8
       1 4897.99 5104.99
Encroach Node=232732.9
       1 4897.99 5104.99
Encroach Node=232681.7
       1 4897.99 5104.99
Encroach Node=232669.7
       1 4897.79 5104.99
Encroach Node=232657.7
       1 4897.79 5104.99
Encroach Node=232645.3
       1 4897.79 5104.99
Encroach Node=232632.3
       1 4897.79 5104.99
Encroach Node=231798.0
       1  4862.7  5081.4
Encroach Node=230908.0
       1  4886.4    5405
Encroach Node=229882.5
       1    4475    5115
Encroach Node=228917.1
       1    4530    5280
Encroach Node=228060.7
       1    4700    5200
Encroach Node=227524.1
       1    4870    5120
Encroach Node=227144.7
       1    4800    5105
Encroach Node=227088.2
       1    4800    5105
Encroach Node=227031.7
       1    4800    5105
Encroach Node=225979.2
       1    4800  5091.1
Encroach Node=224981.6
       1    4895    5275
Encroach Node=224198.0
       1    4830  5126.5
Encroach Node=223061.1
       1    4850  5126.5
Encroach Node=222172.8
       1    4840  5108.8
Encroach Node=221721.3
       1    4900    5090
Encroach Node=221523.4
       1    4850    5150
Encroach Node=221469.5
       1    4850    5150
Encroach Node=221415.6
       1    4850    5150
Encroach Node=220426.4
       1  4879.5    5290
Encroach Node=219577.1
       1  4890.3  5115.2
Encroach Node=218625.5
       1  4872.7    5360
Encroach Node=217899.8
       1  4886.8  5109.4
Encroach Node=216802.9
       1  4895.9    5670
Encroach Node=216040.3
       1    4850    5250
Encroach Node=214968.0
       1    4980    5250
Encroach Node=214945.0
       1    4980    5250
Encroach Node=214922.0
       1    4980    5250
Encroach Node=214866.8
       1    4875    5110
Encroach Node=214821.3
       1    4875    5110
Encroach Node=214775.8
       1    4875    5110
Encroach Node=214672.8
       1    4900    5100
Encroach Node=214628.5
       1    4900    5100
Encroach Node=214584.2
       1    4900    5100
Encroach Node=213687.7
       1    4810  5047.9
Encroach Node=212742.1
       1    4815    5060
Encroach Node=211631.3
       1    4775    5295
Encroach Node=210975.8
       1    4945    5095
Encroach Node=209864.1
       1    4940    5260
Encroach Node=208924.8
       1    4890    5120
Encroach Node=207774.7
       1  4893.8    5400
Encroach Node=206741.3
       1    4915  5143.6
Encroach Node=205679.6
       1    4900    5150
Encroach Node=205102.2
       1    4900    5150
Encroach Node=204727.6
       1    4900    5100
Encroach Node=204673.8
       1    4900    5100
Encroach Node=204620.0
       1    4900    5100
Encroach Node=203658.9
       1    4710    5082
Encroach Node=202834.1
       1    4880    5125
Encroach Node=201783.6
       1    4880  5141.6
Encroach Node=201212.1
       1    4910  5276.7
Encroach Node=200299.3
       1    4850  5076.4
Encroach Node=200076.4
       1  4869.5  5124.9
Encroach Node=200020.5
       1  4869.5  5124.9
Encroach Node=199964.6
       1  4869.5  5124.9
Encroach Node=199440.6
       1  4921.7    5315
Encroach Node=198496.4
       1    4880    5135
Encroach Node=197506.8
       1    4895    5170
Encroach Node=196463.1
       1    4755    5060
Encroach Node=196182.3
       1    4890    5075
Encroach Node=196149.0
       1    4890    5075
Encroach Node=196115.7
       1    4890    5075
Encroach Node=195567.4
       1    4875    5455
Encroach Node=194614.1
       1    4940    5280
Encroach Node=193675.6
       1    4800    5070
Encroach Node=192820.3
       1    4830    5070
Encroach Node=191722.7
       1    4640    5105
Encroach Node=190794.0
       1    4905    5160
Encroach Node=189869.8
       1    4645    5120
Encroach Node=188903.7
       1    4800    5245
Encroach Node=187878.1
       1    4870    5060
Encroach Node=186536.1
       1    4887    5420
Encroach Node=185293.8
       1    4925    5220
Encroach Node=184862.8
       1    4905    5105
Encroach Node=184807.6
       1    4905    5105
Encroach Node=184752.4
       1    4905    5105
Encroach Node=184295.8
       1    4850  5080.3
Encroach Node=183335.1
       1    4945    5080
Encroach Node=182381.6
       1    4890    5150
Encroach Node=181623.0
       1    4715    5390
Encroach Node=180731.2
       1    4890    5200
Encroach Node=179838.1
       1  4779.1    5125
Encroach Node=179305.6
       1    4910    5100
Encroach Node=178955.5
       1    4935    5185
Encroach Node=178899.3
       1    4935    5185
Encroach Node=178843.1
       1    4935    5185
Encroach Node=177732.9
       1  4844.1    5125
Encroach Node=176644.1
       1    4695    5205
Encroach Node=175675.6
       1    4885  5189.1
Encroach Node=173819.4
       1    4230    5095
Encroach Node=172846.5
       1    4935    5480
Encroach Node=171967.4
       1    4475  5098.1
Encroach Node=171168.9
       1    4905    5315
Encroach Node=170256.0
       1    4885    5110
Encroach Node=169087.1
       1    4895    5455
Encroach Node=168169.9
       1    4770  5100.2
Encroach Node=167249.9
       1    4925  5170.5
Encroach Node=166879.7
       1    4835    5275
Encroach Node=166613.0
       1    4940    5660
Encroach Node=166585.6
       1    4940    5660
Encroach Node=166558.2
       1    4940    5660
Encroach Node=166297.3
       1    4855    5125
Encroach Node=165903.2
       1    4825    5110
Encroach Node=165476.1
       1    4915    5085
Encroach Node=165428.1
       1    4915    5085
Encroach Node=165380.1
       1    4915    5085
Encroach Node=164555.2
       1  4899.4    5110
Encroach Node=163635.5
       1    4585    5060
Encroach Node=162811.9
       1    4835    5075
Encroach Node=161822.3
       1    4840  5081.8
Encroach Node=160630.7
       1  4896.1    5120
Encroach Node=159757.4
       1    4880  5107.7
Encroach Node=158811.6
       1    4720    5170
Encroach Node=157933.4
       1    4840    5165
Encroach Node=156882.1
       1    4885    5065
Encroach Node=156116.3
       1    4880  5186.7
Encroach Node=155861.6
       1    4880    5210
Encroach Node=155805.1
       1    4880    5210
Encroach Node=155748.6
       1    4880    5210
Encroach Node=154890.7
       1    4870    5100
Encroach Node=153992.6
       1    4840    5200
Encroach Node=153119.9
       1    4800    5120
Encroach Node=153108.9
       1    4800    5120
Encroach Node=153097.9
       1    4800    5120
Encroach Node=152376.3
       1    4600    5080
Encroach Node=151996.2
       1    4698    5130
Encroach Node=151963.3
       1    4698    5130
Encroach Node=151930.4
       1    4698    5130
Encroach Node=151925.3
       1    4870    5285
Encroach Node=151846.3
       1    4890    5285
Encroach Node=151767.3
       1    4870    5285
Encroach Node=151736.6
       1    4856    5132
Encroach Node=151711.1
       1    4856    5132
Encroach Node=151685.6
       1    4856    5132
Encroach Node=151353.8
       1    4700    5175
Encroach Node=150358.8
       1    4800    5080
Encroach Node=149526.4
       1    4775    5100
Encroach Node=149122.7
       1    4850    5080
Encroach Node=148795.4
       1    4900    5170
Encroach Node=148768.4
       1    4900    5170
Encroach Node=148741.4
       1    4900    5170
Encroach Node=147632.4
       1    4850  5140.4
Encroach Node=146698.0
       1  4858.2    5150
Encroach Node=145723.9
       1    4800    5100
Encroach Node=144753.5
       1  4894.4    5150
Encroach Node=143966.8
       1    4675    5100
Encroach Node=143078.2
       1    4800    5180
Encroach Node=142061.4
       1    4750    5125
Encroach Node=141320.1
       1    4600    5200
Encroach Node=140116.2
       1    4800    5300
Encroach Node=139320.0
       1    4500  5120.7
Encroach Node=138607.9
       1    4500    5400
Encroach Node=137732.0
       1    4800    5430
Encroach Node=137113.0
       1    4850    5236
Encroach Node=136331.2
       1    4870    5325
Encroach Node=135666.2
       1    4675    5175
Encroach Node=134706.7
       1    4570    5350
Encroach Node=134090.6
       1    4330    5085
Encroach Node=133772.1
       1    4450    5210
Encroach Node=133760.1
       1    4450    5210
Encroach Node=133748.1
       1    4450    5210
Encroach Node=132963.8
       1  4921.6    5200
Encroach Node=131789.8
       1    4800    5200
Encroach Node=130765.5
       1    4850    5220
Encroach Node=129725.3
       1    4600    5150
Encroach Node=129163.2
       1    4850    5160
Encroach Node=128326.9
       1    4850    5225
Encroach Node=128104.6
       1    4820    5145
Encroach Node=128066.7
       1    4820    5145
Encroach Node=128028.8
       1    4820    5145
Encroach Node=126647.0
       1    4830    5225
Encroach Node=125376.9
       1    4875    5150
Encroach Node=124983.5
       1    4850    5150
Encroach Node=124644.1
       1    4771    5112
Encroach Node=124591.8
       1    4771    5112
Encroach Node=124539.5
       1    4771    5112
Encroach Node=123658.2
       1    4750    5400
Encroach Node=123138.8
       1    4700    5400
Encroach Node=122627.1
       1    4675    5450
Encroach Node=122572.1
       1    4675    5450
Encroach Node=122517.1
       1    4675    5450
Encroach Node=121229.5
       1    4640    5350
Encroach Node=120962.2
       1    4625    5240
Encroach Node=120005.2
       1    4350    5154
Encroach Node=119952.6
       1    4350    5154
Encroach Node=119900.0
       1    4350    5154
Encroach Node=119495.9
       1    4500    5300
Encroach Node=118667.7
       1    4820    5250
Encroach Node=118466.1
       1    4740    5260
Encroach Node=118418.1
       1    4740    5260
Encroach Node=118370.1
       1    4740    5260
Encroach Node=117845.4
       1    4775    5130
Encroach Node=117204.3
       1    4850    5150
Encroach Node=116395.7
       1    4910    5165
Encroach Node=116167.6
       1    4859    5096
Encroach Node=116121.9
       1    4859    5096
Encroach Node=116076.2
       1    4859    5096
Encroach Node=115655.5
       1    4740    5270
Encroach Node=115635.5
       1    4740    5270
Encroach Node=115615.5
       1    4740    5270
Encroach Node=115573.5
       1    4735    5245
Encroach Node=115553.5
       1    4735    5245
Encroach Node=115533.5
       1    4735    5245
Encroach Node=115214.0
       1    4870    5175
Encroach Node=115168.5
       1    4870    5175
Encroach Node=115123.0
       1    4870    5175
Encroach Node=114890.5
       1    4890    5295
Encroach Node=114864.5
       1    4890    5295
Encroach Node=114838.5
       1    4890    5295
Encroach Node=114492.0
       1    4840    5110
Encroach Node=114195.9
       1    4885    5180
Encroach Node=114168.9
       1    4885    5180
Encroach Node=114141.9
       1    4885    5180
Encroach Node=114097.4
       1    4885    5250
Encroach Node=114070.4
       1    4885    5250
Encroach Node=114043.4
       1    4885    5250
Encroach Node=113644.0
       1    4800    5100
Encroach Node=113411.6
       1    4910    5094
Encroach Node=113374.3
       1    4910    5094
Encroach Node=113337.0
       1    4910    5094
Encroach Node=113266.4
       1    4870    5090
Encroach Node=113238.6
       1    4870    5115
Encroach Node=113210.8
       1    4870    5115
Encroach Node=112974.0
       1    4895    5098
Encroach Node=112944.9
       1    4895    5098
Encroach Node=112915.8
       1    4895    5098
Encroach Node=112575.5
       1    4885    5085
Encroach Node=112534.5
       1    4885    5085
Encroach Node=112493.5
       1    4885    5085
Encroach Node=112003.3
       1    4880    5138
Encroach Node=111953.3
       1    4880    5138
Encroach Node=111903.3
       1    4880    5138
Encroach Node=111853.5
       1    4890    5130
Encroach Node=111818.6
       1    4890    5130
Encroach Node=111783.7
       1    4890    5130
Encroach Node=111626.7
       1    4875    5090
Encroach Node=111518.6
       1    4875    5090
Encroach Node=111410.5
       1    4875    5090
Encroach Node=110876.6
       1    4775    5155
Encroach Node=110837.8
       1    4775    5155
Encroach Node=110799.0
       1    4775    5155
Encroach Node=110672.7
       1    4775    5120
Encroach Node=110643.7
       1    4775    5120
Encroach Node=110614.7
       1    4775    5120
Encroach Node=110200.2
       1  4913.8    5220
Encroach Node=110154.2
       1  4913.8    5220
Encroach Node=110108.2
       1  4913.8    5220
Encroach Node=109551.7
       1    4875    5150
Encroach Node=109518.7
       1    4875    5150
Encroach Node=109485.7
       1    4875    5150
Encroach Node=109440.2
       1    4815    5115
Encroach Node=109395.2
       1    4815    5115
Encroach Node=109350.2
       1    4815    5075
Encroach Node=109119.0
       1    4810    5070
Encroach Node=109103.1
       1    4840    5070
Encroach Node=109087.2
       1    4860    5070
Encroach Node=108565.3
       1    4830  5139.7
Encroach Node=108334.0
       1    4800  5140.6
Encroach Node=107179.4
       1    4870    5103
Encroach Node=107158.9
       1    4870    5103
Encroach Node=107138.4
       1    4870    5103
Encroach Node=106594.0
       1  4866.6  5088.9
Encroach Node=106151.4
       1  4866.6  5088.9
Encroach Node=106131.1
       1  4866.6  5088.9
Encroach Node=106110.8
       1  4866.6  5088.9
Encroach Node=105705.4
       1  4863.8  5130.2
Encroach Node=105667.4
       1  4863.8  5130.2
Encroach Node=105629.4
       1  4863.8  5130.2
Encroach Node=105211.0
       1  4730.2  5116.8
Encroach Node=104608.2
       1    4820  5285.8
Encroach Node=104370.8
       1    4910    5220
Encroach Node=104350.0
       1    4910    5220
Encroach Node=104329.2
       1    4910    5220
Encroach Node=103664.0
       1    4920    5120
Encroach Node=102875.3
       1    4850    5100
Encroach Node=102847.5
       1    4850    5105
Encroach Node=102819.7
       1    4850    5105
Encroach Node=102309.0
       1  4882.9  5097.4
Encroach Node=101828.0
       1  4882.9  5097.4
Encroach Node=101790.1
       1  4882.9  5097.4
Encroach Node=101752.2
       1  4882.9  5097.4
Encroach Node=101007.3
       1  4850.5  5149.5
Encroach Node=99992.6
       1  4843.9  5146.6
Encroach Node=98399.4
       1  4865.2  5190.3
Encroach Node=97517.4
       1  4861.4  5167.3
Encroach Node=96028.6
       1 4879.97 5144.88
Encroach Node=95985.1
       1 4879.97 5144.88
Encroach Node=95941.6
       1 4879.97 5144.88
Encroach Node=95362.9
       1  4822.6    5214
Encroach Node=94280.7
       1  4900.2    5152
Encroach Node=93495.6
       1    4840  5214.9
Encroach Node=92795.6
       1    4840  5202.1
Encroach Node=92741.1
       1    4840  5202.1
Encroach Node=92686.6
       1    4840  5202.1
Encroach Node=90936.7
       1  4717.8  5157.4
Encroach Node=89918.4
       1  4823.9  5159.4
Encroach Node=88579.0
       1  4788.7  5208.7
Encroach Node=87591.9
       1  4856.8  5199.7
Encroach Node=86660.2
       1  4857.9  5159.2
Encroach Node=86641.7
       1  4857.9  5159.2
Encroach Node=86623.2
       1  4857.9  5159.2
Encroach Node=85855.2
       1  4890.1  5113.6
Encroach Node=85238.7
       1  4890.1  5113.6
Encroach Node=84561.7
       1  4890.1  5113.6
Encroach Node=84531.4
       1  4890.1  5113.6
Encroach Node=84501.1
       1  4890.1  5113.6
Encroach Node=84252.6
       1  4871.6  5116.1
Encroach Node=84222.3
       1  4871.6  5116.1
Encroach Node=84192.0
       1  4871.6  5116.1
Encroach Node=83635.7
       1  4794.3  5258.9
Encroach Node=81786.1
       1  4799.7  5268.7
Encroach Node=80903.1
       1    4798  5243.7
Encroach Node=80883.1
       1    4798  5243.7
Encroach Node=80863.1
       1    4798  5243.7
Encroach Node=80538.0
       1  4730.8  5255.8
Encroach Reach=W100-00-00_0805
Encroach Node=248647.7
       1  4923.3  5071.9
Encroach Node=248547.8
       1  4923.3  5071.9
Encroach Node=248481.1
       1  4923.3  5071.9
Encroach Node=248414.4
       1  4923.3  5071.9
Encroach Node=247502.0
       1  4915.1  5075.5
Encroach Node=246449.8
       1  4922.3  5095.7
Encroach Node=245413.7
       1  4894.2  5070.5
Encroach Node=244345.5
       1 4934.91  5116.1
Encroach Node=243452.9
       1  4897.5  5113.5
Encroach Node=242655.3
       1  4915.9  5074.6
Encroach Node=241917.5
       1    4855  5076.8
Encroach Node=241646.1
       1    4930    5090
Encroach Node=241632.7
       1    4930    5090
Encroach Node=241619.3
       1    4930    5090
Encroach Node=241079.0
       1  4881.6  5132.6
Encroach Node=240579.0
       1    4863    5115
Encroach Node=240376.3
       1    4863  5110.8
Encroach Node=240315.3
       1    4863  5110.8
Encroach Node=240254.3
       1    4863  5110.8
Encroach Node=239993.6
       1    4895    5100
Encroach Node=239036.8
       1    4925    5110
Encroach Node=238060.4
       1  4902.5    5105
Encroach Node=237276.3
       1    4880    5080
Encroach Node=236611.0
       1    4870    5080
Encroach Node=235706.9
       1    4890  5088.1
Encroach Node=234807.9
       1    4885    5195
Encroach Node=233698.4
       1  4891.8    5330
Encroach Node=233029.3
       1 4900.17 5097.77
Encroach Node=232816.9
       1 4900.17 5097.77
Encroach Node=232805.9
       1 4900.17 5097.77
Encroach Node=232794.9
       1 4900.17 5097.77
Encroach Node=232790.8
       1 4897.99 5104.99
Encroach Node=232732.9
       1 4897.99 5104.99
Encroach Node=232681.7
       1 4897.99 5104.99
Encroach Node=232669.7
       1 4897.79 5104.99
Encroach Node=232657.7
       1 4897.79 5104.99
Encroach Node=232645.3
       1 4897.79 5104.99
Encroach Node=232632.3
       1 4897.79 5104.99
Encroach Node=231798.0
       1  4862.7  5081.4
Encroach Node=230908.0
       1  4886.4    5405
Encroach Node=229882.5
       1    4475    5115
Encroach Node=228917.1
       1    4530    5280
Encroach Node=228060.7
       1    4700    5200
Encroach Node=227524.1
       1    4870    5120
Encroach Node=227144.7
       1    4800    5105
Encroach Node=227088.2
       1    4800    5105
Encroach Node=227031.7
       1    4800    5105
Encroach Node=225979.2
       1    4800  5091.1
Encroach Node=224981.6
       1    4895    5275
Encroach Node=224198.0
       1    4830  5126.5
Encroach Node=223061.1
       1    4850  5126.5
Encroach Node=222172.8
       1    4840  5108.8
Encroach Node=221721.3
       1    4900    5090
Encroach Node=221523.4
       1    4850    5150
Encroach Node=221469.5
       1    4850    5150
Encroach Node=221415.6
       1    4850    5150
Encroach Node=220426.4
       1  4879.5    5290
Encroach Node=219577.1
       1  4890.3  5115.2
Encroach Node=218625.5
       1  4872.7    5360
Encroach Node=217899.8
       1  4886.8  5109.4
Encroach Node=216802.9
       1  4895.9    5670
Encroach Node=216032.5
       1 4798.25 5198.25
Encroach Node=215429.6
       1 4645.52 5045.52
Encroach Node=215022.5
       1    5020    5290
Encroach Node=214987.8
       1    5020    5290
Encroach Node=214953.1
       1    5020    5290
Encroach Node=214895.5
       1    4870    5115
Encroach Node=214806.4
       1    4870    5115
Encroach Node=214717.4
       1    4870    5115
Encroach Node=214669.3
       1    4900    5100
Encroach Node=214625.3
       1    4900    5100
Encroach Node=214581.3
       1    4900    5100
Encroach Node=213687.7
       1    4810  5047.9
Encroach Node=212742.1
       1    4815    5060
Encroach Node=211631.3
       1    4775    5295
Encroach Node=210975.8
       1    4945    5095
Encroach Node=209864.1
       1    4940    5260
Encroach Node=208924.8
       1    4890    5120
Encroach Node=207774.7
       1  4893.8    5400
Encroach Node=206741.3
       1    4915  5143.6
Encroach Node=205679.6
       1    4900    5150
Encroach Node=205102.2
       1    4900    5150
Encroach Node=204727.6
       1    4900    5100
Encroach Node=204673.8
       1    4900    5100
Encroach Node=204620.0
       1    4900    5100
Encroach Node=203658.9
       1    4710    5082
Encroach Node=202834.1
       1    4880    5125
Encroach Node=201783.6
       1    4880  5141.6
Encroach Node=201212.1
       1    4910  5276.7
Encroach Node=200299.3
       1    4850  5076.4
Encroach Node=200076.4
       1  4869.5  5124.9
Encroach Node=200020.5
       1  4869.5  5124.9
Encroach Node=199964.6
       1  4869.5  5124.9
Encroach Node=199440.6
       1  4921.7    5315
Encroach Node=198496.4
       1    4880    5135
Encroach Node=197506.8
       1    4895    5170
Encroach Node=196463.1
       1    4755    5060
Encroach Node=196182.3
       1    4890    5075
Encroach Node=196149.0
       1    4890    5075
Encroach Node=196115.7
       1    4890    5075
Encroach Node=195567.4
       1    4875    5455
Encroach Node=194614.1
       1    4940    5280
Encroach Node=193675.6
       1    4800    5070
Encroach Node=192820.3
       1    4830    5070
Encroach Node=191722.7
       1    4640    5105
Encroach Node=190794.0
       1    4905    5160
Encroach Node=189869.8
       1    4645    5120
Encroach Node=188903.7
       1    4800    5245
Encroach Node=187878.1
       1    4870    5060
Encroach Node=186536.1
       1    4887    5420
Encroach Node=185293.8
       1    4925    5220
Encroach Node=184862.8
       1    4905    5105
Encroach Node=184807.6
       1    4905    5105
Encroach Node=184752.4
       1    4905    5105
Encroach Node=184295.8
       1    4850  5080.3
Encroach Node=183335.1
       1    4945    5080
Encroach Node=182381.6
       1    4890    5150
Encroach Node=181623.0
       1    4715    5390
Encroach Node=180731.2
       1    4890    5200
Encroach Node=179838.1
       1  4779.1    5125
Encroach Node=179305.6
       1    4910    5100
Encroach Node=178955.5
       1    4935    5185
Encroach Node=178899.3
       1    4935    5185
Encroach Node=178843.1
       1    4935    5185
Encroach Node=177732.9
       1  4844.1    5125
Encroach Node=176644.1
       1    4695    5205
Encroach Node=175675.6
       1    4885  5189.1
Encroach Node=173819.4
       1    4230    5095
Encroach Node=172846.5
       1    4935    5480
Encroach Node=171967.4
       1    4475  5098.1
Encroach Node=171168.9
       1    4905    5315
Encroach Node=170256.0
       1    4885    5110
Encroach Node=169087.1
       1    4895    5455
Encroach Node=168169.9
       1    4770  5100.2
Encroach Node=167249.9
       1    4925  5170.5
Encroach Node=166879.7
       1    4835    5275
Encroach Node=166613.0
       1    4940    5660
Encroach Node=166585.6
       1    4940    5660
Encroach Node=166558.2
       1    4940    5660
Encroach Node=166297.3
       1    4855    5125
Encroach Node=165903.2
       1    4825    5110
Encroach Node=165476.1
       1    4915    5085
Encroach Node=165428.1
       1    4915    5085
Encroach Node=165380.1
       1    4915    5085
Encroach Node=164555.2
       1  4899.4    5110
Encroach Node=163635.5
       1    4585    5060
Encroach Node=162811.9
       1    4835    5075
Encroach Node=161822.3
       1    4840  5081.8
Encroach Node=160630.7
       1  4896.1    5120
Encroach Node=159757.4
       1    4880  5107.7
Encroach Node=158811.6
       1    4720    5170
Encroach Node=157933.4
       1    4840    5165
Encroach Node=156882.1
       1    4885    5065
Encroach Node=156116.3
       1    4880  5186.7
Encroach Node=155861.6
       1    4880    5210
Encroach Node=155805.1
       1    4880    5210
Encroach Node=155748.6
       1    4880    5210
Encroach Node=154890.7
       1    4870    5100
Encroach Node=153992.6
       1    4840    5200
Encroach Node=153119.9
       1    4800    5120
Encroach Node=153108.9
       1    4800    5120
Encroach Node=153097.9
       1    4800    5120
Encroach Node=152376.3
       1    4600    5080
Encroach Node=151996.2
       1    4698    5130
Encroach Node=151963.3
       1    4698    5130
Encroach Node=151930.4
       1    4698    5130
Encroach Node=151925.3
       1    4870    5285
Encroach Node=151846.3
       1    4890    5285
Encroach Node=151767.3
       1    4870    5285
Encroach Node=151736.6
       1    4856    5132
Encroach Node=151711.1
       1    4856    5132
Encroach Node=151685.6
       1    4856    5132
Encroach Node=151353.8
       1    4700    5175
Encroach Node=150358.8
       1    4800    5080
Encroach Node=149526.4
       1    4775    5100
Encroach Node=149122.7
       1    4850    5080
Encroach Node=148795.4
       1    4900    5170
Encroach Node=148768.4
       1    4900    5170
Encroach Node=148741.4
       1    4900    5170
Encroach Node=147632.4
       1    4850  5140.4
Encroach Node=146698.0
       1  4858.2    5150
Encroach Node=145723.9
       1    4800    5100
Encroach Node=144753.5
       1  4894.4    5150
Encroach Node=143966.8
       1    4675    5100
Encroach Node=143078.2
       1    4800    5180
Encroach Node=142061.4
       1    4750    5125
Encroach Node=141320.1
       1    4600    5200
Encroach Node=140116.2
       1    4800    5300
Encroach Node=139320.0
       1    4500  5120.7
Encroach Node=138607.9
       1    4500    5400
Encroach Node=137732.0
       1    4800    5430
Encroach Node=137113.0
       1    4850    5236
Encroach Node=136331.2
       1    4870    5325
Encroach Node=135666.2
       1    4675    5175
Encroach Node=134706.7
       1    4570    5350
Encroach Node=134090.6
       1    4330    5085
Encroach Node=133772.1
       1    4450    5210
Encroach Node=133760.1
       1    4450    5210
Encroach Node=133748.1
       1    4450    5210
Encroach Node=132963.8
       1  4921.6    5200
Encroach Node=131789.8
       1    4800    5200
Encroach Node=130765.5
       1    4850    5220
Encroach Node=129725.3
       1    4600    5150
Encroach Node=129163.2
       1    4850    5160
Encroach Node=128326.9
       1    4850    5225
Encroach Node=128104.6
       1    4820    5145
Encroach Node=128066.7
       1    4820    5145
Encroach Node=128028.8
       1    4820    5145
Encroach Node=126647.0
       1    4830    5225
Encroach Node=125376.9
       1    4875    5150
Encroach Node=124983.5
       1    4850    5150
Encroach Node=124644.1
       1    4771    5112
Encroach Node=124591.8
       1    4771    5112
Encroach Node=124539.5
       1    4771    5112
Encroach Node=123658.2
       1    4750    5400
Encroach Node=123138.8
       1    4700    5400
Encroach Node=122627.1
       1    4675    5450
Encroach Node=122572.1
       1    4675    5450
Encroach Node=122517.1
       1    4675    5450
Encroach Node=122371.6
       1    4715    5480
Encroach Node=122265
       1    4715    5480
Encroach Node=122210.0
       1    4715    5480
Encroach Node=122036.7
       1    4745    5470
Encroach Node=121229.5
       1    4640    5350
Encroach Node=120962.2
       1    4625    5240
Encroach Node=120005.2
       1    4350    5154
Encroach Node=119952.6
       1    4350    5154
Encroach Node=119900.0
       1    4350    5154
Encroach Node=119495.9
       1    4500    5300
Encroach Node=118667.7
       1    4820    5250
Encroach Node=118466.1
       1    4740    5260
Encroach Node=118418.1
       1    4740    5260
Encroach Node=118370.1
       1    4740    5260
Encroach Node=117845.4
       1    4775    5130
Encroach Node=117204.3
       1    4850    5150
Encroach Node=116395.7
       1    4910    5165
Encroach Node=116167.6
       1    4859    5096
Encroach Node=116121.9
       1    4859    5096
Encroach Node=116076.2
       1    4859    5096
Encroach Node=115655.5
       1    4740    5270
Encroach Node=115635.5
       1    4740    5270
Encroach Node=115615.5
       1    4740    5270
Encroach Node=115573.5
       1    4735    5245
Encroach Node=115553.5
       1    4735    5245
Encroach Node=115533.5
       1    4735    5245
Encroach Node=115214.0
       1    4870    5175
Encroach Node=115168.5
       1    4870    5175
Encroach Node=115123.0
       1    4870    5175
Encroach Node=114890.5
       1    4890    5295
Encroach Node=114864.5
       1    4890    5295
Encroach Node=114838.5
       1    4890    5295
Encroach Node=114492.0
       1    4840    5110
Encroach Node=114195.9
       1    4885    5180
Encroach Node=114168.9
       1    4885    5180
Encroach Node=114141.9
       1    4885    5180
Encroach Node=114097.4
       1    4885    5250
Encroach Node=114070.4
       1    4885    5250
Encroach Node=114043.4
       1    4885    5250
Encroach Node=113644.0
       1    4800    5100
Encroach Node=113411.6
       1    4910    5094
Encroach Node=113374.3
       1    4910    5094
Encroach Node=113337.0
       1    4910    5094
Encroach Node=113266.4
       1    4870    5090
Encroach Node=113238.6
       1    4870    5115
Encroach Node=113210.8
       1    4870    5115
Encroach Node=112974.0
       1    4895    5098
Encroach Node=112944.9
       1    4895    5098
Encroach Node=112915.8
       1    4895    5098
Encroach Node=112575.5
       1    4885    5085
Encroach Node=112534.5
       1    4885    5085
Encroach Node=112493.5
       1    4885    5085
Encroach Node=112003.3
       1    4880    5138
Encroach Node=111953.3
       1    4880    5138
Encroach Node=111903.3
       1    4880    5138
Encroach Node=111853.5
       1    4890    5130
Encroach Node=111818.6
       1    4890    5130
Encroach Node=111783.7
       1    4890    5130
Encroach Node=111626.7
       1    4875    5090
Encroach Node=111518.6
       1    4875    5090
Encroach Node=111410.5
       1    4875    5090
Encroach Node=110876.6
       1    4775    5155
Encroach Node=110837.8
       1    4775    5155
Encroach Node=110799.0
       1    4775    5155
Encroach Node=110672.7
       1    4775    5120
Encroach Node=110643.7
       1    4775    5120
Encroach Node=110614.7
       1    4775    5120
Encroach Node=110200.2
       1  4913.8    5220
Encroach Node=110154.2
       1  4913.8    5220
Encroach Node=110108.2
       1  4913.8    5220
Encroach Node=109551.7
       1    4875    5150
Encroach Node=109518.7
       1    4875    5150
Encroach Node=109485.7
       1    4875    5150
Encroach Node=109440.2
       1    4815    5115
Encroach Node=109395.2
       1    4815    5115
Encroach Node=109350.2
       1    4815    5075
Encroach Node=109119.0
       1    4810    5070
Encroach Node=109103.1
       1    4840    5070
Encroach Node=109087.2
       1    4860    5070
Encroach Node=108565.3
       1    4830  5139.7
Encroach Node=108334.0
       1    4800  5140.6
Encroach Node=107179.4
       1    4870    5103
Encroach Node=107158.9
       1    4870    5103
Encroach Node=107138.4
       1    4870    5103
Encroach Node=106594.0
       1  4866.6  5088.9
Encroach Node=106151.4
       1  4866.6  5088.9
Encroach Node=106131.1
       1  4866.6  5088.9
Encroach Node=106110.8
       1  4866.6  5088.9
Encroach Node=105705.4
       1  4863.8  5130.2
Encroach Node=105667.4
       1  4863.8  5130.2
Encroach Node=105629.4
       1  4863.8  5130.2
Encroach Node=105211.0
       1  4730.2  5116.8
Encroach Node=104608.2
       1    4820  5285.8
Encroach Node=104370.8
       1    4910    5220
Encroach Node=104350.0
       1    4910    5220
Encroach Node=104329.2
       1    4910    5220
Encroach Node=103664.0
       1    4920    5120
Encroach Node=102875.3
       1    4850    5100
Encroach Node=102847.5
       1    4850    5105
Encroach Node=102819.7
       1    4850    5105
Encroach Node=102309.0
       1  4882.9  5097.4
Encroach Node=101828.0
       1  4882.9  5097.4
Encroach Node=101790.1
       1  4882.9  5097.4
Encroach Node=101752.2
       1  4882.9  5097.4
Encroach Node=101007.3
       1  4850.5  5149.5
Encroach Node=99992.6
       1  4843.9  5146.6
Encroach Node=98399.4
       1  4865.2  5190.3
Encroach Node=97517.4
       1  4861.4  5167.3
Encroach Node=96028.6
       1 4879.97 5144.88
Encroach Node=95985.1
       1 4879.97 5144.88
Encroach Node=95941.6
       1 4879.97 5144.88
Encroach Node=95362.9
       1  4822.6    5214
Encroach Node=94280.7
       1  4900.2    5152
Encroach Node=93495.6
       1    4840  5214.9
Encroach Node=92795.6
       1    4840  5202.1
Encroach Node=92741.1
       1    4840  5202.1
Encroach Node=92686.6
       1    4840  5202.1
Encroach Node=90936.7
       1  4717.8  5157.4
Encroach Node=89918.4
       1  4823.9  5159.4
Encroach Node=88579.0
       1  4788.7  5208.7
Encroach Node=87591.9
       1  4856.8  5199.7
Encroach Node=86660.2
       1  4857.9  5159.2
Encroach Node=86641.7
       1  4857.9  5159.2
Encroach Node=86623.2
       1  4857.9  5159.2
Encroach Node=85855.2
       1  4890.1  5113.6
Encroach Node=85238.7
       1  4890.1  5113.6
Encroach Node=84561.7
       1  4890.1  5113.6
Encroach Node=84531.4
       1  4890.1  5113.6
Encroach Node=84501.1
       1  4890.1  5113.6
Encroach Node=84252.6
       1  4871.6  5116.1
Encroach Node=84222.3
       1  4871.6  5116.1
Encroach Node=84192.0
       1  4871.6  5116.1
Encroach Node=83635.7
       1  4794.3  5258.9
Encroach Node=81786.1
       1  4799.7  5268.7
Encroach Node=80903.1
       1    4798  5243.7
Encroach Node=80883.1
       1    4798  5243.7
Encroach Node=80863.1
       1    4798  5243.7
Encroach Node=80538.0
       1  4730.8  5255.8
BEGIN DESCRIPTION:
FEMA Effective Floodway 2007 + LOMR 12-06-1071P + LOMR 14-06-2581P + LOMR 20-06-3136P
END DESCRIPTION:
Computation Interval=1HOUR
Output Interval=1HOUR
Run HTab= 0
Run UNet= 0
Run PostProcess= 0
UNET Theta= 1
UNET ZTol= 0.02
UNET ZSATol= 0.1
UNET MxIter= 20
UNET MaxInSteps= 20
UNET DtIC= 0
UNET DtMin= 0
UNET MaxCRTS= 20
UNET WFStab= 2
UNET SFStab= 1
UNET WFX= 1
UNET SFX= 1
UNET Convert EG Bridges=-1
UNET Use Existing IB Tables=-1
Instantaneous Interval=1HOUR
DSS File=dss
Write IC File= 0
IC Time=0
Write Velocity= 0
Write Detailed= 0

--- W100-00-00.f01 (steady flow) ---

Flow Title=FEMA Effective Multi-Profile 2007
Version=Version 3.0.1  May 2012
Number of Profiles= 4
Profile Names=10PCT_10yr,2PCT_50yr,1PCT_100yr,0.2PCT_500yr
River Rch & RM=W100-00-00,W100-00-00_0805 ,248647.7
    1765    3051    3803    6017
River Rch & RM=W100-00-00,W100-00-00_0805 ,247502
    1752    3042    3797    5984
River Rch & RM=W100-00-00,W100-00-00_0805 ,245413.7
    1724    3022    3784    5907
River Rch & RM=W100-00-00,W100-00-00_0805 ,243452.9
    1698    3003    3772    5835
River Rch & RM=W100-00-00,W100-00-00_0805 ,241079
    1665    2980    3758    5748
River Rch & RM=W100-00-00,W100-00-00_0805 ,239993.6
    3152    5370    6670   10178
River Rch & RM=W100-00-00,W100-00-00_0805 ,236611
    3361    5608    6923   10512
River Rch & RM=W100-00-00,W100-00-00_0805 ,234807.9
    3539    5811    7139   10797
River Rch & RM=W100-00-00,W100-00-00_0805 ,232816.9
    3634    5919    7254   10948
River Rch & RM=W100-00-00,W100-00-00_0805 ,231798
    3708    6003    7344   11067
River Rch & RM=W100-00-00,W100-00-00_0805 ,230908
    3878    6197    7549   11338
River Rch & RM=W100-00-00,W100-00-00_0805 ,228917.1
    4040    6381    7745   11597
River Rch & RM=W100-00-00,W100-00-00_0805 ,227144.7
    4139    6499    7870   11750
River Rch & RM=W100-00-00,W100-00-00_0805 ,225979.2
    4297    6735    8117   11964
River Rch & RM=W100-00-00,W100-00-00_0805 ,224981.6
    4484    7022    8422   12239
River Rch & RM=W100-00-00,W100-00-00_0805 ,223061.1
    4580    7185    8606   12425
River Rch & RM=W100-00-00,W100-00-00_0805 ,221523.4
    4616    7246    8675   12495
River Rch & RM=W100-00-00,W100-00-00_0805 ,220426.4
    4748    7471    8930   12752
River Rch & RM=W100-00-00,W100-00-00_0805 ,217899.8
    4835    7617    9096   12919
River Rch & RM=W100-00-00,W100-00-00_0805 ,215022.5
    4922    7765    9264   13088
River Rch & RM=W100-00-00,W100-00-00_0805 ,214669.3
    4942    7796    9299   13126
River Rch & RM=W100-00-00,W100-00-00_0805 ,213687.7
    5040    7946    9467   13311
River Rch & RM=W100-00-00,W100-00-00_0805 ,211631.3
    5116    8063    9600   13465
River Rch & RM=W100-00-00,W100-00-00_0805 ,209864.1
    5230    8237    9809   13744
River Rch & RM=W100-00-00,W100-00-00_0805 ,205679.6
    5288    8324    9914   13883
River Rch & RM=W100-00-00,W100-00-00_0805 ,203658.9
    5497    8632   10276   14391
River Rch & RM=W100-00-00,W100-00-00_0805 ,201783.6
    5620    8813   10489   14689
River Rch & RM=W100-00-00,W100-00-00_0805 ,200076.4
    5833    9127   10859   15206
River Rch & RM=W100-00-00,W100-00-00_0805 ,199440.6
    5977    9341   11113   15587
River Rch & RM=W100-00-00,W100-00-00_0805 ,196182.3
    6059    9465   11262   15820
River Rch & RM=W100-00-00,W100-00-00_0805 ,195567.4
    6140    9586   11407   16047
River Rch & RM=W100-00-00,W100-00-00_0805 ,192820.3
    6303    9830   11699   16503
River Rch & RM=W100-00-00,W100-00-00_0805 ,188903.7
    6388    9958   11852   16742
River Rch & RM=W100-00-00,W100-00-00_0805 ,184807.6
    6500   10159   12103   17041
River Rch & RM=W100-00-00,W100-00-00_0805 ,182381.6
    6625   10382   12379   17390
River Rch & RM=W100-00-00,W100-00-00_0805 ,178955.5
    6660   10445   12457   17489
River Rch & RM=W100-00-00,W100-00-00_0805 ,177732.9
    6893   10855   12967   18192
River Rch & RM=W100-00-00,W100-00-00_0805 ,175675.6
    6958   10990   13131   18441
River Rch & RM=W100-00-00,W100-00-00_0805 ,169087.1
    6979   11034   13185   18522
River Rch & RM=W100-00-00,W100-00-00_0805 ,167249.9
    6989   11054   13209   18558
River Rch & RM=W100-00-00,W100-00-00_0805 ,166613
    7041   11152   13331   18740
River Rch & RM=W100-00-00,W100-00-00_0805 ,166297.3
    7261   11557   13835   19489
River Rch & RM=W100-00-00,W100-00-00_0805 ,165476.1
    7961   12845   15440   21875
River Rch & RM=W100-00-00,W100-00-00_0805 ,164555.2
    8093   13099   15757   22423
River Rch & RM=W100-00-00,W100-00-00_0805 ,162811.9
    8276   13483   16245   23323
River Rch & RM=W100-00-00,W100-00-00_0805 ,158811.6
    8390   13731   16564   23927
River Rch & RM=W100-00-00,W100-00-00_0805 ,155861.6
    8437   13829   16690   24178
River Rch & RM=W100-00-00,W100-00-00_0805 ,154890.7
    8591   14060   16998   25037
River Rch & RM=W100-00-00,W100-00-00_0805 ,151353.8
    8692   14211   17200   25603
River Rch & RM=W100-00-00,W100-00-00_0805 ,150358.8
    8798   14370   17412   26196
River Rch & RM=W100-00-00,W100-00-00_0805 ,148795.4
    8840   14434   17497   26433
River Rch & RM=W100-00-00,W100-00-00_0805 ,138607.9
    8717   14271   17455   25943
River Rch & RM=W100-00-00,W100-00-00_0805 ,128104.6
    8588   14103   17411   25433
River Rch & RM=W100-00-00,W100-00-00_0805 ,123658.2
    8535   14033   17393   25223
River Rch & RM=W100-00-00,W100-00-00_0805 ,110200.2
   38441   51660   59250   80561
River Rch & RM=W100-00-00,W100-00-00_0805 ,107179.4
   38563   51891   59499   80918
River Rch & RM=W100-00-00,W100-00-00_0805 ,99992.6
   38910   52550   60210   81937
River Rch & RM=W100-00-00,W100-00-00_0805 ,94280.7
   39073   52860   60545   82417
River Rch & RM=W100-00-00,W100-00-00_0805 ,92795.6
   39136   52981   60674   82603
River Rch & RM=W100-00-00,W100-00-00_0805 ,89918.4
   39246   53189   60900   82925
River Rch & RM=W100-00-00,W100-00-00_0805 ,83635.7
   39496   53663   61411   83658
River Rch & RM=W100-00-00,W100-00-00_0805 ,80903.1
   39606   53872   61636   83981
Boundary for River Rch & Prof#=W100-00-00,W100-00-00_0805 , 1
Up Type= 0
Dn Type= 3
Dn Slope=.00015
Boundary for River Rch & Prof#=W100-00-00,W100-00-00_0805 , 2
Up Type= 0
Dn Type= 3
Dn Slope=.00015
Boundary for River Rch & Prof#=W100-00-00,W100-00-00_0805 , 3
Up Type= 0
Dn Type= 3
Dn Slope=.00015
Boundary for River Rch & Prof#=W100-00-00,W100-00-00_0805 , 4
Up Type= 0
Dn Type= 3
Dn Slope=.00015
DSS Import GetInterval= 0
DSS Import GetPeak= 0
DSS Import FillOption= 0

--- W100-00-00.f02 (steady flow) ---

Flow Title=Effective Floodway 2007
Version=Version 3.0.1  May 2012
Number of Profiles= 2
Profile Names=1PCT_100yr,1PCT_Floodway_100yr
River Rch & RM=W100-00-00,W100-00-00_0805 ,248647.7
    3803    3803
River Rch & RM=W100-00-00,W100-00-00_0805 ,247502
    3797    3797
River Rch & RM=W100-00-00,W100-00-00_0805 ,245413.7
    3784    3784
River Rch & RM=W100-00-00,W100-00-00_0805 ,243452.9
    3772    3772
River Rch & RM=W100-00-00,W100-00-00_0805 ,241079
    3758    3758
River Rch & RM=W100-00-00,W100-00-00_0805 ,239993.6
    6670    6670
River Rch & RM=W100-00-00,W100-00-00_0805 ,236611
    6923    6923
River Rch & RM=W100-00-00,W100-00-00_0805 ,234807.9
    7139    7139
River Rch & RM=W100-00-00,W100-00-00_0805 ,232816.9
    7254    7254
River Rch & RM=W100-00-00,W100-00-00_0805 ,231798
    7344    7344
River Rch & RM=W100-00-00,W100-00-00_0805 ,230908
    7549    7549
River Rch & RM=W100-00-00,W100-00-00_0805 ,228917.1
    7745    7745
River Rch & RM=W100-00-00,W100-00-00_0805 ,227144.7
    7870    7870
River Rch & RM=W100-00-00,W100-00-00_0805 ,225979.2
    8117    8117
River Rch & RM=W100-00-00,W100-00-00_0805 ,224981.6
    8422    8422
River Rch & RM=W100-00-00,W100-00-00_0805 ,223061.1
    8606    8606
River Rch & RM=W100-00-00,W100-00-00_0805 ,221523.4
    8675    8675
River Rch & RM=W100-00-00,W100-00-00_0805 ,220426.4
    8930    8930
River Rch & RM=W100-00-00,W100-00-00_0805 ,217899.8
    9096    9096
River Rch & RM=W100-00-00,W100-00-00_0805 ,215022.5
    9264    9264
River Rch & RM=W100-00-00,W100-00-00_0805 ,214669.3
    9299    9299
River Rch & RM=W100-00-00,W100-00-00_0805 ,213687.7
    9467    9467
River Rch & RM=W100-00-00,W100-00-00_0805 ,211631.3
    9600    9600
River Rch & RM=W100-00-00,W100-00-00_0805 ,209864.1
    9809    9809
River Rch & RM=W100-00-00,W100-00-00_0805 ,205679.6
    9914    9914
River Rch & RM=W100-00-00,W100-00-00_0805 ,203658.9
   10276   10276
River Rch & RM=W100-00-00,W100-00-00_0805 ,201783.6
   10489   10489
River Rch & RM=W100-00-00,W100-00-00_0805 ,200076.4
   10859   10859
River Rch & RM=W100-00-00,W100-00-00_0805 ,199440.6
   11113   11113
River Rch & RM=W100-00-00,W100-00-00_0805 ,196182.3
   11262   11262
River Rch & RM=W100-00-00,W100-00-00_0805 ,195567.4
   11407   11407
River Rch & RM=W100-00-00,W100-00-00_0805 ,192820.3
   11699   11699
River Rch & RM=W100-00-00,W100-00-00_0805 ,188903.7
   11852   11852
River Rch & RM=W100-00-00,W100-00-00_0805 ,184807.6
   12103   12103
River Rch & RM=W100-00-00,W100-00-00_0805 ,182381.6
   12379   12379
River Rch & RM=W100-00-00,W100-00-00_0805 ,178955.5
   12457   12457
River Rch & RM=W100-00-00,W100-00-00_0805 ,177732.9
   12967   12967
River Rch & RM=W100-00-00,W100-00-00_0805 ,175675.6
   13131   13131
River Rch & RM=W100-00-00,W100-00-00_0805 ,169087.1
   13185   13185
River Rch & RM=W100-00-00,W100-00-00_0805 ,167249.9
   13209   13209
River Rch & RM=W100-00-00,W100-00-00_0805 ,166613
   13331   13331
River Rch & RM=W100-00-00,W100-00-00_0805 ,166297.3
   13835   13835
River Rch & RM=W100-00-00,W100-00-00_0805 ,165476.1
   15440   15440
River Rch & RM=W100-00-00,W100-00-00_0805 ,164555.2
   15757   15757
River Rch & RM=W100-00-00,W100-00-00_0805 ,162811.9
   16245   16245
River Rch & RM=W100-00-00,W100-00-00_0805 ,158811.6
   16564   16564
River Rch & RM=W100-00-00,W100-00-00_0805 ,155861.6
   16690   16690
River Rch & RM=W100-00-00,W100-00-00_0805 ,154890.7
   16998   16998
River Rch & RM=W100-00-00,W100-00-00_0805 ,151353.8
   17200   17200
River Rch & RM=W100-00-00,W100-00-00_0805 ,150358.8
   17412   17412
River Rch & RM=W100-00-00,W100-00-00_0805 ,148795.4
   17497   17497
River Rch & RM=W100-00-00,W100-00-00_0805 ,138607.9
   17455   17455
River Rch & RM=W100-00-00,W100-00-00_0805 ,128104.6
   17411   17411
River Rch & RM=W100-00-00,W100-00-00_0805 ,123658.2
   17393   17393
River Rch & RM=W100-00-00,W100-00-00_0805 ,110200.2
   59250   59250
River Rch & RM=W100-00-00,W100-00-00_0805 ,107179.4
   59499   59499
River Rch & RM=W100-00-00,W100-00-00_0805 ,99992.6
   60210   60210
River Rch & RM=W100-00-00,W100-00-00_0805 ,94280.7
   60545   60545
River Rch & RM=W100-00-00,W100-00-00_0805 ,92795.6
   60674   60674
River Rch & RM=W100-00-00,W100-00-00_0805 ,89918.4
   60900   60900
River Rch & RM=W100-00-00,W100-00-00_0805 ,83635.7
   61411   61411
River Rch & RM=W100-00-00,W100-00-00_0805 ,80903.1
   61636   61636
Boundary for River Rch & Prof#=W100-00-00,W100-00-00_0805 , 1
Up Type= 0
Dn Type= 3
Dn Slope=.00015
Boundary for River Rch & Prof#=W100-00-00,W100-00-00_0805 , 2
Up Type= 0
Dn Type= 1
Dn Known WS=8.03
DSS Import GetInterval= 0
DSS Import GetPeak= 0
DSS Import FillOption= 0

--- W100-00-00.g01 (geometry) ---

Geom Title=W100-00-00 2021
Version=Version 3.0.1  May 2012

River Reach=W100-00-00      ,W100-00-00_0805
Reach XY= 30
 3033048.000029613842619.9999692 3038982.2499721 13844268.999952
 3043219.210002113839694.1298367 3050273.489856813839498.5600179
 3053829.5001332 13842295.999961 3056745.249879113840566.0001402
 3060842.249887213840864.9998703 3064401.049856213837561.8201249
 3068993.999987913836613.9998421 3069714.159964913835043.7998985
 3071814.749923813835959.9998378 3073199.199910813834022.4600777
 3076604.249859213835473.0001556 3077234.8299629 13839707.820098
 3084755.4399216 13845549.709989 3090591.750099413843666.9998437
 3092167.999899613840702.9998662 3096012.500084613838814.0000353
 3098267.499839713840921.0000864 3101492.350017313841389.1100425
 3102609.750013413840004.9999499 3106405.749967413842170.9998829
 3119075.070101113842125.2401319 3123224.739951413843698.1300308
 3125158.240021413842643.1298442 3127190.0000655 13844300.999888
 3127554.249993113842768.0000013 3131879.690161113841553.8898967
  3143150.249969 13840316.999982 3144765.930136613837956.7701224

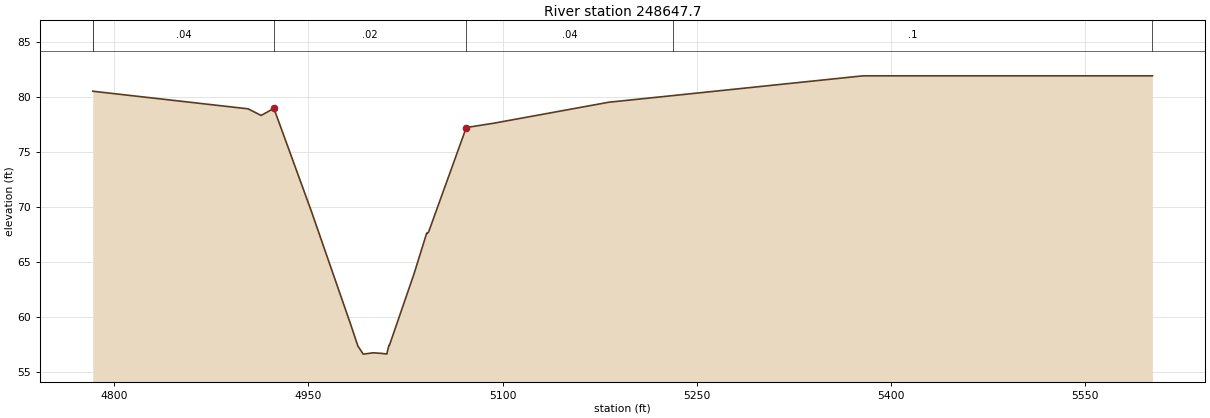
Type RM Length L Ch R = 1 ,248647.7,95.9,99.9,136.8
BEGIN DESCRIPTION:
Cross Section 248647.7-Interpolated
END DESCRIPTION:
XS GIS Cut Line= 4
      3033112.45     13842822.89      3033014.25     13842436.64
      3033014.25     13842240.25      3033033.89     13842017.67
#Sta/Elev= 26
  4783.4    80.5  4903.4    78.9  4913.4    78.3  4923.3   78.94  4952.3   69.57
  4982.7   59.27  4988.1   57.37  4988.2   57.34  4992.3   56.61  4999.9   56.73
  5006.2   56.68  5010.5   56.62  5011.8   57.26  5012.1    57.4  5012.5   57.41
  5031.5    63.9  5041.3   67.61  5041.8   67.58  5042.8   67.72  5071.6   77.11
  5071.9    77.2  5093.4    77.6  5181.9    79.5  5231.9   80.11  5378.3    81.9
  5601.8    81.9
#Mann= 6 ,-1 , 0
  4783.4      .2       0  4783.4     .04       0  4923.3     .02       0
  5071.9     .04       0  5231.9      .1       0  5601.8      .2       0
Bank Sta=4923.3,5071.9
XS Rating Curve= 0
Exp/Cntr=.5,.3