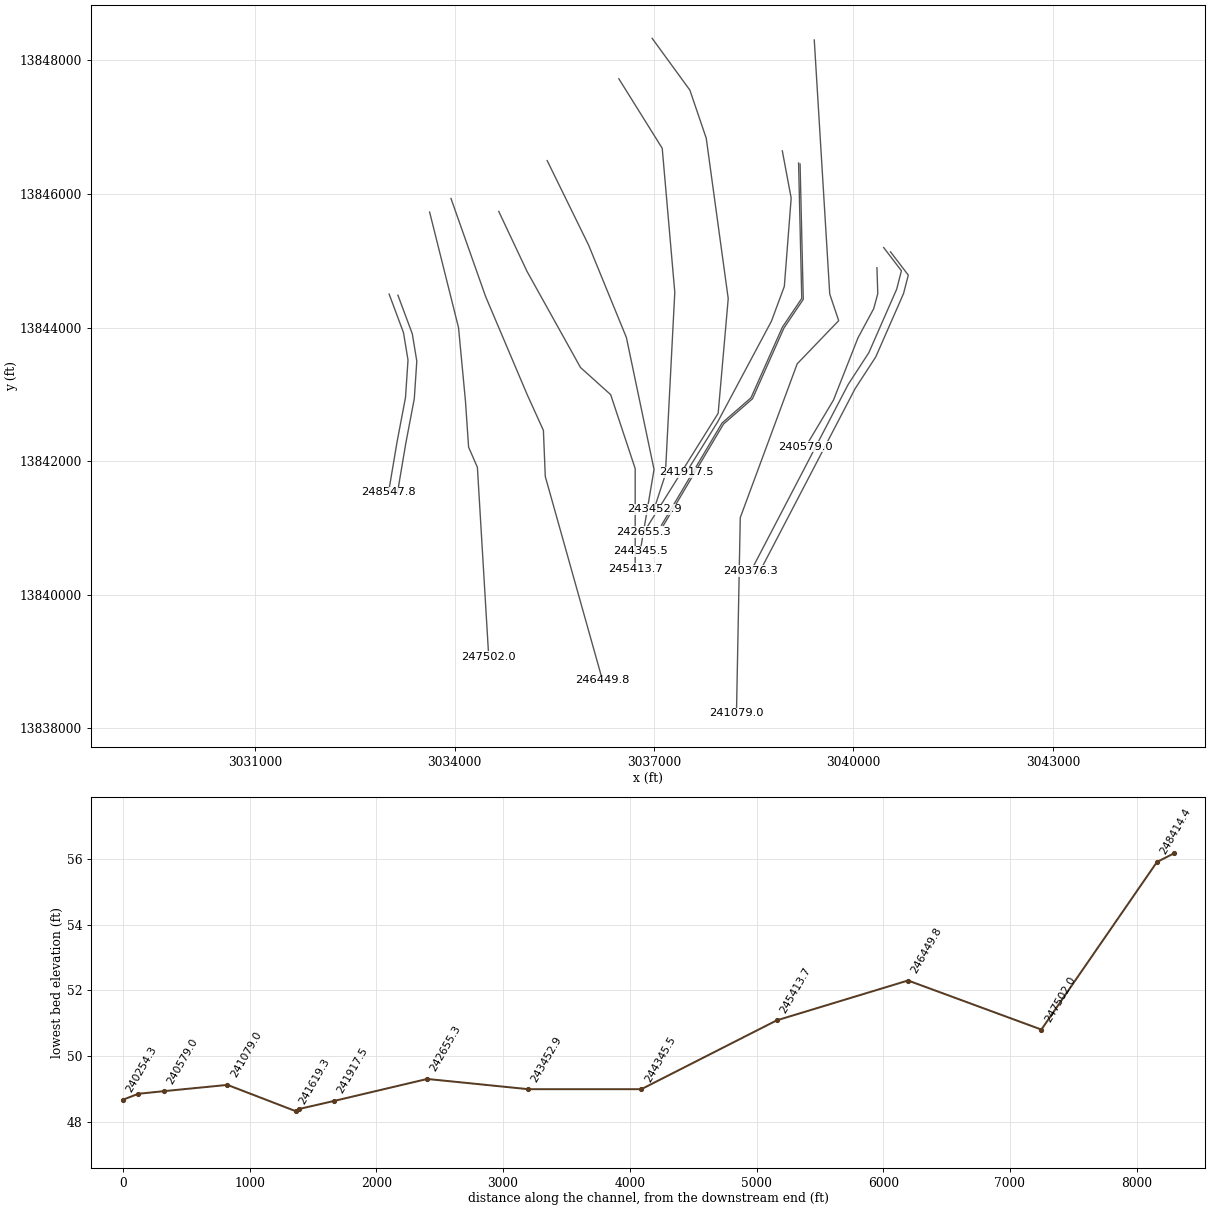
HEC-RAS study W100-00-00.prj: W100-00-00

--- W100-00-00.g01 (geometry) --- (continued)

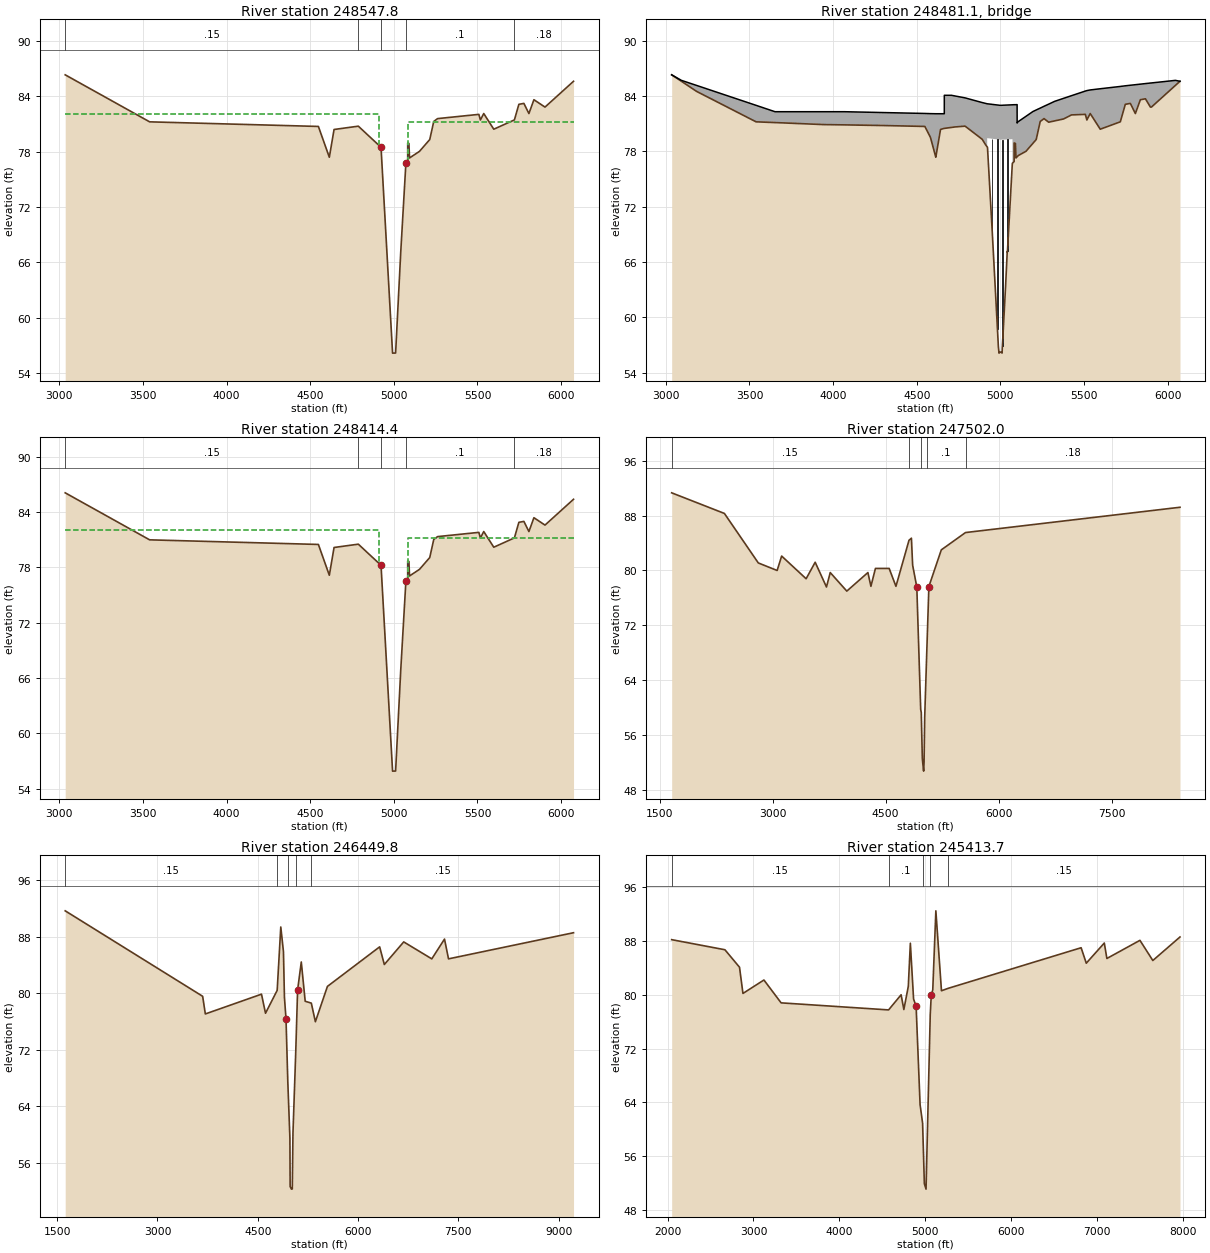
Type RM Length L Ch R = 1 ,248547.8,133.4,133.4,133.4
BEGIN DESCRIPTION:
Upstream Section of Bridge/Culvert/Weir
END DESCRIPTION:
XS GIS Cut Line= 6
      3033013.07     13844500.53      3033229.46     13843922.01
      3033297.17     13843513.13      3033259.33     13842951.33
      3033131.78     13842284.36      3033004.14     13841530.72
#Sta/Elev= 30
  3035.1   86.35  3539.8   81.25  4548.8   80.75  4614.2   77.41  4642.5   80.42
  4787.5   80.78  4923.3   78.49  4992.3   56.16  5010.5   56.17  5041.3   67.16
  5071.9   76.75  5082.7   76.94  5082.9   78.96  5090.1    78.9  5093.6   77.33
  5153.3   78.05  5214.6   79.33  5238.5   81.29  5261.4    81.6  5508.2   82.06
  5517.4   81.45  5537.4   82.15  5597.4   80.45  5720.7   81.46  5747.4   83.15
  5777.4   83.25  5807.4   82.15  5837.4   83.65  5903.6   82.85  6074.2   85.65
#Mann= 5 ,-1 , 0
  3035.1     .15       0  4787.5     .08       0  4923.3     .04       0
  5071.9      .1       0  5720.7     .18       0
#XS Ineff= 2 , 0
            4910    82.1    5082            81.2
Permanent Ineff=
       F       F
Bank Sta=4923.3,5071.9
XS Rating Curve= 0
Exp/Cntr=.5,.3

Type RM Length L Ch R = 3 ,248481.1,,,
BEGIN DESCRIPTION:
STATE HIGHWAY 6
Structure ID: WOO-83
END DESCRIPTION:
Bridge Culvert--1,0,-1,-1, 0
Deck Dist Width WeirC Skew NumUp NumDn MinLoCord MaxHiCord MaxSubmerge Is_Ogee
10,113.4,2.6,0, 50, 50, , , .95, 0, 1,1,,
  3035.1  3093.3  3184.3  3539.8  3652.8  4067.2  4548.8  4582.3  4614.2  4642.5
 4664.99  4665.1  4707.6  4789.4    4892 4921.41  4921.5  4999.9 5072.39  5072.5
  5082.7  5082.9  5090.1  5093.6  5100.4 5100.51  5104.4  5153.3  5194.9  5214.6
  5238.5  5261.4    5289  5324.1    5378  5425.5  5508.2  5517.4  5537.4  5597.4
  5717.4  5747.4  5777.4  5807.4  5837.4  5867.4  5897.4  5903.6  6046.8  6074.2
    86.3    85.7   85.15   82.99    82.3    82.3   82.11   82.09   82.08   82.08
   82.08   84.08   84.08    83.8   83.29   83.16   83.16   82.99   83.05   83.05
   83.06   83.06   83.06   83.06   83.07   81.07   81.19    81.8   82.32   82.49
   82.69   82.89   83.12   83.42   83.75   84.04   84.54   84.59   84.66   84.79
   85.04   85.11   85.17   85.23   85.29   85.35   85.41   85.42    85.7    85.6
    86.3    85.6    84.5    81.2   81.12   80.87    80.7   79.51   77.36   80.37
   80.49   80.49   80.59   80.73    79.3   78.48   79.43   79.26   79.32   76.71
   76.89   78.91   78.85   77.28   77.41   77.41   77.48      78   78.87   79.28
   81.24   81.55   81.16    81.3   81.51   81.95   82.01    81.4    82.1    80.4
    81.2    83.1    83.2    82.1    83.6    83.7    82.8    82.8   85.15    85.6
  3035.1  3093.3  3184.3  3539.8  3652.8  4067.2  4548.8  4582.3  4614.2  4642.5
 4664.99  4665.1  4707.6  4789.4    4892 4921.41  4921.5  4999.9 5072.39  5072.5
  5082.7  5082.9  5090.1  5093.6  5100.4 5100.51  5104.4  5153.3  5194.9  5214.6
  5238.5  5261.4    5289  5324.1    5378  5425.5  5508.2  5517.4  5537.4  5597.4
  5717.4  5747.4  5777.4  5807.4  5837.4  5867.4  5897.4  5903.6  6046.8  6074.2
    86.3    85.7   85.15   82.99    82.3    82.3   82.11   82.09   82.08   82.08
   82.08   84.08   84.08    83.8   83.29   83.16   83.16   82.99   83.05   83.05
   83.06   83.06   83.06   83.06   83.07   81.07   81.19    81.8   82.32   82.49
   82.69   82.89   83.12   83.42   83.75   84.04   84.54   84.59   84.66   84.79
   85.04   85.11   85.17   85.23   85.29   85.35   85.41   85.42    85.7    85.6
   86.15   85.45   84.35   81.05   80.97   80.72   80.55   79.36   77.21   80.22
   80.34   80.34   80.44   80.58   79.15   78.33   79.28   79.11   79.17   76.56
   76.74   78.76    78.7   77.13   77.26   77.26   77.33   77.85   78.72   79.13
   81.09    81.4   81.01   81.15   81.36    81.8   81.86   81.25   81.95   80.25
   81.05   82.95   83.05   81.95   83.45   83.55   82.65   82.65      85   85.45
Pier Skew, UpSta & Num, DnSta & Num=  ,4952.3, 2 ,4952.3, 2 , 0 , 0 , 0 ,,
     1.4     1.4
   67.83   80.37
     1.4     1.4
   67.68   80.22
Pier Skew, UpSta & Num, DnSta & Num=  ,4982.7, 2 ,4982.7, 2 , 0 , 0 , 0 ,,
     1.4     1.4
   57.52    80.3
     1.4     1.4
   57.37   80.15
Pier Skew, UpSta & Num, DnSta & Num=  ,5012.5, 2 ,5012.5, 2 , 0 , 0 , 0 ,,
     1.4     1.4
   55.76   80.27
     1.4     1.4
   55.61   80.12
Pier Skew, UpSta & Num, DnSta & Num=  ,5042.8, 2 ,5042.8, 2 , 0 , 0 , 0 ,,
     1.4     1.4
   66.12   80.29
     1.4     1.4
   65.97   80.14
Abutment Skew #Up #Dn= , 2 , 2
  4921.3  4988.1
   79.43   56.87
  4921.3  4988.1
   79.28   56.72
BR Coef= 1 , 1 , 0 ,1.25, 0 ,,,.8,0,2,0,
WSPro=,,,, 1 ,,,, 0 ,,,, 0 ,,,,-1 ,-1 ,-1 , 0 , 0 , 0 , 0 , 0
BR U #Sta/Elev= 86
  3035.1    86.3  3093.3    85.6  3184.3    84.5  3539.8    81.2  3652.8   81.12
  3946.5    80.9  4067.2   80.87  4297.6    80.8  4548.8    80.7  4582.3   79.51
  4614.2   77.36  4614.9   77.43  4642.5   80.37    4662   80.48 4664.99   80.49
  4665.1   80.49 4665.21   80.49  4707.6   80.59  4726.7   80.64  4740.2   80.66
  4787.5   80.73  4789.4   80.73  4819.1   80.32    4892    79.3  4912.7   78.69
  4912.8   78.69 4921.41   78.48  4921.5   78.48  4923.3   78.44  4952.3   69.07
  4982.7   58.77    4988   56.91  4988.1   56.87  4988.2   56.84  4992.3   56.11
  4999.9   56.23  5001.5   56.22  5006.2   56.18  5010.5   56.12  5011.8   56.76
  5012.1    56.9  5012.5   56.91  5031.5    63.4  5041.3   67.11  5041.8   67.08
  5042.8   67.22  5071.5   76.61  5071.6   76.63  5071.9    76.7 5072.39   76.71
  5072.5   76.71  5082.7   76.89  5082.9   78.91  5090.1   78.85  5093.6   77.28
 5100.29   77.41  5100.4   77.41 5100.51   77.41  5104.4   77.48  5107.9   77.55
  5153.3      78  5194.9   78.87  5214.6   79.28  5238.5   81.24  5261.4   81.55
    5289   81.16  5324.1    81.3    5378   81.51  5425.5   81.95  5508.2   82.01
  5517.4    81.4  5523.6   81.62  5537.4    82.1  5597.4    80.4  5717.4    81.2
  5720.7   81.41  5747.4    83.1  5777.4    83.2  5790.7   82.71  5807.4    82.1
  5837.4    83.6  5867.4    83.7  5897.4    82.8  5903.6    82.8  6046.8   85.15
  6074.2    85.6
BR U #Mann= 5
  3035.1     .15  4787.5     .08  4923.3     .04  5071.9      .1  5720.7     .18
BR U Banks=4923.3,5071.9
BR D #Sta/Elev= 86
  3035.1   86.15  3093.3   85.45  3184.3   84.35  3539.8   81.05  3652.8   80.97
  3946.5   80.75  4067.2   80.72  4297.6   80.65  4548.8   80.55  4582.3   79.36
  4614.2   77.21  4614.9   77.28  4642.5   80.22    4662   80.33 4664.99   80.34
  4665.1   80.34 4665.21   80.34  4707.6   80.44  4726.7   80.49  4740.2   80.51
  4787.5   80.58  4789.4   80.58  4819.1   80.17    4892   79.15  4912.7   78.54
  4912.8   78.54 4921.41   78.33  4921.5   78.33  4923.3   78.29  4952.3   68.92
  4982.7   58.62    4988   56.76  4988.1   56.72  4988.2   56.69  4992.3   55.96
  4999.9   56.08  5001.5   56.07  5006.2   56.03  5010.5   55.97  5011.8   56.61
  5012.1   56.75  5012.5   56.76  5031.5   63.25  5041.3   66.96  5041.8   66.93
  5042.8   67.07  5071.5   76.46  5071.6   76.48  5071.9   76.55 5072.39   76.56
  5072.5   76.56  5082.7   76.74  5082.9   78.76  5090.1    78.7  5093.6   77.13
 5100.29   77.26  5100.4   77.26 5100.51   77.26  5104.4   77.33  5107.9    77.4
  5153.3   77.85  5194.9   78.72  5214.6   79.13  5238.5   81.09  5261.4    81.4
    5289   81.01  5324.1   81.15    5378   81.36  5425.5    81.8  5508.2   81.86
  5517.4   81.25  5523.6   81.47  5537.4   81.95  5597.4   80.25  5717.4   81.05
  5720.7   81.26  5747.4   82.95  5777.4   83.05  5790.7   82.56  5807.4   81.95
  5837.4   83.45  5867.4   83.55  5897.4   82.65  5903.6   82.65  6046.8      85
  6074.2   85.45
BR D #Mann= 5
  3035.1     .15  4787.5     .08  4923.3     .04  5071.9      .1  5720.7     .18
BR D Banks=4923.3,5071.9
BC Design=,, 0 ,, 0 ,,,,,,
BC HTab HWMax=86.35

Type RM Length L Ch R = 1 ,248414.4,912.4,912.4,912.4
BEGIN DESCRIPTION:
Downstream Section of Bridge/Culvert/Weir
END DESCRIPTION:
XS GIS Cut Line= 6
      3033145.44     13844483.97      3033361.82     13843905.45
      3033429.53     13843496.57      3033391.69     13842934.77
      3033264.14      13842267.8      3033136.51     13841514.15
#Sta/Elev= 30
  3035.1   86.09  3539.8   80.99  4548.8   80.49  4614.2   77.15  4642.5   80.16
  4787.5   80.52  4923.3   78.23  4992.3    55.9  5010.5   55.91  5041.3    66.9
  5071.9   76.49  5082.7   76.68  5082.9    78.7  5090.1   78.64  5093.6   77.07
  5153.3   77.79  5214.6   79.07  5238.5   81.03  5261.4   81.34  5508.2    81.8
  5517.4   81.19  5537.4   81.89  5597.4   80.19  5720.7    81.2  5747.4   82.89
  5777.4   82.99  5807.4   81.89  5837.4   83.39  5903.6   82.59  6074.2   85.39
#Mann= 5 ,-1 , 0
  3035.1     .15       0  4787.5     .08       0  4923.3     .04       0
  5071.9      .1       0  5720.7     .18       0
#XS Ineff= 2 , 0
            4910    82.1    5082            81.2
Permanent Ineff=
       F       F
Bank Sta=4923.3,5071.9
XS Rating Curve= 0
Exp/Cntr=.5,.3

Type RM Length L Ch R = 1 ,247502.0,1025.1,1052.2,1074.7
BEGIN DESCRIPTION:
Cross Section 247502.0
END DESCRIPTION:
XS GIS Cut Line= 6
      3033622.24     13845728.73      3034057.36     13843997.68
      3034161.42     13842900.41      3034208.71     13842209.89
      3034341.14     13841907.19      3034511.41     13839074.14
#Sta/Elev= 30
  1661.1    91.3  2361.1    88.3  2811.1    81.1  3061.1      80  3121.1    82.1
    3446    78.8    3566    81.2    3716    77.6    3766    79.7    3986      77
    4266    79.7    4306    77.7    4366    80.3  4548.2    80.3  4638.2    77.7
  4811.7    84.4  4843.7    84.7  4859.8   80.78  4915.1    77.6  4966.7   59.81
  4974.2   59.35  4988.4   52.63  5005.7   50.81  5011.5   52.08  5019.9   58.63
  5045.5   67.48  5075.5   77.67  5240.3      83  5561.7   85.52  8408.9    89.2
#Mann= 5 ,-1 , 0
  1661.1     .15       0  4811.7      .1       0  4966.7     .05       0
  5045.5      .1       0  5561.7     .18       0
Bank Sta=4915.1,5075.5
XS Rating Curve= 0
Exp/Cntr=.3,.1

Type RM Length L Ch R = 1 ,246449.8,1001.9,1036.1,1062.7
BEGIN DESCRIPTION:
Cross Section 246449.8
END DESCRIPTION:
XS GIS Cut Line= 6
      3033943.85      13845932.1      3034464.11     13844465.92
      3035088.42     13842999.73      3035334.36     13842460.56
      3035362.74     13841770.03      3036223.53     13838719.42
#Sta/Elev= 30
  1619.8    91.7  3675.6    79.6  3715.6    77.1  4555.6    79.9  4615.6    77.2
  4790.2   80.44  4844.2   89.41    4884   85.93  4898.8   79.45  4922.3   76.39
  4949.4   67.43  4980.5   59.54  4984.1   52.67  5003.3    52.3    5016   52.32
  5026.3   60.22  5067.9   71.73  5095.7   80.49  5150.8   84.46  5209.1    78.9
  5300.8   78.63  5361.7      76  5541.7      81  6322.8    86.6  6392.8    84.1
  6682.8    87.3  7102.8    84.9  7292.8    87.7  7352.8    84.9  9222.6    88.6
#Mann= 5 ,-1 , 0
  1619.8     .15       0  4790.2      .1       0  4949.4     .05       0
  5067.9      .1       0  5300.8     .15       0
Bank Sta=4922.3,5095.7
XS Rating Curve= 0
Exp/Cntr=.3,.1

Type RM Length L Ch R = 1 ,245413.7,1102.8,1068.2,1027.4
BEGIN DESCRIPTION:
Cross Section 245413.7
END DESCRIPTION:
XS GIS Cut Line= 6
      3034662.76     13845738.18      3035088.42     13844839.56
      3035892.46     13843401.75       3036346.5       13842995.
      3036715.41     13841888.27      3036715.41     13840388.98
#Sta/Elev= 30
  2047.8    88.2  2667.8    86.7  2837.8    84.1  2877.8    80.2  3122.1    82.2
  3322.1    78.8  4573.7   77.75  4719.5      80  4751.5   77.81  4803.4   81.26
  4827.2   87.67  4864.8   79.36  4894.2   78.31  4940.5   63.66  4969.9   60.88
  4990.2   51.91  5009.8   51.09  5058.8   77.06  5070.5   79.92  5088.2   80.74
  5124.2   92.49  5189.5    80.6  5267.9   80.96  6815.7      87  6875.7    84.7
  7085.7    87.7  7115.7    85.4  7500.7    88.1  7650.7    85.1  7967.1    88.6
#Mann= 5 ,-1 , 0
  2047.8     .15       0  4573.7      .1       0  4969.9     .05       0
  5058.8      .1       0  5267.9     .15       0
Bank Sta=4894.2,5070.5
XS Rating Curve= 0
Exp/Cntr=.3,.1

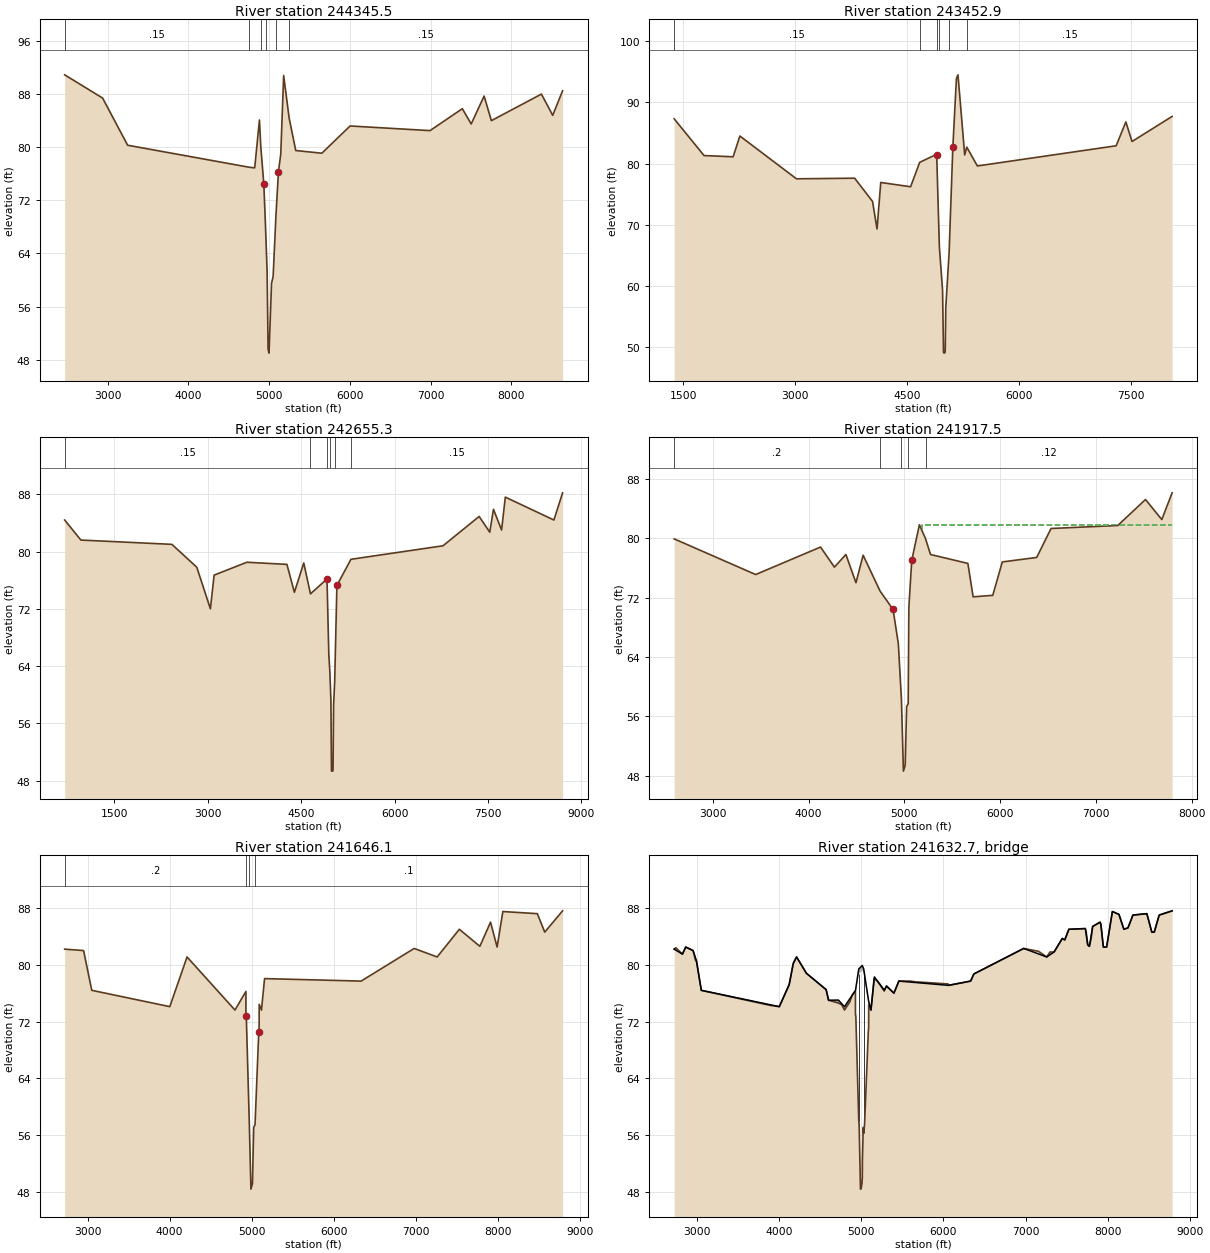
Type RM Length L Ch R = 1 ,244345.5,917.1,892.6,881.1
BEGIN DESCRIPTION:
Cross Section 244345.5
END DESCRIPTION:
XS GIS Cut Line= 5
      3035391.12     13846499.65      3036015.43     13845232.11
      3036582.98     13843851.06      3036999.19     13841874.08
      3036791.09     13840649.11
#Sta/Elev= 30
  2467.5    90.9  2937.5    87.4  3247.5    80.3  4747.5      77  4821.7   76.89
  4880.4    84.1  4897.5   80.05  4935.1   74.39  4955.7   68.06  4975.4   61.35
  4987.7   49.55  4999.3      49  5030.3   59.55  5049.9   60.51  5085.1   69.75
  5116.1   76.33  5144.4   78.95  5180.4    90.8  5248.4   84.39  5330.4    79.5
  5653.6    79.1  6003.6    83.2  6993.6    82.5  7393.9    85.8  7503.9    83.5
  7663.9    87.7  7753.9      84  8373.9      88  8513.9    84.8  8636.4    88.5
#Mann= 6 ,-1 , 0
  2467.5     .15       0  4747.5      .1       0  4897.5     .15       0
  4955.7     .05       0  5085.1      .1       0  5248.4     .15       0
Bank Sta=4935.1,5116.1
XS Rating Curve= 0
Exp/Cntr=.3,.1

Type RM Length L Ch R = 1 ,243452.9,806.5,797.6,793.4
BEGIN DESCRIPTION:
Cross Section 243452.9
END DESCRIPTION:
XS GIS Cut Line= 5
      3036469.47     13847724.63      3037122.16     13846684.11
      3037311.35      13844527.4      3037169.46     13841798.41
      3036999.19     13841278.15
#Sta/Elev= 30
  1379.3    87.3  1779.3    81.3  2169.3    81.1  2259.3    84.5  3017.6    77.5
  3797.6    77.6  4037.6    73.8  4097.6    69.3  4147.6    76.9  4547.6    76.2
  4669.3   80.19  4894.8    81.5  4897.5   81.35  4933.2    66.4  4975.9   59.27
  4988.7   49.09  4998.8      49  5011.3   49.16    5019   56.46  5063.6   65.41
  5113.5   82.64  5161.5   93.87  5182.6    94.5  5272.6    81.4  5300.1   82.68
  5442.6    79.6  7302.6    82.9  7432.6    86.8  7515.3    83.6  8052.7    87.7
#Mann= 6 ,-1 , 0
  1379.3     .15       0  4669.3     .08       0  4894.8     .15       0
  4933.2     .05       0  5063.6      .1       0  5300.1     .15       0
Bank Sta=4897.5,5113.5
XS Rating Curve= 0
Exp/Cntr=.3,.1

Type RM Length L Ch R = 1 ,242655.3,770.8,737.8,718.4
BEGIN DESCRIPTION:
Cross Section 242655.3
END DESCRIPTION:
XS GIS Cut Line= 6
      3036970.81     13848330.02      3037538.37     13847554.36
      3037784.31     13846835.46      3038115.38     13844432.81
      3037964.03     13842715.95      3036847.84     13840937.62
#Sta/Elev= 30
   704.8    84.4   964.8    81.6  2425.7      81  2825.7    77.8  3043.8      72
  3103.8    76.7  3629.8    78.5  4272.4    78.2  4392.4    74.3  4542.4    78.4
  4650.3   74.08  4914.8   76.16  4915.9   76.16  4944.4   65.72    4962    63.1
  4978.5   59.18  4987.7   49.31  5012.3   49.34  5021.5   58.53    5039   61.82
  5074.6   75.25  5299.9   78.91  6778.2    80.8  7358.2    84.9  7528.2    82.7
  7588.2    85.9  7718.2      83  7778.2    87.6  8558.2    84.4  8697.8    88.2
#Mann= 6 ,-1 , 0
   704.8     .15       0  4650.3      .1       0  4914.8     .15       0
    4962    .055       0    5039     .08       0  5299.9     .15       0
Bank Sta=4915.9,5074.6
XS Rating Curve= 0
Exp/Cntr=.3,.1

Type RM Length L Ch R = 1 ,241917.5,270.9,271.4,228.6
BEGIN DESCRIPTION:
Cross Section 241917.5 - Interpolated
END DESCRIPTION:
XS GIS Cut Line= 6
      3038929.17     13846645.52      3039062.57     13845937.47
      3038959.55     13844616.41      3038765.63     13844095.26
      3037959.67     13842592.42        3037487.     13841834.93
#Sta/Elev= 30
  2596.2    79.9  3446.7    75.1  4124.3    78.8  4269.3    76.1  4389.3    77.8
  4494.3      74  4569.3    77.7  4746.4   72.87  4881.8    70.4  4936.8    65.8
  4969.3   58.27  4989.9   48.64  5008.6   49.45  5023.6   57.32  5039.7   57.73
  5046.8    70.7  5076.8      77  5156.8    81.8  5221.1   79.92  5272.9    77.8
  5662.9    76.6  5717.9    72.1  5922.9    72.3  6022.9    76.8  6381.8    77.4
  6531.8    81.3  7228.2    81.7  7518.2    85.2  7688.2    82.5  7796.1    86.1
#Mann= 5 ,-1 , 0
  2596.2      .2       0  4746.4      .1       0  4969.3     .05       0
  5039.7      .1       0  5221.1     .12       0
#XS Ineff= 2 , 0
                            5180            81.8
Permanent Ineff=
       F       F
Bank Sta=4881.8,5076.8
XS Rating Curve= 0
Exp/Cntr=.5,.3

Type RM Length L Ch R = 1 ,241646.1,26.8,26.8,26.8
BEGIN DESCRIPTION:
Upstream Section of Bridge/Culvert/Weir
END DESCRIPTION:
XS GIS Cut Line= 6
      3039173.91     13846462.74      3039221.94     13844436.19
      3038931.12     13844006.91      3038457.45      13842947.3
      3038022.37      13842570.2      3037110.72     13841040.22
#Sta/Elev= 30
  2721.8   82.21  2951.8   82.01  3051.8   76.41  4001.8   74.11  4211.8   81.11
  4795.6   73.63  4928.5   76.25  4928.8   73.24  4933.7   72.73  4969.3   58.03
  4989.9    48.4  5008.6   49.21  5023.6   57.08  5039.7   57.49  5085.2    70.5
  5089.8    71.4  5090.4   74.44    5118   73.62  5155.8   78.06  6331.8   77.71
  6977.7   82.31  7257.7   81.11  7527.7   85.01  7777.7   82.61  7907.7   86.01
  7987.7   82.51  8057.7   87.51  8477.7   87.21  8567.7   84.61  8785.3   87.61
#Mann= 4 ,-1 , 0
  2721.8      .2       0  4933.7      .1       0  4969.3     .05       0
  5039.7      .1       0
#XS Ineff= 2 , 0
          4928.8   73.23  5089.8           71.39
Permanent Ineff=
       F       F
Bank Sta=4933.7,5085.2
XS Rating Curve= 0
Exp/Cntr=.5,.3

Type RM Length L Ch R = 3 ,241632.7,,,
BEGIN DESCRIPTION:
FOOTBRIDGE
Structure ID: WOO-82
END DESCRIPTION:
Bridge Culvert--1,0,-1,-1, 0
Deck Dist Width WeirC Skew NumUp NumDn MinLoCord MaxHiCord MaxSubmerge Is_Ogee
10,6.8,2.6,0, 60, 60, , , .95, 0, 1,1,,
  2721.8  2821.8  2861.8  2951.8  2991.8  3051.8  4001.8  4121.8  4171.8  4211.8
  4331.8  4571.8  4601.8  4720.6  4795.6  4928.5  4928.8 4929.01  4929.1  4968.9
  5011.9  5029.3  5088.9 5089.09  5089.2  5089.8  5090.4    5118  5159.5    5279
  5307.4  5397.4  5457.4  6061.8  6331.8  6370.3  6977.7  7257.7  7347.7  7447.7
  7477.7  7527.7  7727.7  7757.7  7777.7  7817.7  7907.7  7917.7  7947.7  7987.7
  8057.7  8137.7  8197.7  8247.7  8307.7  8477.7  8537.7  8567.7  8627.7  8785.3
    82.2    81.5    82.5      82    80.6    76.4    74.1    77.2    80.2    81.1
    78.8    76.5      75   75.03    74.1   76.38   76.38   76.38   76.38   79.41
    79.9   79.43   74.92    74.9   74.89   74.87   74.85   73.62   78.29   76.44
   77.01      76    77.7    77.1    77.7    78.7    82.3    81.1    81.8    83.7
    83.5      85    85.1    82.8    82.6    85.4      86    85.7    82.5    82.5
    87.5    87.1      85    85.2      87    87.2    84.6    84.6      87    87.6
    82.2    81.5    82.5      82    80.6    76.4    74.1    77.2    80.2    81.1
    78.8    76.5      75    74.6   73.62   76.24   73.23   73.18   75.68   78.71
    79.2   78.73   74.22    74.2   71.22   71.39   74.43   73.61   78.02    76.3
      77      76    77.7    77.1    77.7    78.7    82.3    81.1    81.8    83.7
    83.5      85    85.1    82.8    82.6    85.4      86    85.7    82.5    82.5
    87.5    87.1      85    85.2      87    87.2    84.6    84.6      87    87.6
  2721.8  2821.8  2861.8  2951.8  2991.8  3051.8  4001.8  4121.8  4171.8  4211.8
  4331.8  4571.8  4601.8  4720.6  4795.6  4928.5  4928.8 4929.01  4929.1  4968.9
  5011.9  5029.3  5088.9 5089.09  5089.2  5089.8  5090.4    5118  5159.5    5279
  5307.4  5397.4  5457.4  6061.8  6331.8  6370.3  6977.7  7257.7  7347.7  7447.7
  7477.7  7527.7  7727.7  7757.7  7777.7  7817.7  7907.7  7917.7  7947.7  7987.7
  8057.7  8137.7  8197.7  8247.7  8307.7  8477.7  8537.7  8567.7  8627.7  8785.3
    82.2    81.5    82.5      82    80.6    76.4    74.1    77.2    80.2    81.1
    78.8    76.5      75   75.03    74.1   76.38   76.38   76.38   76.38   79.41
    79.9   79.43   74.92    74.9   74.89   74.87   74.85   73.62   78.29   76.44
   77.01      76    77.7    77.1    77.7    78.7    82.3    81.1    81.8    83.7
    83.5      85    85.1    82.8    82.6    85.4      86    85.7    82.5    82.5
    87.5    87.1      85    85.2      87    87.2    84.6    84.6      87    87.6
   82.13   81.43   82.43   81.93   80.53   76.33   74.03   77.13   80.13   81.03
   78.73   76.43   74.93   74.53   73.55   76.17   73.16   73.11   75.61   78.64
   79.13   78.66   74.15   74.13   71.15   71.32   74.36   73.54   77.95   76.23
   76.93   75.93   77.63   77.03   77.63   78.63   82.23   81.03   81.73   83.63
   83.43   84.93   85.03   82.73   82.53   85.33   85.93   85.63   82.43   82.43
   87.43   87.03   84.93   85.13   86.93   87.13   84.53   84.53   86.93   87.53
Pier Skew, UpSta & Num, DnSta & Num=  ,4969.3, 2 ,4969.3, 2 , 0 , 0 , 0 ,,
     1.5     1.5
   56.92   79.74
     1.5     1.5
   56.85   79.67
Pier Skew, UpSta & Num, DnSta & Num=  ,5029.1, 2 ,5029.1, 2 , 0 , 0 , 0 ,,
     1.5     1.5
   55.37   79.76
     1.5     1.5
    55.3   79.69
Abutment Skew #Up #Dn= , 2 , 2
  4928.9  4930.1
   75.68   72.95
  4928.9  4930.1
   75.61   72.88
Abutment Skew #Up #Dn= , 2 , 2
  5088.2 5089.29
   70.93    74.2
  5088.2 5089.29
   70.86   74.13
BR Coef= 1 , 1 , 0 ,1.25, 0 ,,,.8,0,2,0,
WSPro=,,,, 1 ,,,, 0 ,,,, 0 ,,,,-1 ,-1 ,-1 , 0 , 0 , 0 , 0 , 0
BR U #Sta/Elev= 117
  2721.8    82.2  2741.8    82.4  2821.8    81.5  2861.8    82.5  2951.8      82
  2981.8    80.6  2991.8    80.6  3051.8    76.4  3881.8    74.3  4001.8    74.1
  4121.8    77.2  4171.8    80.2  4211.8    81.1  4331.8    78.8  4571.8    76.5
  4601.8      75  4719.3   74.61  4720.6    74.6  4746.4   74.46    4762   74.37
  4771.7   74.15  4795.6   73.62  4807.4   73.83  4859.6   74.74  4871.3   75.11
  4891.2   75.75  4894.1   75.84  4928.5   76.24  4928.8   73.23  4928.9   73.21
 4929.01   73.18  4929.1   73.16  4929.4    73.1    4930   72.96  4930.1   72.95
 4930.89    72.9    4931    72.9 4931.11   72.89  4933.7   72.72  4968.9   58.19
  4969.3   58.02    4974   57.42    4987   50.16  4988.5   49.24  4989.9   48.39
  4996.9   48.42  4999.5   48.58  5002.6   48.77  5008.6    49.2  5011.9   49.93
  5012.9   50.15  5013.4   52.34  5023.6   57.07  5029.1   56.29  5029.3   56.31
  5039.7   57.48  5085.2   70.49 5086.79   70.71  5086.9   70.73 5087.11   70.76
  5088.1    70.9  5088.2   70.93  5088.9   71.13 5089.09   71.19  5089.2   71.22
  5089.3   71.25  5089.8   71.39  5090.4   74.43  5098.7   74.08  5099.4   74.06
  5117.6   73.62    5118   73.61  5155.8   78.05  5159.5   78.02    5197   77.69
  5198.7   77.67  5221.1   77.29    5279    76.3  5290.4   76.58  5307.4      77
  5309.1   76.98  5397.4      76  5457.4    77.7  5597.5    77.7  5657.5    77.6
  6057.5    77.3  6061.8    77.1  6331.8    77.7  6370.3    78.7  6977.7    82.3
  7157.7    81.9  7257.7    81.1  7297.7    81.8  7347.7    81.8  7447.7    83.7
  7477.7    83.5  7527.7      85  7727.7    85.1  7737.7    84.8  7757.7    82.8
  7777.7    82.6  7797.7    83.6  7817.7    85.4  7907.7      86  7917.7    85.7
  7947.7    82.5  7987.7    82.5  8057.7    87.5  8137.7    87.1  8197.7      85
  8247.7    85.2  8307.7      87  8477.7    87.2  8537.7    84.6  8567.7    84.6
  8627.7      87  8785.3    87.6
BR U #Mann= 4
  2721.8      .2  4933.7      .1  4969.3     .05  5039.7      .1
BR U Banks=4933.7,5085.2
BR D #Sta/Elev= 117
  2721.8   82.13  2741.8   82.33  2821.8   81.43  2861.8   82.43  2951.8   81.93
  2981.8   80.53  2991.8   80.53  3051.8   76.33  3881.8   74.23  4001.8   74.03
  4121.8   77.13  4171.8   80.13  4211.8   81.03  4331.8   78.73  4571.8   76.43
  4601.8   74.93  4719.3   74.54  4720.6   74.53  4746.4   74.39    4762    74.3
  4771.7   74.08  4795.6   73.55  4807.4   73.76  4859.6   74.67  4871.3   75.04
  4891.2   75.68  4894.1   75.77  4928.5   76.17  4928.8   73.16  4928.9   73.14
 4929.01   73.11  4929.1   73.09  4929.4   73.03    4930   72.89  4930.1   72.88
 4930.89   72.83    4931   72.83 4931.11   72.82  4933.7   72.65  4968.9   58.12
  4969.3   57.95    4974   57.35    4987   50.09  4988.5   49.17  4989.9   48.32
  4996.9   48.35  4999.5   48.51  5002.6    48.7  5008.6   49.13  5011.9   49.86
  5012.9   50.08  5013.4   52.27  5023.6      57  5029.1   56.22  5029.3   56.24
  5039.7   57.41  5085.2   70.42 5086.79   70.64  5086.9   70.66 5087.11   70.69
  5088.1   70.83  5088.2   70.86  5088.9   71.06 5089.09   71.12  5089.2   71.15
  5089.3   71.18  5089.8   71.32  5090.4   74.36  5098.7   74.01  5099.4   73.99
  5117.6   73.55    5118   73.54  5155.8   77.98  5159.5   77.95    5197   77.62
  5198.7    77.6  5221.1   77.22    5279   76.23  5290.4   76.51  5307.4   76.93
  5309.1   76.91  5397.4   75.93  5457.4   77.63  5597.5   77.63  5657.5   77.53
  6057.5   77.23  6061.8   77.03  6331.8   77.63  6370.3   78.63  6977.7   82.23
  7157.7   81.83  7257.7   81.03  7297.7   81.73  7347.7   81.73  7447.7   83.63
  7477.7   83.43  7527.7   84.93  7727.7   85.03  7737.7   84.73  7757.7   82.73
  7777.7   82.53  7797.7   83.53  7817.7   85.33  7907.7   85.93  7917.7   85.63
  7947.7   82.43  7987.7   82.43  8057.7   87.43  8137.7   87.03  8197.7   84.93
  8247.7   85.13  8307.7   86.93  8477.7   87.13  8537.7   84.53  8567.7   84.53
  8627.7   86.93  8785.3   87.53
BR D #Mann= 4
  2721.8      .2  4933.7      .1  4969.3     .05  5039.7      .1
BR D Banks=4933.7,5085.2
BC Design=,, 0 ,, 0 ,,,,,,
BC HTab HWMax=87.61

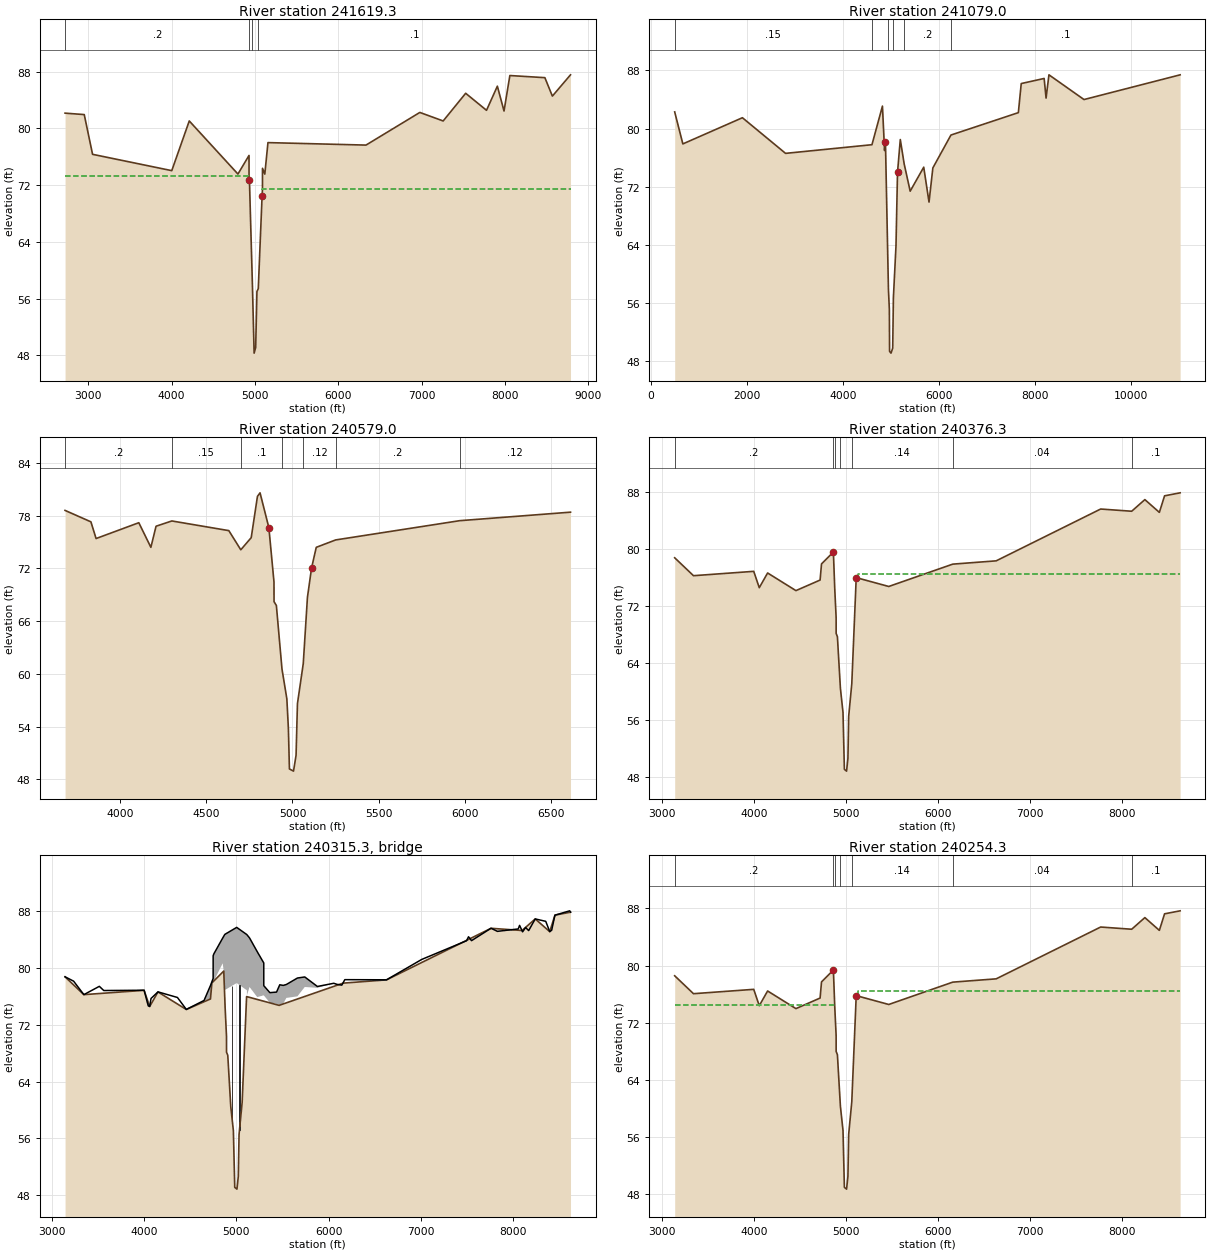
Type RM Length L Ch R = 1 ,241619.3,540.3,540.3,540.3
BEGIN DESCRIPTION:
Downstream Section of Bridge/Culvert/Weir
END DESCRIPTION:
XS GIS Cut Line= 6
      3039196.53     13846448.37      3039244.56     13844421.83
      3038953.74     13843992.55      3038480.07     13842932.94
      3038044.99     13842555.84      3037133.35     13841025.85
#Sta/Elev= 30
  2721.8   82.14  2951.8   81.94  3051.8   76.34  4001.8   74.04  4211.8   81.04
  4795.6   73.56  4928.5   76.18  4928.8   73.17  4933.7   72.66  4969.3   57.96
  4989.9   48.33  5008.6   49.14  5023.6   57.01  5039.7   57.42  5085.2   70.43
  5089.8   71.33  5090.4   74.37    5118   73.55  5155.8   77.99  6331.8   77.64
  6977.7   82.24  7257.7   81.04  7527.7   84.94  7777.7   82.54  7907.7   85.94
  7987.7   82.44  8057.7   87.44  8477.7   87.14  8567.7   84.54  8785.3   87.54
#Mann= 4 ,-1 , 0
  2721.8      .2       0  4933.7      .1       0  4969.3     .05       0
  5039.7      .1       0
#XS Ineff= 2 , 0
          4928.8   73.23  5089.8           71.39
Permanent Ineff=
       F       F
Bank Sta=4933.7,5085.2
XS Rating Curve= 0
Exp/Cntr=.5,.3

Type RM Length L Ch R = 1 ,241079.0,459,500,533.6
BEGIN DESCRIPTION:
Cross Section 241079.0
END DESCRIPTION:
XS GIS Cut Line= 6
      3039409.98     13848305.63      3039642.88     13844501.51
      3039777.52     13844102.83      3039152.92     13843456.49
      3038296.51     13841153.71      3038239.42      13838222.9
#Sta/Elev= 30
   493.5    82.3   663.5    77.9  1903.5    81.5  2801.7    76.6  4600.5   77.79
  4819.1    83.1  4862.9   76.99  4881.6   78.16  4943.8   57.87  4962.8   55.14
  4967.5   49.37  4997.1   49.13  5032.5   49.81  5046.9   56.75  5100.8   63.87
  5132.6   73.98  5190.7    78.5    5271   75.16  5396.3    71.4  5678.6    74.7
  5788.6    69.9  5868.6    74.6  6245.1   79.12  7648.6    82.2  7708.6    86.2
  8185.5    86.9  8225.5    84.2  8285.5    87.4  9015.5      84 11016.9    87.4
#Mann= 6 ,-1 , 0
   493.5     .15       0  4600.5      .1       0  4943.8     .06       0
  5046.9      .1       0    5271      .2       0  6245.1      .1       0
Bank Sta=4881.6,5132.6
XS Rating Curve= 0
Exp/Cntr=.3,.1

Type RM Length L Ch R = 1 ,240579.0,232.7,202.7,197.1
BEGIN DESCRIPTION:
Cross Section 240579.0 - Interpolated
END DESCRIPTION:
XS GIS Cut Line= 6
      3040353.32     13844895.17      3040365.44     13844507.34
      3040304.84     13844283.12      3040068.51     13843846.81
      3039698.86     13842913.59      3039280.72      13842216.7
#Sta/Elev= 30
  3680.3    78.6  3830.3    77.3  3860.3    75.4  4108.3    77.2  4178.3    74.4
  4208.3    76.8    4300    77.4  4630.6    76.3  4700.1   74.12  4760.6    75.5
  4796.8    80.2  4811.8    80.6    4863   76.64  4892.7   70.46    4893   68.22
  4906.6   67.78  4939.1   60.56  4967.4   57.16  4976.3   53.79  4982.3   49.19
    5006   48.94  5020.8   50.74  5028.9   56.62  5062.6   61.17  5086.9   68.72
  5110.8   72.05    5138    74.4  5250.4   75.24    5970   77.43  6613.5    78.4
#Mann= 7 ,-1 , 0
  3680.3      .2       0    4300     .15       0  4700.1      .1       0
  4939.1    .045       0  5062.6     .12       0  5250.4      .2       0
    5970     .12       0
Bank Sta=4863,5110.8
XS Rating Curve= 0
Exp/Cntr=.5,.3

Type RM Length L Ch R = 1 ,240376.3,122,122,122
BEGIN DESCRIPTION:
Upstream Section of Bridge/Culvert/Weir
END DESCRIPTION:
XS GIS Cut Line= 6
      3040453.76     13845198.05      3040721.53     13844849.94
      3040650.11       13844574.      3040231.76     13843624.38
      3039921.38     13843149.53      3038457.37     13840354.86
#Sta/Elev= 30
    3141   78.75    3345   76.24  3998.6   76.85  4058.9   74.56  4149.3   76.62
  4456.6   74.15  4718.8   75.63  4734.2   77.89    4863   79.56    4878   74.36
  4892.7   70.38    4893   68.14  4906.6    67.7  4939.1   60.48  4967.4   57.08
  4982.3   49.11    5006   48.86  5020.8   50.66  5028.9   56.54  5062.6   61.09
  5110.8   75.97  5463.7   74.73  6158.3   77.86  6629.5   78.32  7763.2   85.58
  8099.8   85.27  8242.8    86.9  8400.2   85.11  8456.6   87.43  8625.6   87.85
#Mann= 7 ,-1 , 0
    3141      .2       0    4863      .1       0    4878     .14       0
  4939.1    .045       0  5062.6     .14       0  6158.3     .04       0
  8099.8      .1       0
#XS Ineff= 2 , 0
          4877.5    74.5    5125            76.5
Permanent Ineff=
       F       F
Bank Sta=4863,5110.8
XS Rating Curve= 0
Exp/Cntr=.5,.3

Type RM Length L Ch R = 3 ,240315.3,,,
BEGIN DESCRIPTION:
ELDRIDGE PARKWAY
Structure ID: WOO-80&81
END DESCRIPTION:
Bridge Culvert--1,0,-1,-1, 0
Deck Dist Width WeirC Skew NumUp NumDn MinLoCord MaxHiCord MaxSubmerge Is_Ogee
10,102,2.6,0, 60, 60, , , .95, 0, 1,1,,
    3141  3233.6    3345  3512.9  3560.7  3998.6  4043.8  4058.9  4073.9  4149.3
  4360.4  4456.6  4649.1  4718.8  4734.2 4747.79  4747.9  4755.8  4851.1    4863
 4873.91    4874  5003.3 5114.09  5114.2  5142.5  5225.7  5297.2 5297.31  5363.1
  5435.8  5470.7    5508  5542.3  5662.3  5741.9    5879  6056.6  6090.9    6144
  6176.6  6629.5  7011.6  7497.8  7518.9  7551.5  7763.2    7832  8058.3    8073
  8105.5  8138.1  8171.5  8242.8  8356.8  8400.2  8420.9  8456.6  8616.9  8625.6
   78.75   78.14   76.24   77.41   76.82   76.86   74.65    74.6    75.7   76.63
   75.84   74.16   75.42   77.52   78.05   78.52   81.72   81.99    84.2   84.47
   84.71   84.72   85.71   84.69   84.68   84.23    82.3    80.7    77.5   76.52
    76.6   77.63   77.54   77.67   78.58   78.73   77.39   77.84   77.69   77.58
   78.35   78.33    81.2   83.83   84.39   83.84   85.59   85.15   85.49   85.99
   85.08   85.69   85.26    86.9   86.56   85.11    85.3   87.43   88.04   87.85
   78.75   78.14   76.24    77.4   76.81   76.85   74.64   74.56   75.69   76.62
   75.83   74.15   75.41   75.63   77.89   77.61   77.61   77.45   80.66   79.56
   75.78   76.88   77.87   76.85   76.11   77.32    75.9   76.14   76.14    75.1
   74.95   74.76   74.95   75.78      76   77.32    77.2   77.83      77   76.94
   78.34   78.32   81.19   83.82   84.38   83.83   85.58   85.15   85.49   85.99
   85.08   85.69   85.26    86.9   86.56   85.11    85.3   87.43   88.04   87.85
    3141  3233.6    3345  3512.9  3560.7  3998.6  4043.8  4058.9  4073.9  4149.3
  4360.4  4456.6  4649.1  4718.8  4734.2 4747.79  4747.9  4755.8  4851.1    4863
 4873.91    4874  5003.3 5114.09  5114.2  5142.5  5225.7  5297.2 5297.31  5363.1
  5435.8  5470.7    5508  5542.3  5662.3  5741.9    5879  6056.6  6090.9    6144
  6176.6  6629.5  7011.6  7497.8  7518.9  7551.5  7763.2    7832  8058.3    8073
  8105.5  8138.1  8171.5  8242.8  8356.8  8400.2  8420.9  8456.6  8616.9  8625.6
   78.75   78.14   76.24   77.41   76.82   76.86   74.65    74.6    75.7   76.63
   75.84   74.16   75.42   77.52   78.05   78.52   81.72   81.99    84.2   84.47
   84.71   84.72   85.71   84.69   84.68   84.23    82.3    80.7    77.5   76.52
    76.6   77.63   77.54   77.67   78.58   78.73   77.39   77.84   77.69   77.58
   78.35   78.33    81.2   83.83   84.39   83.84   85.59   85.15   85.49   85.99
   85.08   85.69   85.26    86.9   86.56   85.11    85.3   87.43   88.04   87.85
   78.64   78.03   76.13   77.29    76.7   76.74   74.53   74.45   75.58   76.51
   75.72   74.04    75.3   75.52   77.78    77.5    77.5   77.34   80.55   79.45
   75.67   76.77   77.76   76.74      76   77.21   75.79   76.03   76.03   74.99
   74.84   74.65   74.84   75.67   75.89   77.21   77.09   77.72   76.89   76.83
   78.23   78.21   81.08   83.71   84.27   83.72   85.47   85.04   85.38   85.88
   84.97   85.58   85.15   86.79   86.45      85   85.19   87.32   87.93   87.74
Pier Skew, UpSta & Num, DnSta & Num=  ,4953.9, 2 ,4953.9, 2 , 0 , 0 , 0 ,,
     2.5     2.5
   57.92    78.5
     2.5     2.5
   57.81   78.39
Pier Skew, UpSta & Num, DnSta & Num=  ,5034, 2 ,5034, 2 , 0 , 0 , 0 ,,
     2.5     2.5
   56.14    78.6
     2.5     2.5
   56.03   78.49
Abutment Skew #Up #Dn= , 2 , 2
  4873.8  4890.7
   76.88   70.06
  4873.8  4890.7
   76.77   69.95
Abutment Skew #Up #Dn= , 2 , 2
  5097.2 5114.29
   70.39   76.85
  5097.2 5114.29
   70.28   76.74
BR Coef= 1 , 1 , 0 ,1.25, 0 ,,,.8,0,2,0,
WSPro=,,,, 1 ,,,, 0 ,,,, 0 ,,,,-1 ,-1 ,-1 , 0 , 0 , 0 , 0 , 0
BR U #Sta/Elev= 30
    3141   78.75    3345   76.24  3998.6   76.85  4058.9   74.56  4149.3   76.62
  4456.6   74.15  4718.8   75.63  4734.2   77.89    4863   79.56    4878   74.36
  4892.7   70.38    4893   68.14  4906.6    67.7  4939.1   60.48  4967.4   57.08
  4982.3   49.11    5006   48.86  5020.8   50.66  5028.9   56.54  5062.6   61.09
  5110.8   75.97  5463.7   74.73  6158.3   77.86  6629.5   78.32  7763.2   85.58
  8099.8   85.27  8242.8    86.9  8400.2   85.11  8456.6   87.43  8625.6   87.85
BR U #Mann= 7
    3141      .2    4863      .1    4878     .14  4939.1    .045  5062.6     .14
  6158.3     .04  8099.8      .1
BR U Banks=4863,5110.8
BR D #Sta/Elev= 30
    3141   78.64    3345   76.13  3998.6   76.74  4058.9   74.45  4149.3   76.51
  4456.6   74.04  4718.8   75.52  4734.2   77.78    4863   79.45    4878   74.25
  4892.7   70.27    4893   68.03  4906.6   67.59  4939.1   60.37  4967.4   56.97
  4982.3      49    5006   48.75  5020.8   50.55  5028.9   56.43  5062.6   60.98
  5110.8   75.86  5463.7   74.62  6158.3   77.75  6629.5   78.21  7763.2   85.47
  8099.8   85.16  8242.8   86.79  8400.2      85  8456.6   87.32  8625.6   87.74
BR D #Mann= 7
    3141      .2    4863      .1    4878     .14  4939.1    .045  5062.6     .14
  6158.3     .04  8099.8      .1
BR D Banks=4863,5110.8
BC Design=,, 0 ,, 0 ,,,,,,
BC HTab HWMax=88.04

Type RM Length L Ch R = 1 ,240254.3,260.7,260.7,260.7
BEGIN DESCRIPTION:
Downstream Section of Bridge/Culvert/Weir
END DESCRIPTION:
XS GIS Cut Line= 6
      3040557.09      13845133.2      3040824.87      13844785.1
      3040753.45     13844509.16       3040335.1     13843559.54
      3040024.72     13843084.69      3038560.71     13840290.02
#Sta/Elev= 30
    3141   78.57    3345   76.06  3998.6   76.67  4058.9   74.38  4149.3   76.44
  4456.6   73.97  4718.8   75.45  4734.2   77.71    4863   79.38    4878   74.18
  4892.7    70.2    4893   67.96  4906.6   67.52  4939.1    60.3  4967.4    56.9
  4982.3   48.93    5006   48.68  5020.8   50.48  5028.9   56.36  5062.6   60.91
  5110.8   75.79  5463.7   74.55  6158.3   77.68  6629.5   78.14  7763.2    85.4
  8099.8   85.09  8242.8   86.72  8400.2   84.93  8456.6   87.25  8625.6   87.67
#Mann= 7 ,-1 , 0
    3141      .2       0    4863      .1       0    4878     .14       0
  4939.1    .045       0  5062.6     .14       0  6158.3     .04       0
  8099.8      .1       0
#XS Ineff= 2 , 0
          4877.5    74.5    5125            76.5
Permanent Ineff=
       F       F
Bank Sta=4863,5110.8
XS Rating Curve= 0
Exp/Cntr=.5,.3