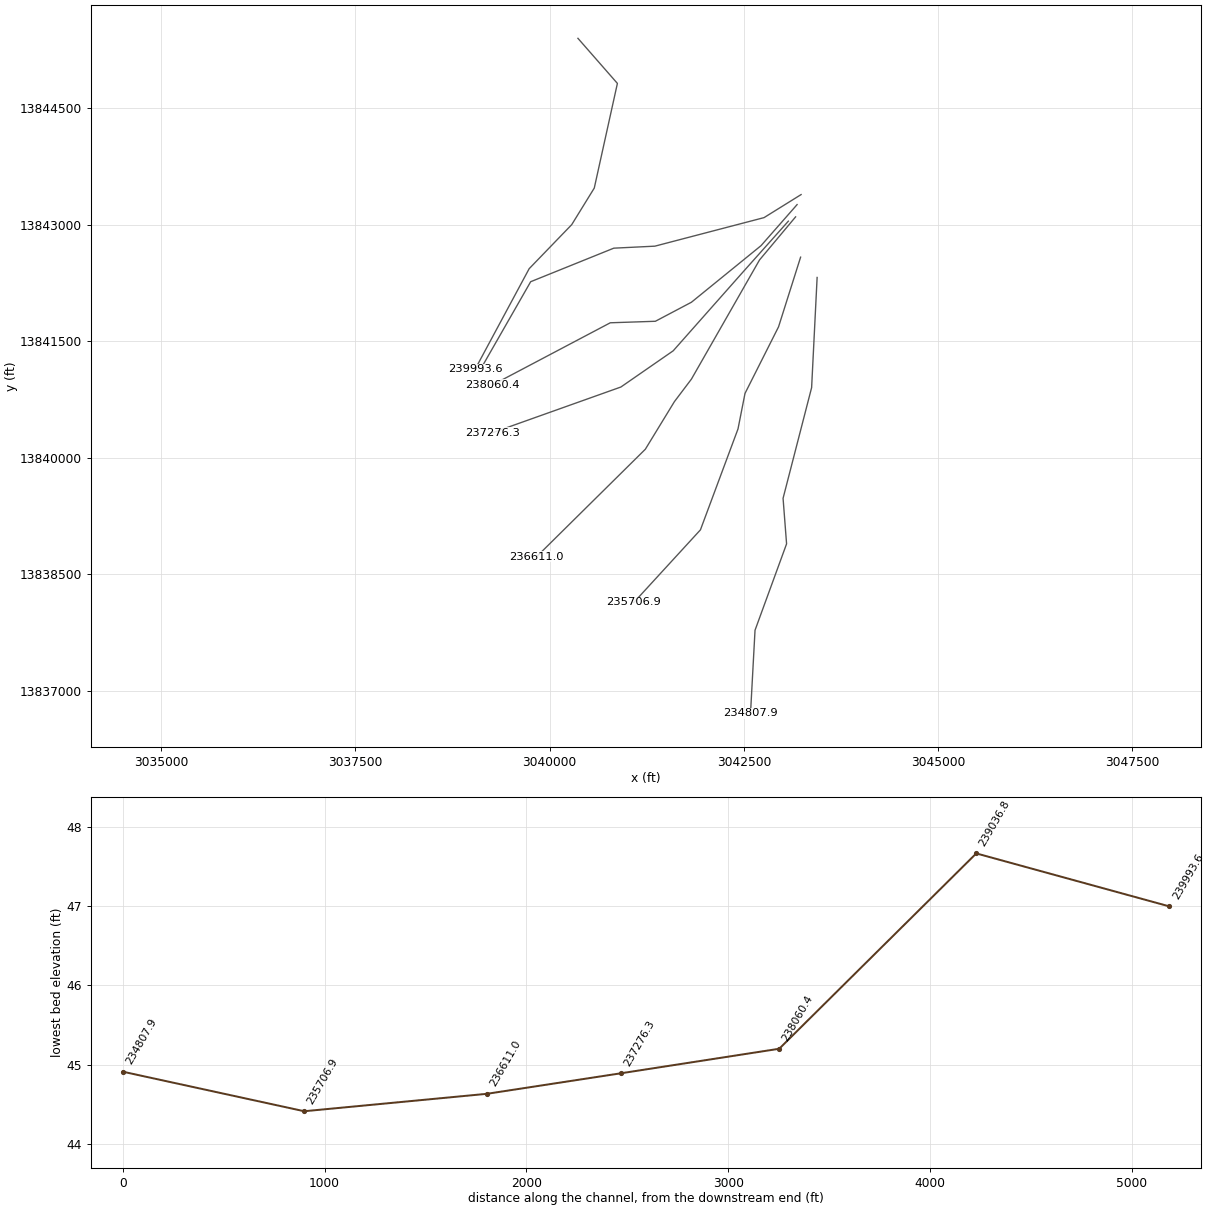
HEC-RAS study W100-00-00.prj: W100-00-00

--- W100-00-00.g01 (geometry) --- (continued)

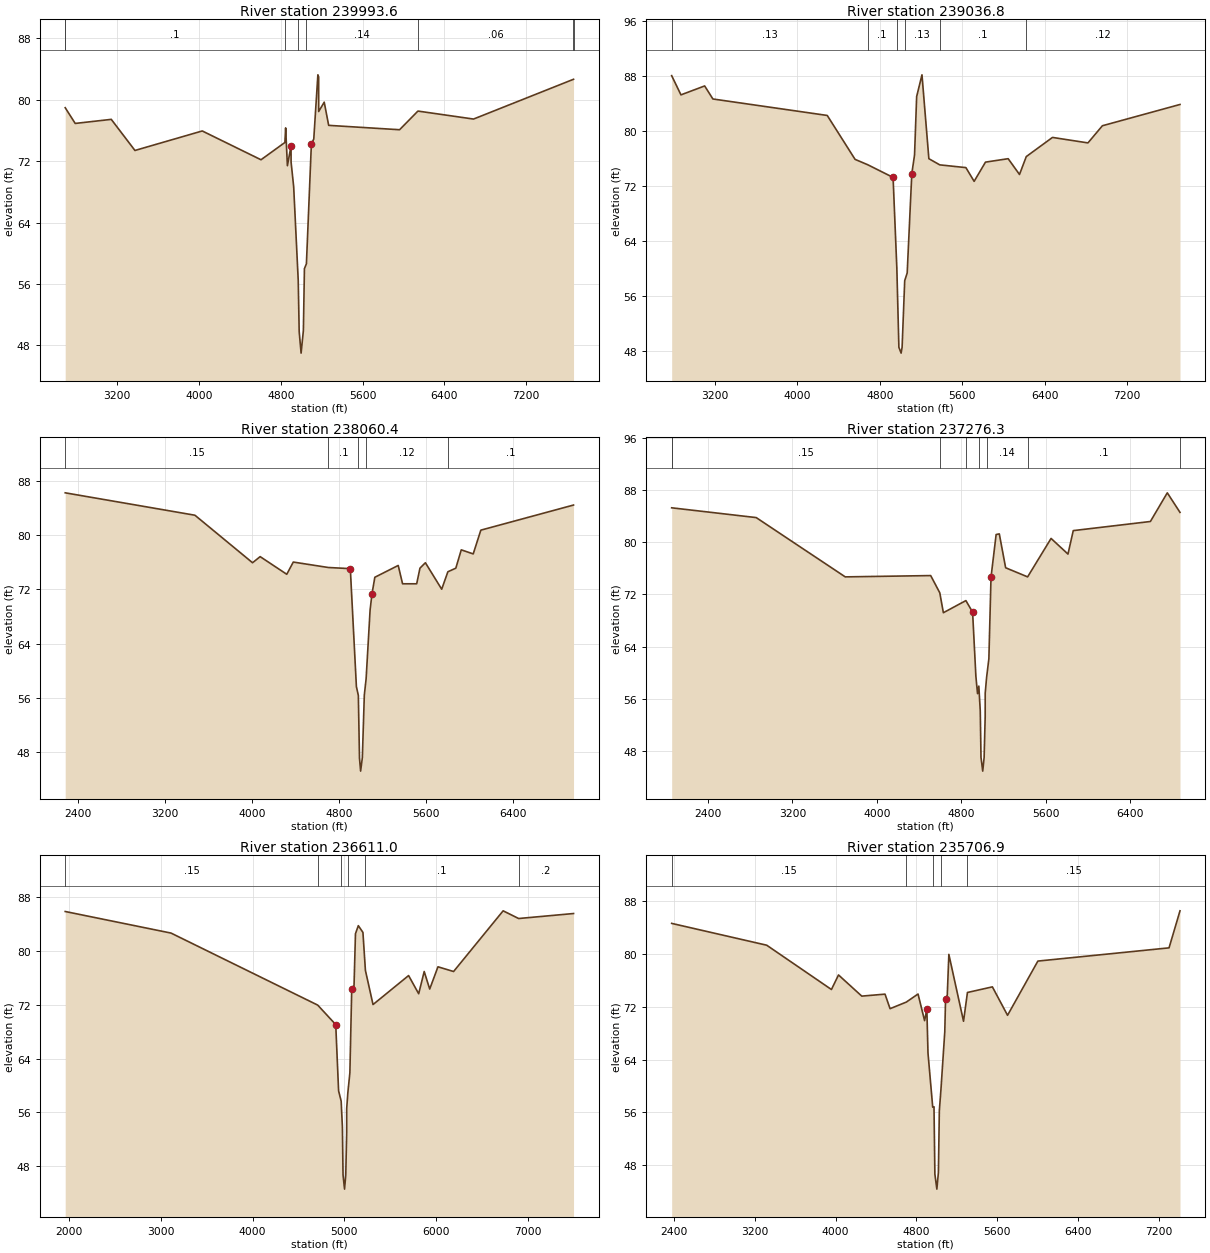
Type RM Length L Ch R = 1 ,239993.6,1026,956.8,847.5
BEGIN DESCRIPTION:
Cross Section 239993.6
END DESCRIPTION:
XS GIS Cut Line= 6
      3040364.62     13845399.92      3040872.43     13844819.69
      3040574.74     13843472.34      3040284.66     13843001.76
      3039736.73     13842434.49      3039040.53     13841138.79
#Sta/Elev= 30
  2691.6   78.96  2789.4   76.91  3142.1   77.44  3373.6   73.39  4031.6   75.93
  4606.1   72.18  4839.7   74.43    4847   76.33  4864.3    71.4  4899.6   73.98
  4900.3   71.88  4925.6   68.66  4970.1   56.48  4979.5    49.8  4998.2      47
  5020.5   49.94  5030.7      58  5050.2   58.64  5098.5   74.19  5122.1   74.88
  5162.2   83.24  5169.7   82.97  5170.2   78.46  5224.2   79.68  5267.8   76.66
  5961.1   76.09  6140.6   78.52  6684.2   77.48    7660   82.65    7662   82.66
#Mann= 8 ,-1 , 0
  2691.6      .2       0  2691.6      .1       0  4839.7     .14       0
  4970.1     .04       0  5050.2     .14       0  6140.6     .06       0
    7660     .04       0    7662      .2       0
Bank Sta=4899.6,5098.5
XS Rating Curve= 0
Exp/Cntr=.3,.1

Type RM Length L Ch R = 1 ,239036.8,976.9,976.4,973.1
BEGIN DESCRIPTION:
Cross Section 239036.8
END DESCRIPTION:
XS GIS Cut Line= 6
      3043237.05     13843388.54      3042760.03     13843092.01
      3041354.74     13842724.57      3040826.15     13842698.79
      3039756.07     13842266.89      3039143.67     13841196.81
#Sta/Elev= 30
  2780.3    88.1  2870.3    85.3  3100.3    86.6  3180.3    84.7  4289.5    82.3
  4559.5    75.9  4680.6   75.13  4928.1   73.27  4964.6   60.03  4984.4   48.52
  5006.1   47.67  5015.6   48.53  5040.9   58.23  5064.9   59.35  5109.7   73.82
  5136.3   76.54  5156.7   85.05  5208.4   88.22  5275.2      76  5381.1    75.1
  5634.4    74.7  5714.4    72.7  5824.4    75.5  6044.4      76  6154.4    73.7
  6220.3   76.31  6474.4    79.1  6818.4    78.3  6958.4    80.8  7711.3    83.9
#Mann= 6 ,-1 , 0
  2780.3     .13       0  4680.6      .1       0  4964.6    .055       0
  5040.9     .13       0  5381.1      .1       0  6220.3     .12       0
Bank Sta=4928.1,5109.7
XS Rating Curve= 0
Exp/Cntr=.3,.1

Type RM Length L Ch R = 1 ,238060.4,699.8,784.1,857.1
BEGIN DESCRIPTION:
Cross Section 238060.4
END DESCRIPTION:
XS GIS Cut Line= 6
      3043185.48     13843259.61      3042721.35     13842731.02
      3041825.32     13842002.59      3041361.19     13841757.63
      3040781.02     13841738.29      3039266.15     13840938.95
#Sta/Elev= 30
  2279.6    86.2    3473    82.9    4003    75.9    4073    76.8  4317.8    74.2
  4377.8      76  4699.6    75.2  4902.5   75.03  4958.4   57.65  4976.3   56.35
  4986.8   47.12  4997.3    45.2  5013.2    47.2  5031.3   56.41  5047.8    58.8
  5084.3   68.91  5101.1   71.24    5128   73.76  5343.1    75.5  5383.1    72.8
  5513.1    72.8  5543.1    75.1  5593.1    75.9  5743.1      72    5800   74.57
  5873.1    75.1  5923.1    77.8  6033.1    77.2  6103.1    80.7  6955.9    84.4
#Mann= 5 ,-1 , 0
  2279.6     .15       0  4699.6      .1       0  4976.3     .06       0
  5047.8     .12       0    5800      .1       0
Bank Sta=4902.5,5101.1
XS Rating Curve= 0
Exp/Cntr=.3,.1

Type RM Length L Ch R = 1 ,237276.3,627.1,665.3,708.4
BEGIN DESCRIPTION:
Cross Section 237276.3-Interpolated
END DESCRIPTION:
XS GIS Cut Line= 5
      3043072.96      13843046.2      3042471.91     13842372.61
      3041591.05     13841377.76      3040917.45     13840911.42
      3039259.37     13840320.73
#Sta/Elev= 30
  2057.6    85.3  2857.6    83.8  3700.4    74.7  4509.1    74.9  4595.1   72.26
  4629.1    69.2  4842.1   71.06  4905.7   69.29  4936.7   59.47  4952.3   56.78
  4964.7   57.94  4978.2   54.12  4985.2      47  5001.6   44.89  5014.8   46.98
  5024.8   53.26    5025   56.83  5037.9   59.23  5059.7   62.14    5080   74.64
  5128.4    81.2  5158.4    81.3  5218.4    76.1  5426.5    74.7  5648.4    80.6
  5808.4    78.2  5858.4    81.8  6588.4    83.2  6748.4    87.6  6868.6    84.6
#Mann= 8 ,-1 , 0
  2057.6      .2       0  2057.6     .15       0  4595.1     .08       0
  4842.1     .14       0  4964.7     .06       0  5037.9     .14       0
  5426.5      .1       0  6868.6      .2       0
Bank Sta=4905.7,5080
XS Rating Curve= 0
Exp/Cntr=.3,.1

Type RM Length L Ch R = 1 ,236611.0,896.9,904.1,914.4
BEGIN DESCRIPTION:
Cross Section 236611.0
END DESCRIPTION:
XS GIS Cut Line= 6
      3043166.14     13843101.68      3042702.01      13842547.3
      3041825.32     13841013.09      3041606.14     13840723.01
      3041232.26     13840110.61      3039833.42     13838727.89
#Sta/Elev= 30
  1958.3    85.8  3111.3    82.6  4709.2   71.92  4905.7   69.03  4936.7   59.21
  4964.7   57.68  4978.2   53.86  4985.2   46.74  5001.6   44.63  5014.8   46.72
  5024.8      53    5025   56.57  5037.9   58.97  5059.7   61.88    5080   74.38
    5105   74.83  5120.6    82.5  5151.9    83.7  5201.9    82.7  5228.9   77.07
  5311.9      72  5699.4    76.3  5809.4    73.6  5869.4    76.9  5929.4    74.3
  6019.4    77.6  6189.4    76.9  6729.4    85.9  6898.3   84.76  7496.3    85.5
#Mann= 6 ,-1 , 0
  1958.3     .15       0  4709.2      .1       0  4964.7     .06       0
  5037.9     .15       0  5228.9      .1       0  6898.3      .2       0
Bank Sta=4905.7,5080
XS Rating Curve= 0
Exp/Cntr=.3,.1

Type RM Length L Ch R = 1 ,235706.9,894.4,899,912.4
BEGIN DESCRIPTION:
Cross Section 235706.9
END DESCRIPTION:
XS GIS Cut Line= 6
       3043230.6     13842582.75      3042946.97     13841686.72
      3042515.07     13840829.37      3042424.82     13840371.68
      3041941.35     13839072.76        3041084.     13838138.05
#Sta/Elev= 30
  2379.6    84.6  3319.5    81.3  3959.5    74.6  4029.5    76.8  4259.5    73.6
  4489.4    73.9  4539.4    71.7  4700.2    72.7    4816   73.92  4880.9   69.89
  4903.1   71.63  4914.4      65  4961.2    56.8  4973.8   56.87  4982.6   46.67
  5002.1   44.41  5017.4   46.93  5026.7    56.3  5042.2   59.39  5080.5   68.22
  5088.1   73.11  5105.2   73.76  5120.7   79.91  5265.9    69.8  5304.6   74.15
  5551.2      75  5701.2    70.7  6001.2    78.9  7298.3    80.9  7406.6    86.5
#Mann= 5 ,-1 , 0
  2379.6     .15       0  4700.2      .1       0  4961.2    .055       0
  5042.2     .12       0  5304.6     .15       0
Bank Sta=4903.1,5088.1
XS Rating Curve= 0
Exp/Cntr=.3,.1

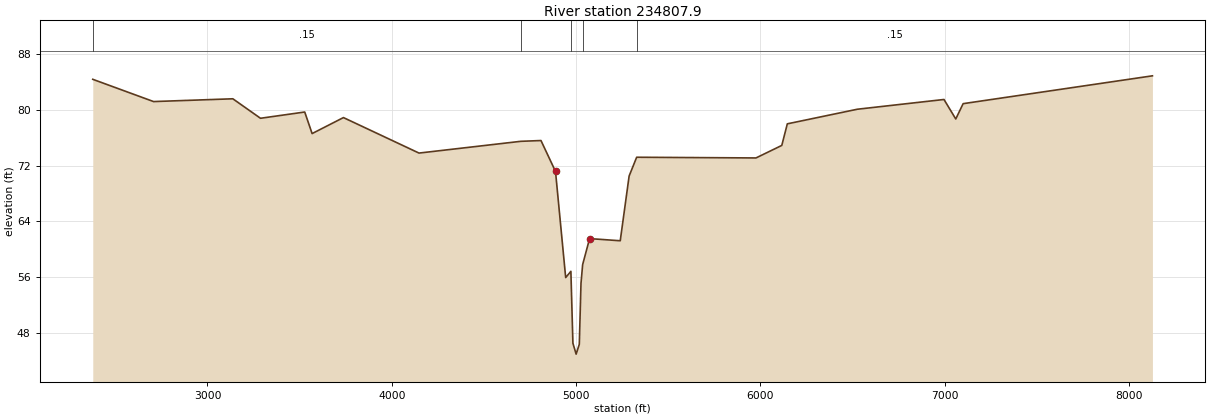
Type RM Length L Ch R = 1 ,234807.9,1035.8,1109.5,1195.3
BEGIN DESCRIPTION:
Cross Section 234807.9
END DESCRIPTION:
XS GIS Cut Line= 6
      3043443.33     13842321.68      3043372.42      13840903.5
      3043004.98     13839478.88      3043050.11     13838892.27
      3042643.99     13837780.28      3042585.98      13836710.2
#Sta/Elev= 30
  2377.7    84.4  2707.7    81.2  3137.7    81.6  3287.7    78.8  3527.7    79.7
  3567.7    76.6  3737.7    78.9  4147.7    73.8  4700.2   75.49  4809.5    75.6
  4888.3   71.16  4943.5   55.91  4971.7   56.81  4982.7   46.48  5000.2   44.91
  5017.4   46.32  5026.6    55.1  5035.6   57.78  5073.2   61.51  5239.5    61.2
  5287.7    70.5  5328.6    73.2    5976    73.1    6116    74.9    6146      78
    6526    80.1    6996    81.5  7059.9    78.7  7099.9    80.9  8126.9    84.9
#Mann= 5 ,-1 , 0
  2377.7     .15       0  4700.2      .1       0  4971.7    .055       0
  5035.6     .12       0  5328.6     .15       0
Bank Sta=4888.3,5073.2
XS Rating Curve= 0
Exp/Cntr=.3,.1