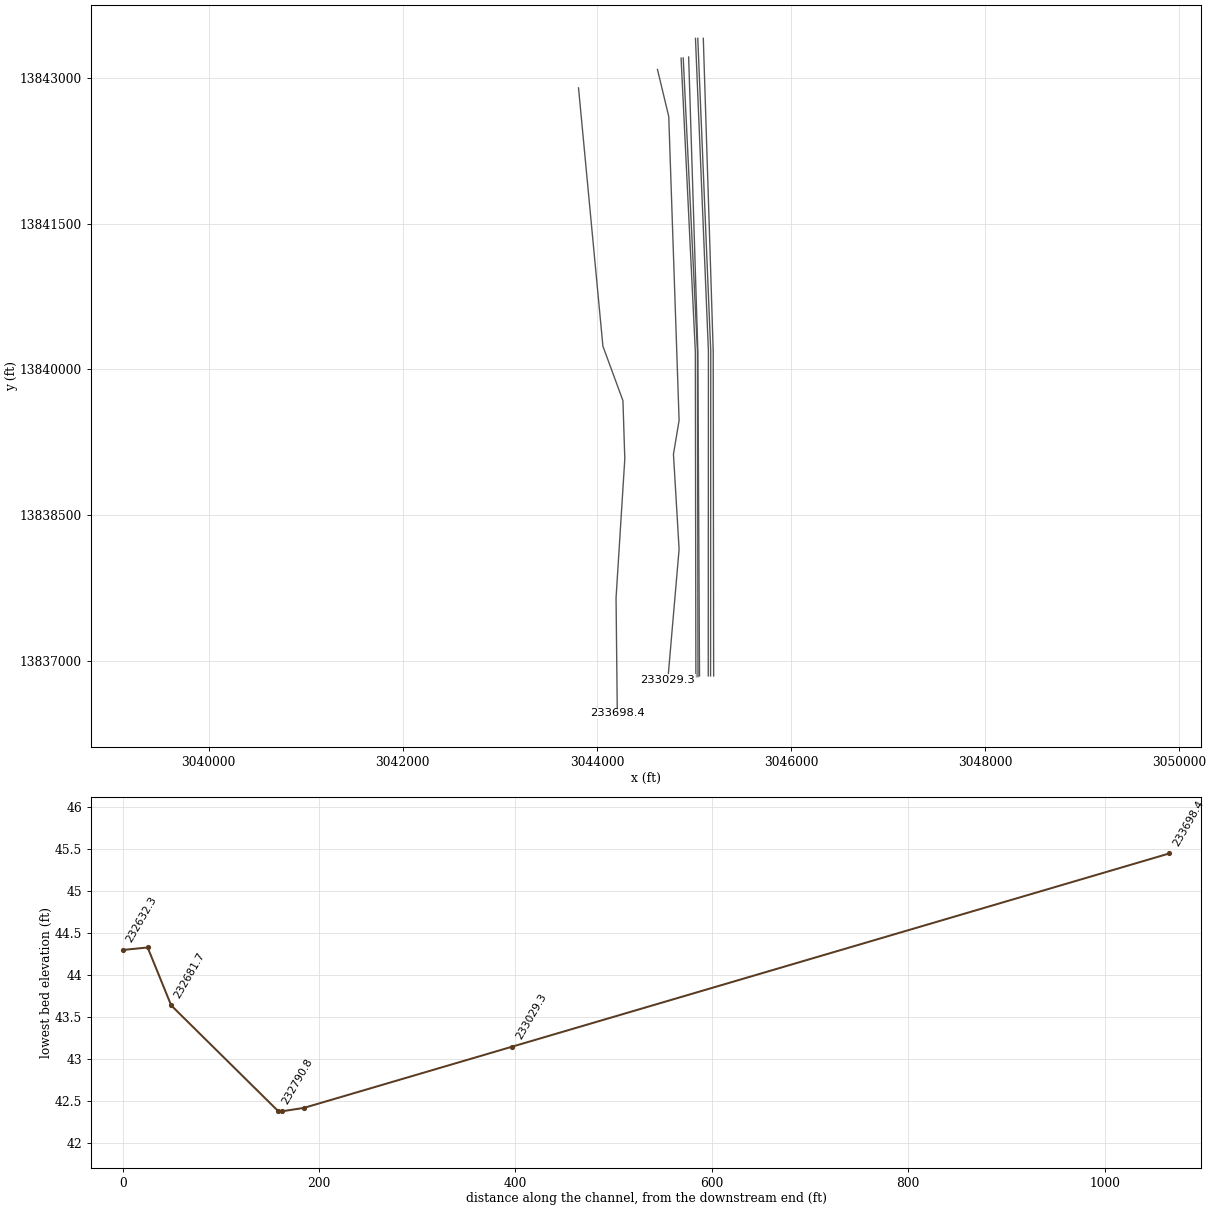
HEC-RAS study W100-00-00.prj: W100-00-00

--- W100-00-00.g01 (geometry) --- (continued)

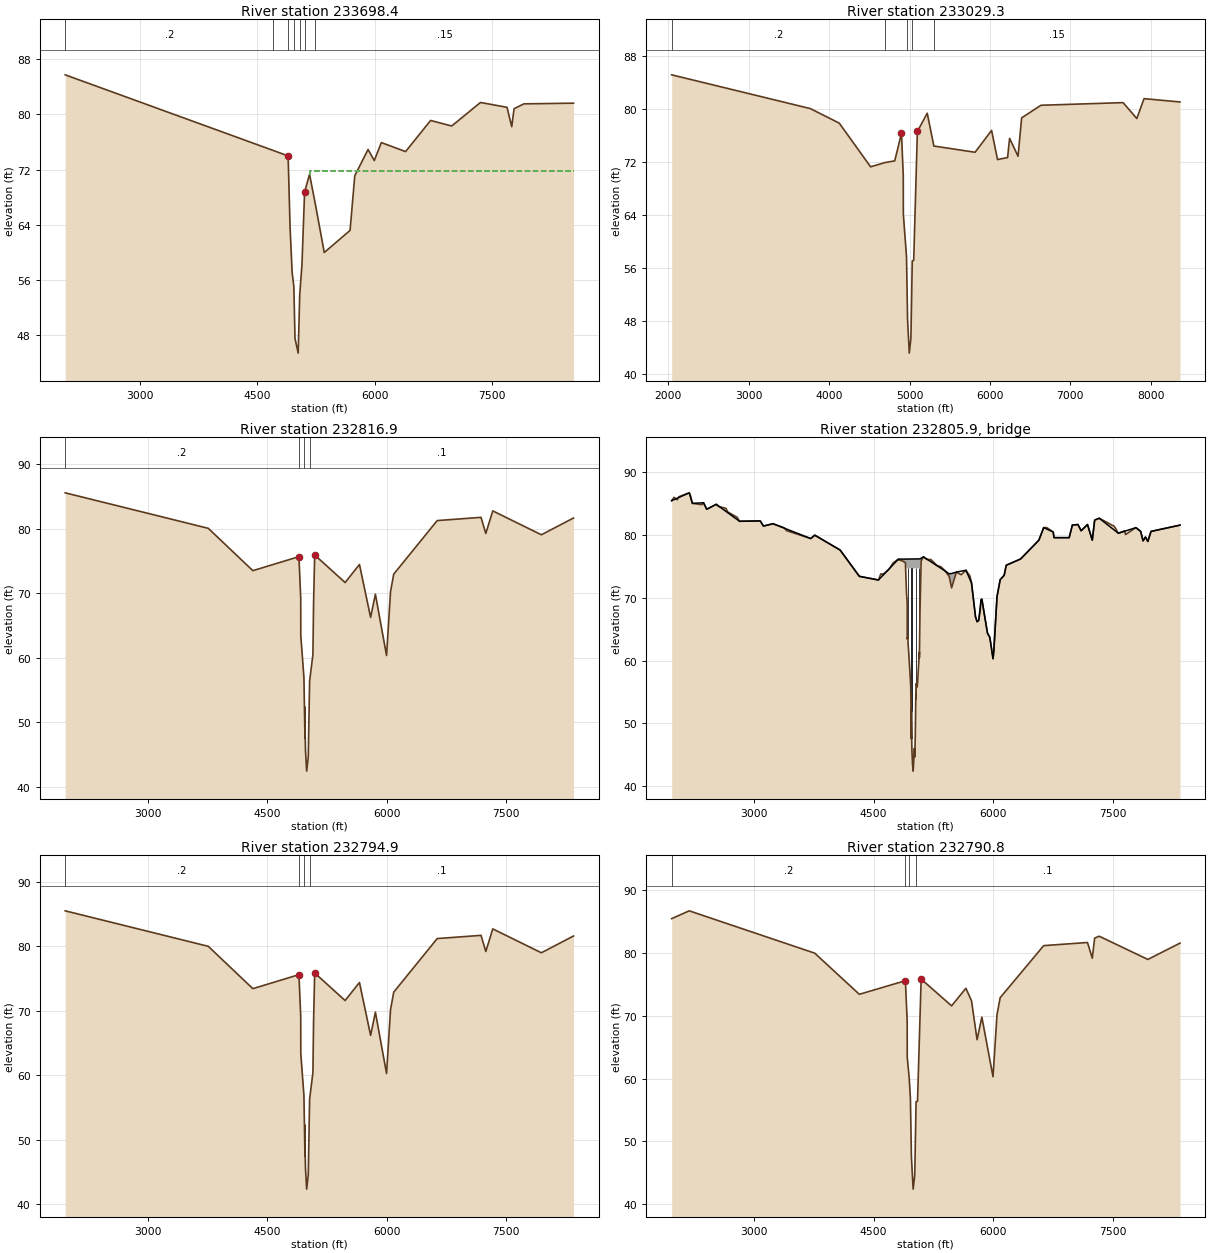
Type RM Length L Ch R = 1 ,233698.4,694.8,669.1,644.3
BEGIN DESCRIPTION:
Cross Section 233698.4
END DESCRIPTION:
XS GIS Cut Line= 6
      3043810.77     13842901.84      3044062.17     13840239.54
      3044268.45     13839678.71      3044287.79     13839079.21
      3044197.54     13837644.91      3044210.44     13836455.58
#Sta/Elev= 30
  2041.7    85.7  4701.7   74.76  4891.8   73.97  4892.3   73.78  4916.1   63.84
  4942.7   57.17  4965.2   55.05  4979.6   47.57  5020.5   45.45  5039.9   53.86
  5068.9   58.29  5102.1   68.69  5102.3   68.74  5165.6   71.32  5241.7    66.9
  5353.8      60  5683.8    63.2  5743.8    71.1  5913.6    74.9  5993.6    73.3
  6083.6    75.9  6393.6    74.6  6713.6    79.1  6983.6    78.3  7350.8    81.7
  7690.8      81  7750.8    78.2  7780.8    80.8  7905.7    81.5  8540.8    81.6
#Mann= 7 ,-1 , 0
  2041.7      .2       0  4701.7      .1       0  4892.3      .1       0
  4965.2     .06       0  5039.9      .1       0  5102.1      .1       0
  5241.7     .15       0
#XS Ineff= 2 , 0
                            5167            71.8
Permanent Ineff=
       F       F
Bank Sta=4891.8,5102.3
XS Rating Curve= 0
Exp/Cntr=.3,.1

Type RM Length L Ch R = 1 ,233029.3,263.9,212.4,208.4
BEGIN DESCRIPTION:
Cross Section 233029.3 - Interpolated
END DESCRIPTION:
XS GIS Cut Line= 6
      3044624.32     13843091.75      3044740.67     13842606.96
      3044847.33     13839475.21      3044789.15     13839126.17
      3044847.33     13838146.89      3044730.98     13836799.17
#Sta/Elev= 30
  2042.9    85.2  3766.5    80.1  4126.5    77.9  4516.5    71.3  4697.2   71.95
  4816.5    72.2 4900.17   76.38 4922.77    69.9 4923.27    64.2 4962.97   57.65
 4975.67    48.3 4997.27   43.15 5017.47   45.39 5034.17   57.09 5052.17   57.16
 5097.77   76.64  5220.5    79.4  5302.8   74.44  5815.5    73.5  6020.5    76.8
  6094.4    72.4  6219.4    72.7  6244.4    75.6  6349.4    72.9  6394.4    78.7
  6634.4    80.6  7655.4      81  7826.2    78.6  7916.2    81.6  8363.1    81.1
#Mann= 5 ,-1 , 0
  2042.9      .2       0  4697.2      .1       0 4962.97     .04       0
 5034.17      .1       0  5302.8     .15       0
Bank Sta=4900.17,5097.77
XS Rating Curve= 0
Exp/Cntr=.5,.3

Type RM Length L Ch R = 1 ,232816.9,22,22,22
BEGIN DESCRIPTION:
Upstream Section of Bridge/Culvert/Weir
END DESCRIPTION:
XS GIS Cut Line= 3
      3044867.88      13843208.2      3045014.86     13840178.67
      3045020.15     13836832.27
#Sta/Elev= 30
  1966.9   85.54  3762.4   80.04    4322   73.48 4900.17   75.65 4922.77   69.17
 4923.27   63.47 4962.97   56.92 4975.67   47.57 4976.47   52.34 4977.97    48.2
 4982.37   45.59 4997.27   42.42 5017.47   44.66 5034.17   56.36 5075.57   60.48
 5083.97   68.46 5097.77   75.91  5479.8   71.64  5659.8   74.44  5799.8   66.24
  5859.8   69.84  5999.8   60.34  6049.8   70.24  6089.8   72.94  6635.5   81.24
  7185.4   81.74  7245.4   79.24  7332.9   82.74  7942.9   79.04  8346.4   81.64
#Mann= 4 ,-1 , 0
  1966.9      .2       0 4900.17      .1       0 4962.97     .04       0
 5034.17      .1       0
#XS Ineff= 2 , 0
            4900    73.9    5100            73.7
Permanent Ineff=
       F       F
Bank Sta=4900.17,5097.77
XS Rating Curve= 0
Exp/Cntr=.5,.3

Type RM Length L Ch R = 3 ,232805.9,,,
BEGIN DESCRIPTION:
3-24" PIPELINES
END DESCRIPTION:
Bridge Culvert--1,0,-1,-1, 0
Deck Dist Width WeirC Skew NumUp NumDn MinLoCord MaxHiCord MaxSubmerge Is_Ogee
10,2,2.6,0, 60, 60, , , .95, 0, 1,1,,
  1966.9  2186.9  2226.9  2366.9  2406.9  2526.9  2818.6  3078.6  3118.6  3238.6
  3712.4  3762.4  4080.8    4322    4562 4811.97 4900.17 4914.37 5083.97 5126.17
 5403.47  5449.8  5479.8  5539.8  5659.8  5729.8  5779.8  5799.8  5819.8  5849.8
  5859.8  5929.8  5959.8  5999.8  6009.8  6049.8  6089.8  6139.8  6165.5  6345.5
  6575.5  6635.5  6755.4  6765.4  6955.4  6995.4  7065.4  7105.4  7185.4  7245.4
  7275.4  7332.9  7572.9  7792.9  7852.9  7882.9  7912.9  7942.9  7982.9  8346.4
    85.5   86.75   85.07   85.17   84.13   84.92   82.21   82.27   81.45   81.82
   79.46      80   77.63   73.44   72.85   76.18   76.19   76.19   76.22   76.55
   74.25   73.83   73.89   74.11    74.4    72.4      67    66.2    66.4    69.7
    69.8    64.4    63.7    60.3    61.5    70.2    72.9    73.6    75.2    76.2
    79.2    81.2    80.5    79.6    79.6    81.6    81.7    80.7    81.7    79.2
    82.4    82.7    80.3    81.2    80.6    79.1    79.7      79    80.6    81.6
    85.5   86.75   85.07   85.17   84.13   84.92   82.21   82.27   81.45   81.82
   79.46      80   77.63   73.44   72.85   76.17   75.61   74.69   74.72   76.54
   74.24    73.4    71.6    74.1    74.4    72.4      67    66.2    66.4    69.7
    69.8    64.4    63.7    60.3    61.5    70.2    72.9    73.6    75.2    76.2
    79.2    81.2    80.5    79.6    79.6    81.6    81.7    80.7    81.7    79.2
    82.4    82.7    80.3    81.2    80.6    79.1    79.7      79    80.6    81.6
  1966.9  2186.9  2226.9  2366.9  2406.9  2526.9  2818.6  3078.6  3118.6  3238.6
  3712.4  3762.4  4080.8    4322    4562 4811.97 4900.17 4914.37 5083.97 5126.17
 5403.47  5449.8  5479.8  5539.8  5659.8  5729.8  5779.8  5799.8  5819.8  5849.8
  5859.8  5929.8  5959.8  5999.8  6009.8  6049.8  6089.8  6139.8  6165.5  6345.5
  6575.5  6635.5  6755.4  6765.4  6955.4  6995.4  7065.4  7105.4  7185.4  7245.4
  7275.4  7332.9  7572.9  7792.9  7852.9  7882.9  7912.9  7942.9  7982.9  8346.4
    85.5   86.75   85.07   85.17   84.13   84.92   82.21   82.27   81.45   81.82
   79.46      80   77.63   73.44   72.85   76.18   76.19   76.19   76.22   76.55
   74.25   73.83   73.89   74.11    74.4    72.4      67    66.2    66.4    69.7
    69.8    64.4    63.7    60.3    61.5    70.2    72.9    73.6    75.2    76.2
    79.2    81.2    80.5    79.6    79.6    81.6    81.7    80.7    81.7    79.2
    82.4    82.7    80.3    81.2    80.6    79.1    79.7      79    80.6    81.6
    85.5   86.75   85.07   85.17   84.13   84.92   82.21   82.27   81.45   81.82
   79.46      80   77.63   73.44   72.85   76.17   75.61   74.69   74.72   76.54
   74.24    73.4    71.6    74.1    74.4    72.4      67    66.2    66.4    69.7
    69.8    64.4    63.7    60.3    61.5    70.2    72.9    73.6    75.2    76.2
    79.2    81.2    80.5    79.6    79.6    81.6    81.7    80.7    81.7    79.2
    82.4    82.7    80.3    81.2    80.6    79.1    79.7      79    80.6    81.6
Pier Skew, UpSta & Num, DnSta & Num=  ,4930.9, 2 ,4930.9, 2 , 0 , 0 , 0 ,,
     1.5     1.5
   62.67    75.7
     1.5     1.5
   62.67    75.7
Pier Skew, UpSta & Num, DnSta & Num=  ,4976.7, 2 ,4976.7, 2 , 0 , 0 , 0 ,,
     1.5     1.5
   48.02    75.7
     1.5     1.5
   48.02    75.7
Pier Skew, UpSta & Num, DnSta & Num=  ,5031.4, 2 ,5031.4, 2 , 0 , 0 , 0 ,,
     1.5     1.5
   53.39   75.71
     1.5     1.5
   53.39   75.71
Pier Skew, UpSta & Num, DnSta & Num=  ,5075.6, 2 ,5075.6, 2 , 0 , 0 , 0 ,,
     1.5     1.5
   60.15   75.72
     1.5     1.5
   60.15   75.72
BR Coef= 1 , 1 , 0 ,1.25, 0 ,,,.8,0,2,0,
WSPro=,,,, 1 ,,,, 0 ,,,, 0 ,,,,-1 ,-1 ,-1 , 0 , 0 , 0 , 0 , 0
BR U #Sta/Elev= 136
  1966.9    85.5  1996.9   86.03  2036.9   85.65  2056.9   86.12  2186.9   86.75
  2196.9   86.57  2226.9   85.07  2346.9   84.86  2366.9   85.17  2406.9   84.13
  2526.9   84.92  2556.9   84.55  2558.6   84.56  2648.6   84.27  2668.6   83.72
  2788.6   82.85  2818.6   82.21  2868.6   82.24  3078.6   82.27  3118.6   81.45
  3238.6   81.82  3378.6   81.18  3408.6   80.72  3712.4   79.46  3762.4      80
  4080.8   77.63    4322   73.44    4562   72.85    4592   73.83  4596.7   73.82
 4616.37   73.76 4617.07   73.72 4693.67   74.53  4697.2    74.6 4746.17   75.58
  4799.5   76.06 4811.97   76.17 4813.07   76.08  4859.5    75.9 4862.97   75.89
  4869.5   75.84  4889.5   75.69 4898.77   75.62 4898.88   75.62 4898.97   75.62
 4900.17   75.61 4914.37   70.72 4922.77   69.13 4923.27   63.43 4930.87   63.88
 4930.97   64.01 4932.97   62.95 4942.97   61.14 4947.57   60.14 4962.97   56.88
 4967.37   55.58 4975.67   47.53 4976.47    52.3 4976.67   51.98 4977.97   48.16
 4982.37   45.55 4990.27   43.41 4997.27   42.38 5008.87   44.82 5012.97   46.02
 5017.47   44.62 5024.27   47.95 5030.87   54.64 5031.37   53.93 5034.17   56.32
 5047.97    55.8 5052.17   56.39 5075.27   61.33 5075.57   60.44 5083.97   68.42
 5097.77   75.87 5121.86   76.44 5121.97   76.44 5122.07   76.44 5126.17   76.54
  5137.7   76.43 5167.97   76.14 5220.27   76.11 5293.17    75.2  5302.8   75.15
 5349.67   74.92  5389.1   74.42 5403.47   74.24 5403.57   74.23  5449.8    73.4
  5479.8    71.6  5539.8    74.1  5599.8    73.7  5621.8   73.96  5659.8    74.4
  5709.8    73.5  5729.8    72.4  5779.8      67  5799.8    66.2  5819.8    66.4
  5839.8      68  5849.8    69.7  5859.8    69.8  5929.8    64.4  5959.8    63.7
  5999.8    60.3  6009.8    61.5  6049.8    70.2  6089.8    72.9  6139.8    73.6
  6165.5    75.2  6345.5    76.2  6575.5    79.2  6635.5    81.2  6675.4    81.2
  6755.4    80.5  6765.4    79.6  6955.4    79.6  6995.4    81.6  7065.4    81.7
  7105.4    80.7  7185.4    81.7  7245.4    79.2  7275.4    82.4  7332.9    82.7
  7522.9    81.4  7572.9    80.3  7652.9    80.7  7662.9    80.1  7792.9    81.2
  7852.9    80.6  7882.9    79.1  7912.9    79.7  7942.9      79  7982.9    80.6
  8346.4    81.6
BR U #Mann= 4
  1966.9      .2 4900.17      .1 4962.97     .04 5034.17      .1
BR U Banks=4900.17,5097.77
BR D #Sta/Elev= 136
  1966.9    85.5  1996.9   86.03  2036.9   85.65  2056.9   86.12  2186.9   86.75
  2196.9   86.57  2226.9   85.07  2346.9   84.86  2366.9   85.17  2406.9   84.13
  2526.9   84.92  2556.9   84.55  2558.6   84.56  2648.6   84.27  2668.6   83.72
  2788.6   82.85  2818.6   82.21  2868.6   82.24  3078.6   82.27  3118.6   81.45
  3238.6   81.82  3378.6   81.18  3408.6   80.72  3712.4   79.46  3762.4      80
  4080.8   77.63    4322   73.44    4562   72.85    4592   73.83  4596.7   73.82
 4616.37   73.76 4617.07   73.72 4693.67   74.53  4697.2    74.6 4746.17   75.58
  4799.5   76.06 4811.97   76.17 4813.07   76.08  4859.5    75.9 4862.97   75.89
  4869.5   75.84  4889.5   75.69 4898.77   75.62 4898.88   75.62 4898.97   75.62
 4900.17   75.61 4914.37   70.72 4922.77   69.13 4923.27   63.43 4930.87   63.88
 4930.97   64.01 4932.97   62.95 4942.97   61.14 4947.57   60.14 4962.97   56.88
 4967.37   55.58 4975.67   47.53 4976.47    52.3 4976.67   51.98 4977.97   48.16
 4982.37   45.55 4990.27   43.41 4997.27   42.38 5008.87   44.82 5012.97   46.02
 5017.47   44.62 5024.27   47.95 5030.87   54.64 5031.37   53.93 5034.17   56.32
 5047.97    55.8 5052.17   56.39 5075.27   61.33 5075.57   60.44 5083.97   68.42
 5097.77   75.87 5121.86   76.44 5121.97   76.44 5122.07   76.44 5126.17   76.54
  5137.7   76.43 5167.97   76.14 5220.27   76.11 5293.17    75.2  5302.8   75.15
 5349.67   74.92  5389.1   74.42 5403.47   74.24 5403.57   74.23  5449.8    73.4
  5479.8    71.6  5539.8    74.1  5599.8    73.7  5621.8   73.96  5659.8    74.4
  5709.8    73.5  5729.8    72.4  5779.8      67  5799.8    66.2  5819.8    66.4
  5839.8      68  5849.8    69.7  5859.8    69.8  5929.8    64.4  5959.8    63.7
  5999.8    60.3  6009.8    61.5  6049.8    70.2  6089.8    72.9  6139.8    73.6
  6165.5    75.2  6345.5    76.2  6575.5    79.2  6635.5    81.2  6675.4    81.2
  6755.4    80.5  6765.4    79.6  6955.4    79.6  6995.4    81.6  7065.4    81.7
  7105.4    80.7  7185.4    81.7  7245.4    79.2  7275.4    82.4  7332.9    82.7
  7522.9    81.4  7572.9    80.3  7652.9    80.7  7662.9    80.1  7792.9    81.2
  7852.9    80.6  7882.9    79.1  7912.9    79.7  7942.9      79  7982.9    80.6
  8346.4    81.6
BR D #Mann= 4
  1966.9      .2 4900.17      .1 4962.97     .04 5034.17      .1
BR D Banks=4900.17,5097.77
BC Design=,, 0 ,, 0 ,,,,,,
BC HTab HWMax=86.79

Type RM Length L Ch R = 1 ,232794.9,4.1,4.1,4.1
BEGIN DESCRIPTION:
Downstream Section of Bridge/Culvert/Weir
END DESCRIPTION:
XS GIS Cut Line= 3
      3044889.77     13843210.43      3045036.74     13840180.89
      3045042.04     13836834.49
#Sta/Elev= 30
  1966.9    85.5  3762.4      80    4322   73.44 4900.17   75.61 4922.77   69.13
 4923.27   63.43 4962.97   56.88 4975.67   47.53 4976.47    52.3 4977.97   48.16
 4982.37   45.55 4997.27   42.38 5017.47   44.62 5034.17   56.32 5075.57   60.44
 5083.97   68.42 5097.77   75.87  5479.8    71.6  5659.8    74.4  5799.8    66.2
  5859.8    69.8  5999.8    60.3  6049.8    70.2  6089.8    72.9  6635.5    81.2
  7185.4    81.7  7245.4    79.2  7332.9    82.7  7942.9      79  8346.4    81.6
#Mann= 4 ,-1 , 0
  1966.9      .2       0 4900.17      .1       0 4962.97     .04       0
 5034.17      .1       0
#XS Ineff= 2 , 0
            4900    73.9    5100            73.7
Permanent Ineff=
       F       F
Bank Sta=4900.17,5097.77
XS Rating Curve= 0
Exp/Cntr=.5,.3

Type RM Length L Ch R = 1 ,232790.8,109.1,109.1,109.1
BEGIN DESCRIPTION:
Upstream Section of Bridge/Culvert/Weir
END DESCRIPTION:
XS GIS Cut Line= 3
      3044945.81       13843220.      3045040.54     13840188.37
       3045057.7     13836842.02
#Sta/Elev= 30
  1966.9    85.5  2186.9   86.75  3762.4      80    4322   73.44  4900.2   75.61
  4922.8   69.13  4923.3   63.43  4947.6   60.14    4963   56.88  4975.7   47.53
  4997.3   42.38  5017.5   44.62  5034.2   56.32  5052.2   56.39  5097.8   75.87
  5479.8    71.6  5659.8    74.4  5729.8    72.4  5799.8    66.2  5859.8    69.8
  5999.8    60.3  6049.8    70.2  6089.8    72.9  6635.5    81.2  7185.4    81.7
  7245.4    79.2  7275.4    82.4  7332.9    82.7  7942.9      79  8346.4    81.6
#Mann= 4 ,-1 , 0
  1966.9      .2       0  4900.2      .1       0  4947.6     .04       0
  5034.2      .1       0
#XS Ineff= 2 , 0
            4900    73.9    5100            73.7
Permanent Ineff=
       F       F
Bank Sta=4900.2,5097.8
XS Rating Curve= 0
Exp/Cntr=.5,.3

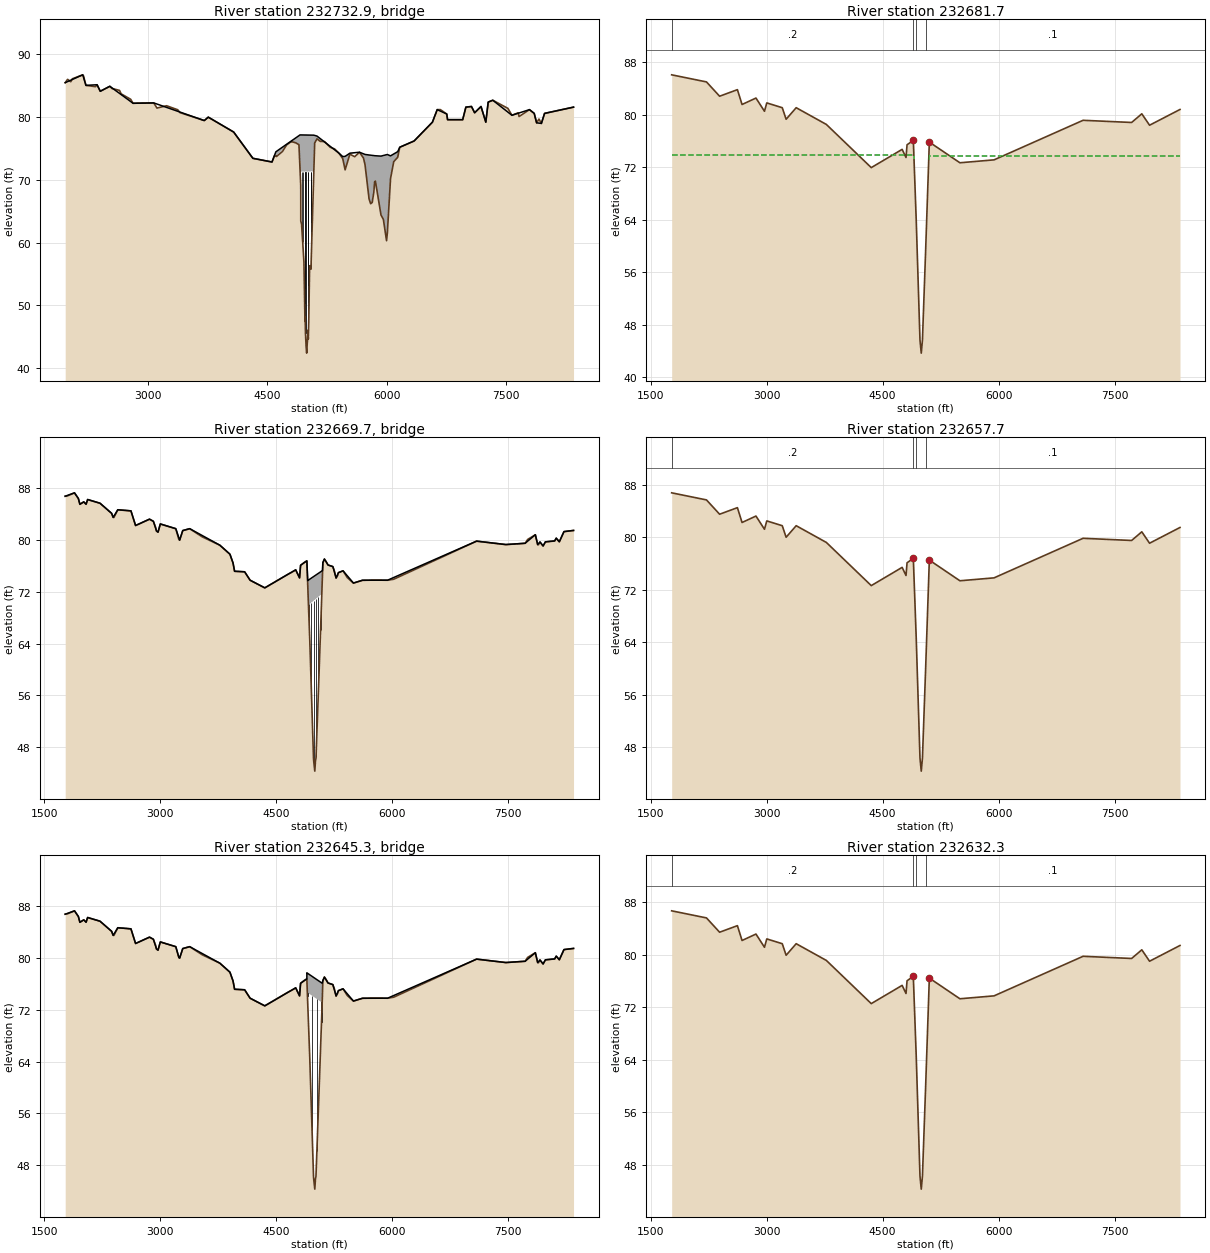
Type RM Length L Ch R = 3 ,232732.9,,,
BEGIN DESCRIPTION:
DAIRY ASHFORD ROAD
Structure ID: W00-78&79
END DESCRIPTION:
Bridge Culvert--1,0,-1,-1, 0
Deck Dist Width WeirC Skew NumUp NumDn MinLoCord MaxHiCord MaxSubmerge Is_Ogee
10,95.8,2.6,0, 60, 60, , , .95, 0, 1,1,,
  1966.9  2186.9  2226.9  2366.9  2406.9  2526.9  2818.6  3078.6  3712.4  3762.4
  4080.8    4322    4562  4610.7    4812  4900.2  4912.8  4922.8  5087.2  5097.8
  5126.2  5403.5  5449.8  5479.8  5539.8  5659.8  5729.8  5779.8  5799.8  5819.8
  5849.8  5859.8  5929.8  5959.8  5999.8  6009.8  6049.8  6089.8  6139.8  6165.5
  6345.5  6575.5  6635.5  6755.4  6765.4  6955.4  6995.4  7065.4  7105.4  7185.4
  7245.4  7275.4  7332.9  7572.9  7792.9  7852.9  7882.9  7942.9  7982.9  8346.4
    85.5   86.75   85.07   85.17   84.13   84.92   82.21   82.27   79.46      80
   77.63   73.44   72.85   74.48   76.27   77.05   77.17   77.17   77.13   77.09
   76.99   74.25   73.72   73.75   74.26   74.41   74.06   73.97   73.94   73.91
   73.86   73.85   73.79   73.89   74.02   74.05   73.83   74.13    74.5   75.21
    76.2    79.2    81.2    80.5    79.6    79.6    81.6    81.7    80.7    81.7
    79.2    82.4    82.7    80.3    81.2    80.6    79.1      79    80.6    81.6
    85.5   86.75   85.07   85.17   84.13   84.92   82.21   82.27   79.46      80
   77.63   73.44   72.85   73.78   76.17   75.61      72   71.31   71.34   75.87
   76.54   74.24    73.4    71.6    74.1    74.4    72.4      67    66.2    66.4
    69.7    69.8    64.4    63.7    60.3    61.5    70.2    72.9    73.6    75.2
    76.2    79.2    81.2    80.5    79.6    79.6    81.6    81.7    80.7    81.7
    79.2    82.4    82.7    80.3    81.2    80.6    79.1      79    80.6    81.6
  1966.9  2186.9  2226.9  2366.9  2406.9  2526.9  2818.6  3078.6  3712.4  3762.4
  4080.8    4322    4562    4812  4900.2  4913.6  4922.8  5087.2  5097.8  5126.2
  5403.5  5449.8  5479.8  5539.8  5659.8  5709.8  5729.8  5779.8  5819.8  5849.8
  5859.8  5929.8  5959.8  5999.8  6009.8  6049.8  6089.8  6139.8  6165.5  6345.5
  6575.5  6635.5  6755.4  6765.4  6955.4  6995.4  7065.4  7105.4  7185.4  7245.4
  7275.4  7332.9  7572.9  7792.9  7852.9  7882.9  7912.9  7942.9  7982.9  8346.4
   86.54   87.79   86.11   86.21   85.17   85.96   83.25   83.31    80.5   81.04
   78.67   74.48   73.89   77.21   77.05   77.17   77.17   77.13   77.09   77.58
   75.28   74.44   73.75   75.14   75.44   74.54   74.06   73.97   73.91   73.86
   73.85   73.79   73.89   74.02   74.05   73.83   74.13   74.64   76.24   77.24
   80.24   82.24   81.54   80.64   80.64   82.64   82.74   81.74   82.74   80.24
   83.44   83.74   81.34   82.24   81.64   80.14   80.74   80.04   81.64   82.64
   86.54   87.79   86.11   86.21   85.17   85.96   83.25   83.31    80.5   81.04
   78.67   74.48   73.89   77.21   76.65   72.81   72.35   72.38   76.91   77.58
   75.28   74.44   72.64   75.14   75.44   74.54   73.44   68.04   67.44   70.74
   70.84   65.44   64.74   61.34   62.54   71.24   73.94   74.64   76.24   77.24
   80.24   82.24   81.54   80.64   80.64   82.64   82.74   81.74   82.74   80.24
   83.44   83.74   81.34   82.24   81.64   80.14   80.74   80.04   81.64   82.64
Pier Skew, UpSta & Num, DnSta & Num=  ,4943, 2 ,4943, 2 , 0 , 0 , 0 ,,
     1.3     1.3
      60   72.31
     1.3     1.3
   61.04   73.35
Pier Skew, UpSta & Num, DnSta & Num=  ,4947.6, 2 ,4947.6, 2 , 0 , 0 , 0 ,,
     1.3     1.3
      59   72.31
     1.3     1.3
   60.04   73.35
Pier Skew, UpSta & Num, DnSta & Num=  ,4978, 2 ,4978, 2 , 0 , 0 , 0 ,,
     1.3     1.3
   46.77    72.3
     1.3     1.3
   47.81   73.34
Pier Skew, UpSta & Num, DnSta & Num=  ,4982.4, 2 ,4982.4, 2 , 0 , 0 , 0 ,,
     1.3     1.3
   44.37    72.3
     1.3     1.3
   45.41   73.34
Pier Skew, UpSta & Num, DnSta & Num=  ,5013, 2 ,5013, 2 , 0 , 0 , 0 ,,
     1.3     1.3
   44.82   72.29
     1.3     1.3
   45.86   73.33
Pier Skew, UpSta & Num, DnSta & Num=  ,5017.5, 2 ,5017.5, 2 , 0 , 0 , 0 ,,
     1.3     1.3
   43.82   72.29
     1.3     1.3
   44.86   73.33
Pier Skew, UpSta & Num, DnSta & Num=  ,5048.1, 2 ,5048.1, 2 , 0 , 0 , 0 ,,
     1.3     1.3
   54.82   72.28
     1.3     1.3
   55.86   73.32
Pier Skew, UpSta & Num, DnSta & Num=  ,5052.2, 2 ,5052.2, 2 , 0 , 0 , 0 ,,
     1.3     1.3
    55.3   72.28
     1.3     1.3
   56.34   73.32
Abutment Skew #Up #Dn= , 2 , 2
  4912.9  4922.9
   71.91   67.99
  4912.9  4922.9
   72.95   69.03
BR Coef= 1 , 1 , 0 ,1.25, 0 ,,,.8,-1,2,0,
WSPro=,,,, 1 ,,,, 0 ,,,, 0 ,,,,-1 ,-1 ,-1 , 0 , 0 , 0 , 0 , 0
BR U #Sta/Elev= 154
  1966.9    85.5  1996.9   86.03  2036.9   85.65  2056.9   86.12  2186.9   86.75
  2196.9   86.57  2226.9   85.07  2346.9   84.86  2366.9   85.17  2406.9   84.13
  2526.9   84.92  2556.9   84.55  2558.6   84.56  2648.6   84.27  2668.6   83.72
  2788.6   82.85  2818.6   82.21  2868.6   82.24  3078.6   82.27  3118.6   81.45
  3238.6   81.82  3378.6   81.18  3408.6   80.72  3712.4   79.46  3762.4      80
  4080.8   77.63    4322   73.44    4562   72.85    4592   73.83  4596.7   73.82
  4610.7   73.78  4616.4   73.76  4617.1   73.72  4683.7   74.42  4693.7   74.53
  4697.2    74.6  4746.2   75.58  4762.4   75.73    4812   76.17  4813.1   76.08
    4863   75.89 4863.09   75.89  4863.2   75.89 4863.31   75.89  4886.2   75.72
  4900.2   75.61  4912.6   72.05  4912.8      72  4912.9   71.97 4913.01   71.94
  4913.1   71.91  4913.6   71.77  4922.8   69.13  4922.9   67.99  4923.3   63.43
  4932.1   62.99  4932.2   62.99    4933   62.95    4943   61.14  4947.6   60.14
    4963   56.88  4975.7   47.53    4978   48.16  4982.4   45.55  4990.3   43.41
  4997.3   42.38  5008.9   44.82    5013   46.02  5017.5   44.62  5024.3   47.95
  5034.2   56.32    5048    55.8  5052.2   56.39  5087.2   71.34  5087.3   71.38
 5087.39   71.42  5087.5   71.47  5087.6   71.51  5087.7   71.56  5097.8   75.87
  5105.8   76.06  5106.6   76.08  5126.2   76.54    5168   76.14  5188.7   76.13
  5220.3   76.11  5230.6   75.98  5230.9   75.98  5236.4   75.91  5237.7   75.89
  5293.2    75.2  5299.4   75.17  5302.8   75.15 5303.19   75.15  5303.3   75.15
 5303.41   75.15  5349.7   74.92  5372.4   74.63  5389.1   74.42  5403.5   74.24
  5403.6   74.23  5449.8    73.4  5479.8    71.6  5489.1   71.99  5539.8    74.1
  5549.1   74.04  5599.8    73.7  5659.8    74.4  5709.8    73.5  5729.8    72.4
  5779.8      67  5799.8    66.2  5819.8    66.4  5839.8      68  5849.8    69.7
  5850.2    69.7  5859.8    69.8  5929.8    64.4  5930.2   64.39  5959.8    63.7
  5999.8    60.3  6009.8    61.5  6010.2   61.59  6040.2   68.11  6049.8    70.2
  6089.8    72.9  6139.8    73.6  6165.5    75.2  6281.1   75.84  6345.5    76.2
  6575.5    79.2  6635.5    81.2  6675.4    81.2  6755.4    80.5  6765.4    79.6
  6955.4    79.6  6995.4    81.6  7065.4    81.7  7105.4    80.7  7185.4    81.7
  7245.4    79.2  7275.4    82.4  7332.9    82.7  7522.9    81.4  7572.9    80.3
  7652.9    80.7  7662.9    80.1  7792.9    81.2  7852.9    80.6  7882.9    79.1
  7912.9    79.7  7942.9      79  7982.9    80.6  8346.4    81.6
BR U #Mann= 4
  1966.9      .2  4900.2      .1  4947.6     .04  5034.2      .1
BR U Banks=4900.2,5097.8
BR D #Sta/Elev= 154
  1966.9   86.54  1996.9   87.07  2036.9   86.69  2056.9   87.16  2186.9   87.79
  2196.9   87.61  2226.9   86.11  2346.9    85.9  2366.9   86.21  2406.9   85.17
  2526.9   85.96  2556.9   85.59  2558.6    85.6  2648.6   85.31  2668.6   84.76
  2788.6   83.89  2818.6   83.25  2868.6   83.28  3078.6   83.31  3118.6   82.49
  3238.6   82.86  3378.6   82.22  3408.6   81.76  3712.4    80.5  3762.4   81.04
  4080.8   78.67    4322   74.48    4562   73.89    4592   74.87  4596.7   74.86
  4610.7   74.82  4616.4    74.8  4617.1   74.76  4683.7   75.46  4693.7   75.57
  4697.2   75.64  4746.2   76.62  4762.4   76.77    4812   77.21  4813.1   77.12
    4863   76.93 4863.09   76.93  4863.2   76.93 4863.31   76.93  4886.2   76.76
  4900.2   76.65  4912.6   73.09  4912.8   73.04  4912.9   73.01 4913.01   72.98
  4913.1   72.95  4913.6   72.81  4922.8   70.17  4922.9   69.03  4923.3   64.47
  4932.1   64.03  4932.2   64.03    4933   63.99    4943   62.18  4947.6   61.18
    4963   57.92  4975.7   48.57    4978    49.2  4982.4   46.59  4990.3   44.45
  4997.3   43.42  5008.9   45.86    5013   47.06  5017.5   45.66  5024.3   48.99
  5034.2   57.36    5048   56.84  5052.2   57.43  5087.2   72.38  5087.3   72.42
 5087.39   72.46  5087.5   72.51  5087.6   72.55  5087.7    72.6  5097.8   76.91
  5105.8    77.1  5106.6   77.12  5126.2   77.58    5168   77.18  5188.7   77.17
  5220.3   77.15  5230.6   77.02  5230.9   77.02  5236.4   76.95  5237.7   76.93
  5293.2   76.24  5299.4   76.21  5302.8   76.19 5303.19   76.19  5303.3   76.19
 5303.41   76.19  5349.7   75.96  5372.4   75.67  5389.1   75.46  5403.5   75.28
  5403.6   75.27  5449.8   74.44  5479.8   72.64  5489.1   73.03  5539.8   75.14
  5549.1   75.08  5599.8   74.74  5659.8   75.44  5709.8   74.54  5729.8   73.44
  5779.8   68.04  5799.8   67.24  5819.8   67.44  5839.8   69.04  5849.8   70.74
  5850.2   70.74  5859.8   70.84  5929.8   65.44  5930.2   65.43  5959.8   64.74
  5999.8   61.34  6009.8   62.54  6010.2   62.63  6040.2   69.15  6049.8   71.24
  6089.8   73.94  6139.8   74.64  6165.5   76.24  6281.1   76.88  6345.5   77.24
  6575.5   80.24  6635.5   82.24  6675.4   82.24  6755.4   81.54  6765.4   80.64
  6955.4   80.64  6995.4   82.64  7065.4   82.74  7105.4   81.74  7185.4   82.74
  7245.4   80.24  7275.4   83.44  7332.9   83.74  7522.9   82.44  7572.9   81.34
  7652.9   81.74  7662.9   81.14  7792.9   82.24  7852.9   81.64  7882.9   80.14
  7912.9   80.74  7942.9   80.04  7982.9   81.64  8346.4   82.64
BR D #Mann= 4
  1966.9      .2  4900.2      .1  4947.6     .04  5034.2      .1
BR D Banks=4900.2,5097.8
BC Design=,, 0 ,, 0 ,,,,,,
BC HTab HWMax=86.75

Type RM Length L Ch R = 1 ,232681.7,24,24,24
BEGIN DESCRIPTION:
Upstream Section of Bridge/Culvert/Weir
END DESCRIPTION:
XS GIS Cut Line= 3
      3045015.92     13843412.34      3045149.52     13840188.31
      3045147.67     13836842.01
#Sta/Elev= 30
  1773.2   86.05  2223.2   84.97  2393.2   82.79  2623.2   83.79  2683.2   81.53
  2863.2   82.51  2973.2    80.5  3003.2   81.77  3203.2   81.04  3253.2   79.28
  3383.2   81.04  3773.4   78.49  4354.1   71.91  4753.5   74.69  4803.5   73.45
 4816.79   75.39 4897.99   76.07 4935.59   63.89 4984.19   45.59 5000.69   43.64
 5015.79    45.6 5057.29   59.31 5104.99    75.8  5500.3   72.65  5941.7   73.09
  7092.9   79.12  7720.8   78.79  7852.6   80.11  7952.6   78.37  8346.3   80.77
#Mann= 4 ,-1 , 0
  1773.2      .2       0 4897.99      .1       0 4935.59     .04       0
 5057.29      .1       0
#XS Ineff= 2 , 0
          4906.6    73.9  5097.1            73.7
Permanent Ineff=
       F       F
Bank Sta=4897.99,5104.99
XS Rating Curve= 0
Exp/Cntr=.5,.3

Type RM Length L Ch R = 3 ,232669.7,,,
BEGIN DESCRIPTION:
46" PIPELINE
END DESCRIPTION:
Bridge Culvert--1,0,-1,-1, 0
Deck Dist Width WeirC Skew NumUp NumDn MinLoCord MaxHiCord MaxSubmerge Is_Ogee
10,4,2.6,0, 60, 60, , , .95, 0, 1,1,,
  1773.2  1893.2  1943.2  1963.2  2013.2  2043.2  2063.2  2223.2  2373.2  2393.2
  2453.2  2623.2  2683.2  2863.2  2913.2  2953.2  2973.2  3003.2  3203.2  3253.2
  3293.2  3383.2  3773.4  3903.4  3943.4  3963.4  4093.4  4164.1  4354.1  4753.5
  4803.5 4816.79 4897.99 4909.29 4918.59 5091.39 5100.39 5104.99 5124.99 5171.39
  5234.1    5276    5306    5366  5500.3  5616.6  5941.7  7092.9  7470.8  7720.8
  7852.6  7882.6  7912.6  7952.6  7982.6  8102.6  8122.6  8162.6  8222.6  8346.3
   86.74   87.26   86.39   85.49   85.87    85.5   86.23   85.66    84.1   83.48
   84.65   84.48   82.22    83.2   82.87   81.38   81.19   82.46   81.73   79.97
   81.44   81.73   79.18   77.79   76.44   75.16   75.08   73.78    72.6   75.38
   74.14   76.08   76.77   73.72    73.8    75.2   75.27    76.5   77.05   76.13
   75.88   74.12   74.95   75.23   73.34   73.77   73.78   79.81   79.28   79.48
    80.8   79.28   79.68   79.06    79.7   79.84   80.27   79.71   81.28   81.46
   86.73   87.25   86.38   85.48   85.86   85.49   86.22   85.65   84.09   83.47
   84.64   84.47   82.21   83.19   82.86   81.37   81.18   82.45   81.72   79.96
   81.43   81.72   79.17   77.78   76.43   75.15   75.07   73.77   72.59   75.37
   74.13   76.07   76.75   73.01   69.96   71.66   74.85   76.48   77.03   76.12
   75.87   74.11   74.94   75.22   73.33   73.76   73.77    79.8   79.27   79.47
   80.79   79.27   79.67   79.05   79.69   79.83   80.26    79.7   81.27   81.45
  1773.2  1893.2  1943.2  1963.2  2013.2  2043.2  2063.2  2223.2  2373.2  2393.2
  2453.2  2623.2  2683.2  2863.2  2913.2  2953.2  2973.2  3003.2  3203.2  3253.2
  3293.2  3383.2  3773.4  3903.4  3943.4  3963.4  4093.4  4164.1  4354.1  4753.5
  4803.5 4816.79 4897.99 4909.29 4918.59 5091.39 5100.39 5104.99 5124.99 5171.39
  5234.1    5276    5306    5366  5500.3  5616.6  5941.7  7092.9  7470.8  7720.8
  7852.6  7882.6  7912.6  7952.6  7982.6  8102.6  8122.6  8162.6  8222.6  8346.3
   86.74   87.26   86.39   85.49   85.87    85.5   86.23   85.66    84.1   83.48
   84.65   84.48   82.22    83.2   82.87   81.38   81.19   82.46   81.73   79.97
   81.44   81.73   79.18   77.79   76.44   75.16   75.08   73.78    72.6   75.38
   74.14   76.08   76.77   73.72    73.8    75.2   75.27    76.5   77.05   76.13
   75.88   74.12   74.95   75.23   73.34   73.77   73.78   79.81   79.28   79.48
    80.8   79.28   79.68   79.06    79.7   79.84   80.27   79.71   81.28   81.46
   86.74   87.26   86.39   85.49   85.87    85.5   86.23   85.66    84.1   83.48
   84.65   84.48   82.22    83.2   82.87   81.38   81.19   82.46   81.73   79.97
   81.44   81.73   79.18   77.79   76.44   75.16   75.08   73.78    72.6   75.38
   74.14   76.08   76.76   73.02   69.97   71.67   74.86   76.49   77.04   76.13
   75.88   74.12   74.95   75.23   73.34   73.77   73.78   79.81   79.28   79.48
    80.8   79.28   79.68   79.06    79.7   79.84   80.27   79.71   81.28   81.46
Pier Skew, UpSta & Num, DnSta & Num=  ,4927.1, 2 ,4927.1, 2 , 0 , 0 , 0 ,,
     1.5     1.5
   66.02   71.03
     1.5     1.5
   66.03   71.04
Pier Skew, UpSta & Num, DnSta & Num=  ,4956.4, 2 ,4956.4, 2 , 0 , 0 , 0 ,,
     1.5     1.5
   55.46   71.27
     1.5     1.5
   55.47   71.28
Pier Skew, UpSta & Num, DnSta & Num=  ,4986.3, 2 ,4986.3, 2 , 0 , 0 , 0 ,,
     1.5     1.5
   44.82   71.51
     1.5     1.5
   44.83   71.52
Pier Skew, UpSta & Num, DnSta & Num=  ,5016.3, 2 ,5016.3, 2 , 0 , 0 , 0 ,,
     1.5     1.5
   45.27   71.75
     1.5     1.5
   45.28   71.76
Pier Skew, UpSta & Num, DnSta & Num=  ,5045.9, 2 ,5045.9, 2 , 0 , 0 , 0 ,,
     1.5     1.5
   54.98   71.99
     1.5     1.5
   54.99      72
Pier Skew, UpSta & Num, DnSta & Num=  ,5075.2, 2 ,5075.2, 2 , 0 , 0 , 0 ,,
     1.5     1.5
   64.86    72.4
     1.5     1.5
   64.87   72.41
BR Coef= 1 , 1 , 0 ,1.25, 0 ,,,.8,0,2,0,
WSPro=,,,, 1 ,,,, 0 ,,,, 0 ,,,,-1 ,-1 ,-1 , 0 , 0 , 0 , 0 , 0
BR U #Sta/Elev= 96
  1773.2   86.73  1803.2   86.79  1893.2   87.25  1943.2   86.38  1963.2   85.48
  2013.2   85.86  2043.2   85.49  2063.2   86.22  2223.2   85.65  2373.2   84.09
  2393.2   83.47  2403.2   83.46  2453.2   84.64  2623.2   84.47  2683.2   82.21
  2863.2   83.19  2913.2   82.86  2943.2   81.92  2953.2   81.37  2973.2   81.18
  3003.2   82.45  3203.2   81.72  3243.2   80.04  3253.2   79.96  3293.2   81.43
  3383.2   81.72  3543.4   80.48  3773.4   79.17  3903.4   77.78  3943.4   76.43
  3963.4   75.15  4093.4   75.07  4164.1   73.77  4354.1   72.59  4659.7   74.74
  4688.2   74.92  4703.5   75.01  4753.5   75.37  4803.5   74.13 4816.79   76.07
 4841.79   76.31  4862.8    76.5 4866.99   76.54  4872.8   76.58  4882.8   76.65
 4897.99   76.75 4909.29   73.01  4909.4   72.98 4909.49   72.95 4918.59   69.94
 4935.59   64.57 4984.19   46.27 4986.79   45.85 5000.69   44.32 5009.29    45.9
 5015.79   46.28 5057.29   59.99 5091.39   71.66 5100.28   74.81 5100.39   74.85
 5100.49   74.89 5104.99   76.48  5112.8   76.69 5124.99   77.03  5141.9   76.74
 5147.89   76.64 5171.39   76.12  5234.1   75.87  5254.1   75.21    5256   75.12
    5276   74.11    5296    74.5  5303.2   74.82    5306   74.94    5366   75.22
  5420.3   74.19  5500.3   73.33  5616.6   73.76  5781.7    73.8  5941.7   73.77
  6021.7   73.93  7092.9    79.8  7470.8   79.27  7720.8   79.47  7752.6   80.06
  7852.6   80.79  7882.6   79.27  7892.6   79.24  7912.6   79.67  7952.6   79.05
  7982.6   79.69  8102.6   79.83  8122.6   80.26  8162.6    79.7  8222.6   81.27
  8346.3   81.45
BR U #Mann= 4
  1773.2      .2 4897.99      .1 4935.59     .04 5057.29      .1
BR U Banks=4897.99,5104.99
BR D #Sta/Elev= 96
  1773.2   86.74  1803.2    86.8  1893.2   87.26  1943.2   86.39  1963.2   85.49
  2013.2   85.87  2043.2    85.5  2063.2   86.23  2223.2   85.66  2373.2    84.1
  2393.2   83.48  2403.2   83.47  2453.2   84.65  2623.2   84.48  2683.2   82.22
  2863.2    83.2  2913.2   82.87  2943.2   81.93  2953.2   81.38  2973.2   81.19
  3003.2   82.46  3203.2   81.73  3243.2   80.05  3253.2   79.97  3293.2   81.44
  3383.2   81.73  3543.4   80.49  3773.4   79.18  3903.4   77.79  3943.4   76.44
  3963.4   75.16  4093.4   75.08  4164.1   73.78  4354.1    72.6  4659.7   74.75
  4688.2   74.93  4703.5   75.02  4753.5   75.38  4803.5   74.14 4816.79   76.08
 4841.79   76.32  4862.8   76.51 4866.99   76.55  4872.8   76.59  4882.8   76.66
 4897.99   76.76 4909.29   73.02  4909.4   72.99 4909.49   72.96 4918.59   69.95
 4935.59   64.58 4984.19   46.28 4986.79   45.86 5000.69   44.33 5009.29   45.91
 5015.79   46.29 5057.29      60 5091.39   71.67 5100.28   74.82 5100.39   74.86
 5100.49    74.9 5104.99   76.49  5112.8    76.7 5124.99   77.04  5141.9   76.75
 5147.89   76.65 5171.39   76.13  5234.1   75.88  5254.1   75.22    5256   75.13
    5276   74.12    5296   74.51  5303.2   74.83    5306   74.95    5366   75.23
  5420.3    74.2  5500.3   73.34  5616.6   73.77  5781.7   73.81  5941.7   73.78
  6021.7   73.94  7092.9   79.81  7470.8   79.28  7720.8   79.48  7752.6   80.07
  7852.6    80.8  7882.6   79.28  7892.6   79.25  7912.6   79.68  7952.6   79.06
  7982.6    79.7  8102.6   79.84  8122.6   80.27  8162.6   79.71  8222.6   81.28
  8346.3   81.46
BR D #Mann= 4
  1773.2      .2 4897.99      .1 4935.59     .04 5057.29      .1
BR D Banks=4897.99,5104.99
BC Design=,, 0 ,, 0 ,,,,,,
BC HTab HWMax=86.57

Type RM Length L Ch R = 1 ,232657.7,25.4,25.4,25.4
BEGIN DESCRIPTION:
Downstream Section of Bridge/Culvert/Weir
END DESCRIPTION:
XS GIS Cut Line= 3
      3045039.91     13843411.84      3045173.52     13840187.81
      3045171.66      13836841.5
#Sta/Elev= 30
  1773.2   86.74  2223.2   85.66  2393.2   83.48  2623.2   84.48  2683.2   82.22
  2863.2    83.2  2973.2   81.19  3003.2   82.46  3203.2   81.73  3253.2   79.97
  3383.2   81.73  3773.4   79.18  4354.1    72.6  4753.5   75.38  4803.5   74.14
 4816.79   76.08 4897.99   76.76 4935.59   64.58 4984.19   46.28 5000.69   44.33
 5015.79   46.29 5057.29      60 5104.99   76.49  5500.3   73.34  5941.7   73.78
  7092.9   79.81  7720.8   79.48  7852.6    80.8  7952.6   79.06  8346.3   81.46
#Mann= 4 ,-1 , 0
  1773.2      .2       0 4897.99      .1       0 4935.59     .04       0
 5057.29      .1       0
#XS Ineff= 2 , 0
          4906.6    73.9  5097.1            73.7
Permanent Ineff=
       F       F
Bank Sta=4897.99,5104.99
XS Rating Curve= 0
Exp/Cntr=.5,.3

Type RM Length L Ch R = 3 ,232645.3,,,
BEGIN DESCRIPTION:
2-36" PIPELINES
END DESCRIPTION:
Bridge Culvert--1,0,-1,-1, 0
Deck Dist Width WeirC Skew NumUp NumDn MinLoCord MaxHiCord MaxSubmerge Is_Ogee
10,6,2.6,0, 60, 60, , , .95, 0, 1,1,,
  1773.2  1893.2  1943.2  1963.2  2013.2  2043.2  2063.2  2223.2  2373.2  2393.2
  2453.2  2623.2  2683.2  2863.2  2913.2  2953.2  2973.2  3003.2  3203.2  3243.2
  3253.2  3293.2  3383.2  3773.4  3903.4  3943.4  3963.4  4093.4  4164.1  4354.1
  4753.5  4803.5 4816.79 4897.79 4897.89 4903.99 5095.99 5104.99 5124.99 5171.39
  5234.1    5276    5306    5366  5500.3  5616.6  5941.7  7092.9  7470.8  7720.8
  7852.6  7882.6  7912.6  7952.6  7982.6  8102.6  8122.6  8162.6  8222.6  8346.3
   86.74   87.26   86.39   85.49   85.87    85.5   86.23   85.66    84.1   83.48
   84.65   84.48   82.22    83.2   82.87   81.38   81.19   82.46   81.73   80.05
   79.97   81.44   81.73   79.18   77.79   76.44   75.16   75.08   73.78    72.6
   75.38   74.14   76.08   76.76    77.7   77.65   76.09    76.5   77.04   76.13
   75.88   74.12   74.95   75.23   73.34   73.77   73.78   79.81   79.28   79.48
    80.8   79.28   79.68   79.06    79.7   79.84   80.27   79.71   81.28   81.46
   86.74   87.26   86.39   85.49   85.87    85.5   86.23   85.66    84.1   83.48
   84.65   84.48   82.22    83.2   82.87   81.38   81.19   82.46   81.73   80.05
   79.97   81.44   81.73   79.18   77.79   76.44   75.16   75.08   73.78    72.6
   75.38   74.14   76.08   76.76   76.73   74.67   73.09   76.49   77.04   76.13
   75.88   74.12   74.95   75.23   73.34   73.77   73.78   79.81   79.28   79.48
    80.8   79.28   79.68   79.06    79.7   79.84   80.27   79.71   81.28   81.46
  1773.2  1893.2  1943.2  1963.2  2013.2  2043.2  2063.2  2223.2  2373.2  2393.2
  2453.2  2623.2  2683.2  2863.2  2913.2  2953.2  2973.2  3003.2  3203.2  3243.2
  3253.2  3293.2  3383.2  3773.4  3903.4  3943.4  3963.4  4093.4  4164.1  4354.1
  4753.5  4803.5 4816.79 4897.79 4897.89 4903.99 5095.99 5104.99 5124.99 5171.39
  5234.1    5276    5306    5366  5500.3  5616.6  5941.7  7092.9  7470.8  7720.8
  7852.6  7882.6  7912.6  7952.6  7982.6  8102.6  8122.6  8162.6  8222.6  8346.3
   86.74   87.26   86.39   85.49   85.87    85.5   86.23   85.66    84.1   83.48
   84.65   84.48   82.22    83.2   82.87   81.38   81.19   82.46   81.73   80.05
   79.97   81.44   81.73   79.18   77.79   76.44   75.16   75.08   73.78    72.6
   75.38   74.14   76.08   76.76    77.7   77.65   76.09    76.5   77.04   76.13
   75.88   74.12   74.95   75.23   73.34   73.77   73.78   79.81   79.28   79.48
    80.8   79.28   79.68   79.06    79.7   79.84   80.27   79.71   81.28   81.46
   86.74   87.26   86.39   85.49   85.87    85.5   86.23   85.66    84.1   83.48
   84.65   84.48   82.22    83.2   82.87   81.38   81.19   82.46   81.73   80.05
   79.97   81.44   81.73   79.18   77.79   76.44   75.16   75.08   73.78    72.6
   75.38   74.14   76.08   76.76   76.73   74.67   73.09   76.49   77.04   76.13
   75.88   74.12   74.95   75.23   73.34   73.77   73.78   79.81   79.28   79.48
    80.8   79.28   79.68   79.06    79.7   79.84   80.27   79.71   81.28   81.46
Pier Skew, UpSta & Num, DnSta & Num=  ,4905.9, 2 ,4905.9, 2 , 0 , 0 , 0 ,,
     1.5     1.5
   72.82   75.66
     1.5     1.5
   72.82   75.66
Pier Skew, UpSta & Num, DnSta & Num=  ,4965.1, 2 ,4965.1, 2 , 0 , 0 , 0 ,,
     1.5     1.5
   52.19   75.16
     1.5     1.5
   52.19   75.16
Pier Skew, UpSta & Num, DnSta & Num=  ,5027.8, 2 ,5027.8, 2 , 0 , 0 , 0 ,,
     1.5     1.5
   49.01   74.65
     1.5     1.5
   49.01   74.65
Pier Skew, UpSta & Num, DnSta & Num=  ,5087.3, 2 ,5087.3, 2 , 0 , 0 , 0 ,,
     1.5     1.5
   68.88   74.17
     1.5     1.5
   68.88   74.17
BR Coef= 1 , 1 , 0 ,1.25, 0 ,,,.8,0,2,0,
WSPro=,,,, 1 ,,,, 0 ,,,, 0 ,,,,-1 ,-1 ,-1 , 0 , 0 , 0 , 0 , 0
BR U #Sta/Elev= 91
  1773.2   86.74  1803.2    86.8  1893.2   87.26  1943.2   86.39  1963.2   85.49
  2013.2   85.87  2043.2    85.5  2063.2   86.23  2223.2   85.66  2373.2    84.1
  2393.2   83.48  2403.2   83.47  2453.2   84.65  2623.2   84.48  2683.2   82.22
  2863.2    83.2  2913.2   82.87  2943.2   81.93  2953.2   81.38  2973.2   81.19
  3003.2   82.46  3203.2   81.73  3243.2   80.05  3253.2   79.97  3293.2   81.44
  3383.2   81.73  3543.4   80.49  3773.4   79.18  3903.4   77.79  3943.4   76.44
  3963.4   75.16  4093.4   75.08  4164.1   73.78  4354.1    72.6  4659.7   74.75
  4688.2   74.93  4703.5   75.02  4753.5   75.38  4803.5   74.14 4816.79   76.08
 4841.79   76.32 4866.99   76.55 4897.79   76.76 4897.89   76.73    4898   76.69
 4898.09   76.66 4903.99   74.67 4935.59   64.58 4984.19   46.28 4986.79   45.86
 5000.69   44.33 5009.29   45.91 5015.79   46.29 5057.29      60 5095.99   73.07
 5104.99   76.49 5109.58   76.62 5109.69   76.62 5109.79   76.62 5124.99   77.04
 5147.89   76.65 5171.39   76.13  5234.1   75.88  5254.1   75.22    5256   75.13
    5276   74.12    5296   74.51  5303.2   74.83    5306   74.95    5366   75.23
  5420.3    74.2  5500.3   73.34  5616.6   73.77  5781.7   73.81  5941.7   73.78
  6021.7   73.94  7092.9   79.81  7470.8   79.28  7720.8   79.48  7752.6   80.07
  7852.6    80.8  7882.6   79.28  7892.6   79.25  7912.6   79.68  7952.6   79.06
  7982.6    79.7  8102.6   79.84  8122.6   80.27  8162.6   79.71  8222.6   81.28
  8346.3   81.46
BR U #Mann= 4
  1773.2      .2 4897.79      .1 4935.59     .04 5057.29      .1
BR U Banks=4897.79,5104.99
BR D #Sta/Elev= 91
  1773.2   86.74  1803.2    86.8  1893.2   87.26  1943.2   86.39  1963.2   85.49
  2013.2   85.87  2043.2    85.5  2063.2   86.23  2223.2   85.66  2373.2    84.1
  2393.2   83.48  2403.2   83.47  2453.2   84.65  2623.2   84.48  2683.2   82.22
  2863.2    83.2  2913.2   82.87  2943.2   81.93  2953.2   81.38  2973.2   81.19
  3003.2   82.46  3203.2   81.73  3243.2   80.05  3253.2   79.97  3293.2   81.44
  3383.2   81.73  3543.4   80.49  3773.4   79.18  3903.4   77.79  3943.4   76.44
  3963.4   75.16  4093.4   75.08  4164.1   73.78  4354.1    72.6  4659.7   74.75
  4688.2   74.93  4703.5   75.02  4753.5   75.38  4803.5   74.14 4816.79   76.08
 4841.79   76.32 4866.99   76.55 4897.79   76.76 4897.89   76.73    4898   76.69
 4898.09   76.66 4903.99   74.67 4935.59   64.58 4984.19   46.28 4986.79   45.86
 5000.69   44.33 5009.29   45.91 5015.79   46.29 5057.29      60 5095.99   73.07
 5104.99   76.49 5109.58   76.62 5109.69   76.62 5109.79   76.62 5124.99   77.04
 5147.89   76.65 5171.39   76.13  5234.1   75.88  5254.1   75.22    5256   75.13
    5276   74.12    5296   74.51  5303.2   74.83    5306   74.95    5366   75.23
  5420.3    74.2  5500.3   73.34  5616.6   73.77  5781.7   73.81  5941.7   73.78
  6021.7   73.94  7092.9   79.81  7470.8   79.28  7720.8   79.48  7752.6   80.07
  7852.6    80.8  7882.6   79.28  7892.6   79.25  7912.6   79.68  7952.6   79.06
  7982.6    79.7  8102.6   79.84  8122.6   80.27  8162.6   79.71  8222.6   81.28
  8346.3   81.46
BR D #Mann= 4
  1773.2      .2 4897.79      .1 4935.59     .04 5057.29      .1
BR D Banks=4897.79,5104.99
BC Design=,, 0 ,, 0 ,,,,,,
BC HTab HWMax=87.26

Type RM Length L Ch R = 1 ,232632.3,834.3,834.3,834.3
BEGIN DESCRIPTION:
Downstream Section of Bridge/Culvert/Weir
END DESCRIPTION:
XS GIS Cut Line= 3
       3045096.7     13843412.45      3045198.92     13840187.28
      3045203.34     13836840.97
#Sta/Elev= 30
  1773.2   86.71  2223.2   85.63  2393.2   83.45  2623.2   84.45  2683.2   82.19
  2863.2   83.17  2973.2   81.16  3003.2   82.43  3203.2    81.7  3253.2   79.94
  3383.2    81.7  3773.4   79.15  4354.1   72.57  4753.5   75.35  4803.5   74.11
 4816.79   76.05 4897.79   76.73 4935.59   64.55 4984.19   46.25 5000.69    44.3
 5015.79   46.26 5057.29   59.97 5104.99   76.46  5500.3   73.31  5941.7   73.75
  7092.9   79.78  7720.8   79.45  7852.6   80.77  7952.6   79.03  8346.3   81.43
#Mann= 4 ,-1 , 0
  1773.2      .2       0 4897.79      .1       0 4935.59     .04       0
 5057.29      .1       0
#XS Ineff= 2 , 0
          4906.4    73.9  5098.2            73.7
Permanent Ineff=
       F       F
Bank Sta=4897.79,5104.99
XS Rating Curve= 0
Exp/Cntr=.5,.3