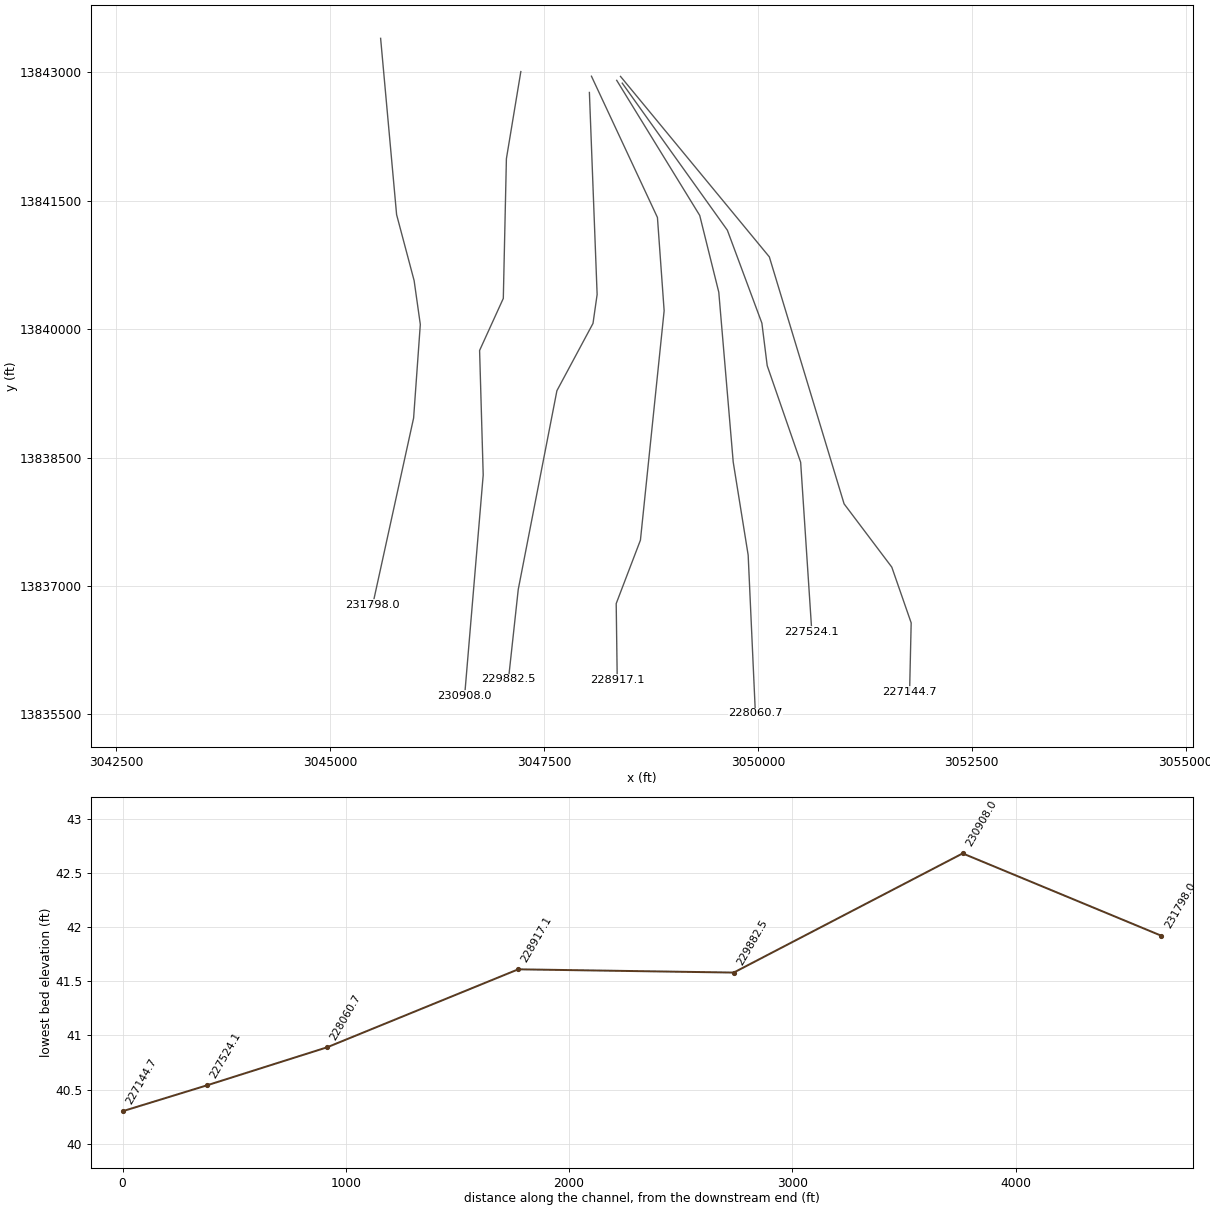
HEC-RAS study W100-00-00.prj: W100-00-00

--- W100-00-00.g01 (geometry) --- (continued)

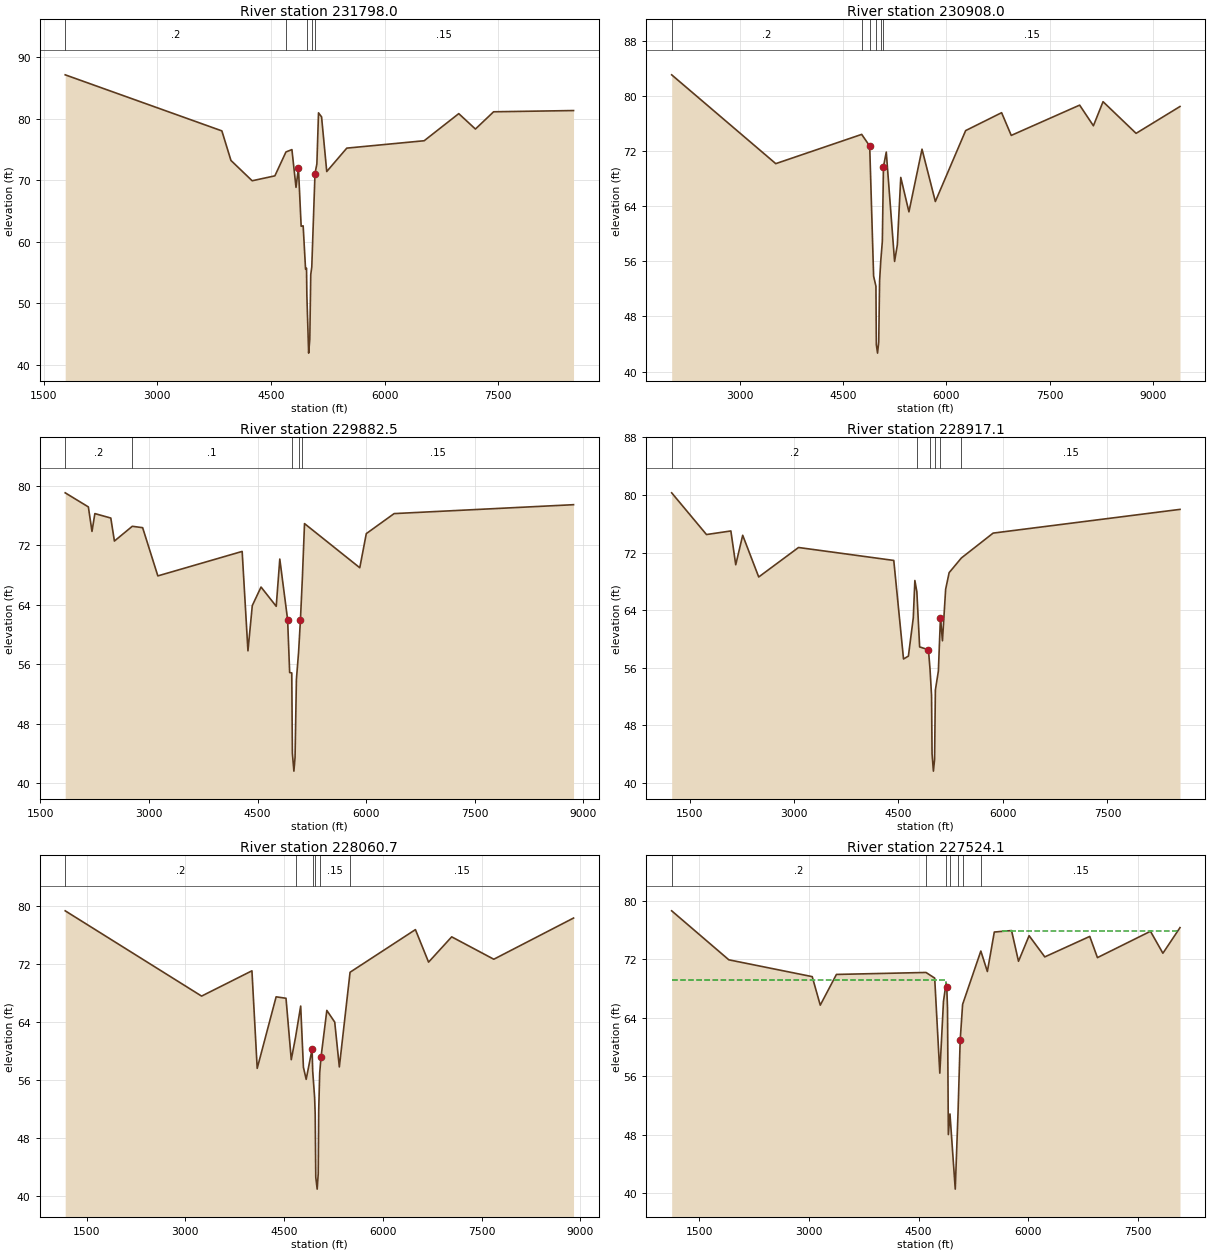
Type RM Length L Ch R = 1 ,231798.0,959.5,890,826.7
BEGIN DESCRIPTION:
Cross Section 231798.0
END DESCRIPTION:
XS GIS Cut Line= 6
      3045591.37     13843398.38      3045778.11     13841338.28
      3045982.91     13840567.25       3046055.2     13840055.23
      3045976.89     13838961.93      3045499.31     13836781.66
#Sta/Elev= 30
  1783.3    87.1  3851.8      78  3971.8    73.2  4251.8    69.9  4551.8    70.7
  4698.3   74.58  4776.8   74.96  4830.9   68.83  4862.7      72  4898.7   62.52
  4925.2   62.58  4956.9   55.54  4969.6    55.7    4974   51.36  4997.6   41.92
  5012.9   44.21  5025.5   54.68    5039    55.9  5080.2   70.63  5081.4   71.08
  5106.3   72.64  5127.9   80.93  5168.2   80.27  5236.7    71.4  5501.2    75.2
  6523.1    76.4  6979.7    80.8  7199.7    78.3  7439.7    81.1  8495.1    81.3
#Mann= 5 ,-1 , 0
  1783.3      .2       0  4698.3      .1       0  4969.6    .055       0
    5039     .15       0  5080.2     .15       0
Bank Sta=4862.7,5081.4
XS Rating Curve= 0
Exp/Cntr=.3,.1

Type RM Length L Ch R = 1 ,230908.0,1031.9,1025.5,1021.4
BEGIN DESCRIPTION:
Cross Section 230908.0
END DESCRIPTION:
XS GIS Cut Line= 6
      3047229.82     13843009.85      3047061.15     13841991.85
      3047025.01     13840359.43      3046747.92     13839751.04
      3046790.09     13838296.32      3046573.23     13835718.18
#Sta/Elev= 30
  2009.8    83.1  3521.7    70.2  4769.8   74.45  4886.4   72.75    4890   71.44
  4942.9   53.86  4976.7   52.39  4982.6   43.89  5000.1   42.68  5017.3   44.32
  5029.7   53.13  5046.3      56  5069.7   58.91  5080.2   65.94  5085.9   69.76
  5126.8   71.88  5247.4      56  5287.4    58.4  5337.4    68.2  5455.9    63.2
  5645.9    72.3  5839.6    64.7  6279.6      75  6802.1    77.6  6942.1    74.3
  7935.3    78.7  8135.3    75.7  8275.3    79.2  8755.3    74.6    9393    78.5
#Mann= 6 ,-1 , 0
  2009.8      .2       0  4769.8      .1       0    4890     .12       0
  4976.7    .055       0  5046.3     .12       0  5080.2     .15       0
Bank Sta=4886.4,5085.9
XS Rating Curve= 0
Exp/Cntr=.3,.1

Type RM Length L Ch R = 1 ,229882.5,887.8,965.4,1030.2
BEGIN DESCRIPTION:
Cross Section 229882.5
END DESCRIPTION:
XS GIS Cut Line= 6
      3048030.97     13842765.89      3048121.32     13840404.61
      3048073.13     13840067.28      3047651.47     13839281.19
       3047199.7     13836959.06      3047085.25     13835907.93
#Sta/Elev= 30
  1842.5    79.1  2162.5    77.2  2212.5    73.9  2252.5    76.3  2472.5    75.7
  2522.5    72.6  2769.8   74.59  2912.5    74.4  3122.5    67.9  4287.6    71.2
  4367.6    57.8  4427.6    63.9  4548.4    66.4  4758.4    63.8  4807.6   70.17
  4915.7   62.01  4943.9   54.87    4973   54.82  4981.6   43.98  5002.4   41.58
  5018.4   43.41  5037.2   53.94  5067.6   57.66    5093      62  5119.8   67.66
  5149.3   74.95  5912.9      69  6002.9    73.6  6387.5    76.3  8866.4    77.5
#Mann= 5 ,-1 , 0
  1842.5      .2       0  2769.8      .1       0    4973    .055       0
  5067.6      .1       0  5119.8     .15       0
Bank Sta=4915.7,5093
XS Rating Curve= 0
Exp/Cntr=.3,.1

Type RM Length L Ch R = 1 ,228917.1,825.9,856.4,864.6
BEGIN DESCRIPTION:
Cross Section 228917.1
END DESCRIPTION:
XS GIS Cut Line= 6
      3048055.06     13842955.64      3048826.09     13841305.15
       3048904.4     13840214.86      3048627.31     13837534.32
       3048344.2     13836793.41      3048356.25     13835904.91
#Sta/Elev= 30
  1242.8    80.3  1742.8    74.5  2092.8      75  2162.8    70.3  2262.8    74.4
  2492.8    68.6  3064.5    72.7  4432.2    70.9  4572.2    57.2  4642.2    57.6
  4712.2    62.9  4735.1   68.11  4763.6   66.55  4803.5   58.88  4930.2   58.48
  4953.2   55.74  4974.7   52.12  4981.9   44.03  5001.5   41.61  5018.2   43.22
  5029.6   52.88  5072.7   55.53  5102.4   62.94  5102.8   62.92  5131.2   59.73
  5177.2    66.9  5227.2    69.2  5402.8   71.24  5858.9    74.7  8542.4      78
#Mann= 6 ,-1 , 0
  1242.8      .2       0  4763.6      .1       0  4953.2     .06       0
  5029.6     .12       0  5102.8      .2       0  5402.8     .15       0
Bank Sta=4930.2,5102.4
XS Rating Curve= 0
Exp/Cntr=.3,.1

Type RM Length L Ch R = 1 ,228060.7,514.2,536.6,553.6
BEGIN DESCRIPTION:
Cross Section 228060.7
END DESCRIPTION:
XS GIS Cut Line= 6
      3048350.22     13842907.45      3049320.03     13841329.24
      3049542.91     13840431.71      3049711.57     13838446.91
      3049886.26     13837359.63      3049970.59     13835510.36
#Sta/Elev= 30
  1174.2    79.4  3246.6    67.6  4011.4    71.1  4091.4    57.6    4379    67.5
    4529    67.3    4609    58.8  4674.2   61.92    4752   66.22  4793.7   57.75
  4835.4   56.08  4925.2   60.25  4934.6   57.23  4963.7   53.58  4972.5   51.29
  4981.4   42.53  5002.7   40.89  5018.7   43.04  5025.9   51.79    5041   56.97
  5061.9   59.21  5149.4   65.62  5269.3      64  5339.3    57.8  5502.3    70.9
  6495.3    76.8  6695.3    72.3  7046.5    75.8  7686.5    72.7  8897.7    78.4
#Mann= 6 ,-1 , 0
  1174.2      .2       0  4674.2      .1       0  4934.6      .1       0
  4963.7     .06       0    5041     .15       0  5502.3     .15       0
Bank Sta=4925.2,5061.9
XS Rating Curve= 0
Exp/Cntr=.3,.1

Type RM Length L Ch R = 1 ,227524.1,336.6,379.4,339.9
BEGIN DESCRIPTION:
Cross Section 227524.1 - Interpolated
END DESCRIPTION:
XS GIS Cut Line= 6
      3048414.61     13842874.95      3049643.26     13841156.08
      3050046.61     13840070.15      3050108.66     13839573.72
      3050499.59     13838444.36      3050629.91     13836464.86
#Sta/Elev= 30
  1124.4    78.6  1906.1    71.9  3046.1    69.6  3156.1    65.7  3377.2    69.9
  4601.8   70.17  4720.7    69.4  4790.7    56.4  4840.7    66.2  4876.8   68.73
  4885.7    68.2    4896    65.3  4907.5      48  4929.7   50.82  5001.9   40.54
  5039.3   50.85  5069.3   60.89  5102.6   65.81  5351.8    73.1    5441    70.3
    5536    75.7  5771.7    75.9  5866.7    71.7  6011.7    75.2  6226.1    72.3
  6841.1    75.1  6946.1    72.2  7671.1    75.8  7841.1    72.8  8074.9    76.3
#Mann= 7 ,-1 , 0
  1124.4      .2       0  4601.8     .15       0  4876.8      .1       0
  4929.7     .05       0  5039.3      .1       0  5102.6      .2       0
  5351.8     .15       0
#XS Ineff= 2 , 0
            4873    69.2    5635            75.8
Permanent Ineff=
       F       F
Bank Sta=4885.7,5069.3
XS Rating Curve= 0
Exp/Cntr=.5,.3

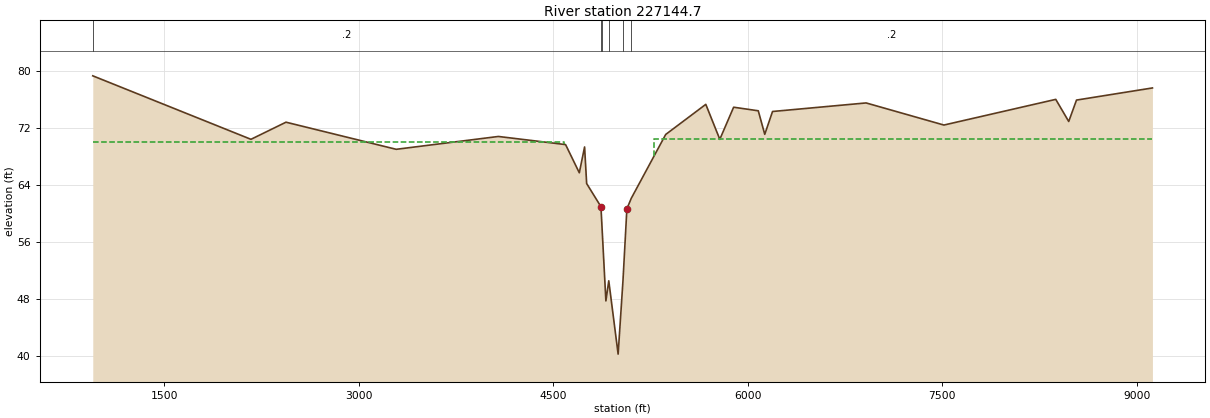
Type RM Length L Ch R = 1 ,227144.7,113,113,113
BEGIN DESCRIPTION:
Upstream Section of Bridge/Culvert/Weir
END DESCRIPTION:
XS GIS Cut Line= 6
      3048394.45     13842953.46      3050133.65     13840844.63
      3051007.13     13837958.66      3051564.76     13837218.92
      3051791.11     13836567.76      3051772.55     13835764.91
#Sta/Elev= 30
   950.5   79.31  2170.5   70.41  2440.5   72.81  3290.5   69.01  4078.2   70.81
  4596.7   69.67  4702.5   65.72  4743.2   69.34  4759.1   64.21  4869.3   60.97
  4876.8   58.38  4907.5   47.76  4929.7   50.58  5001.9    40.3  5039.3   50.61
  5069.3   60.65  5102.6   62.12  5368.7   71.09  5677.9   75.31    5786   70.41
  5892.6   74.91  6082.6   74.41  6132.6   71.11  6192.6   74.31  6914.1   75.51
  7514.1   72.41  8376.7   76.01  8476.7   72.91  8536.7   75.91  9122.2   77.61
#Mann= 6 ,-1 , 0
   950.5      .2       0  4869.3      .1       0  4876.8      .1       0
  4929.7     .05       0  5039.3      .1       0  5102.6      .2       0
#XS Ineff= 2 , 0
            4585      70    5280            70.5
Permanent Ineff=
       F       F
Bank Sta=4869.3,5069.3
XS Rating Curve= 0
Exp/Cntr=.5,.3