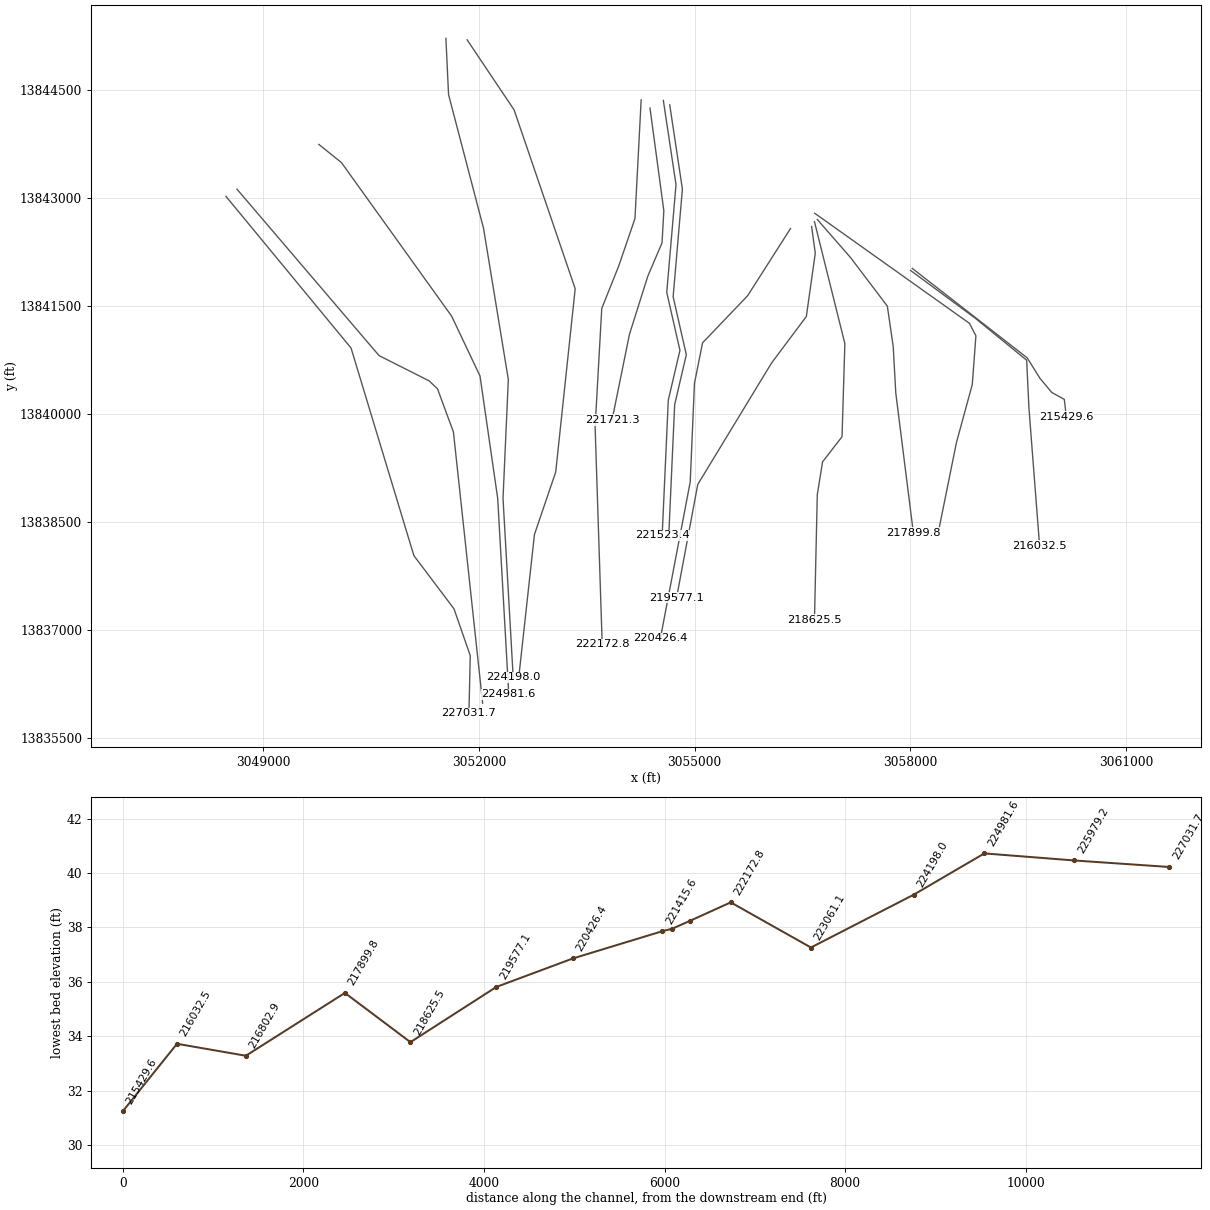
HEC-RAS study W100-00-00.prj: W100-00-00

--- W100-00-00.g01 (geometry) --- (continued)

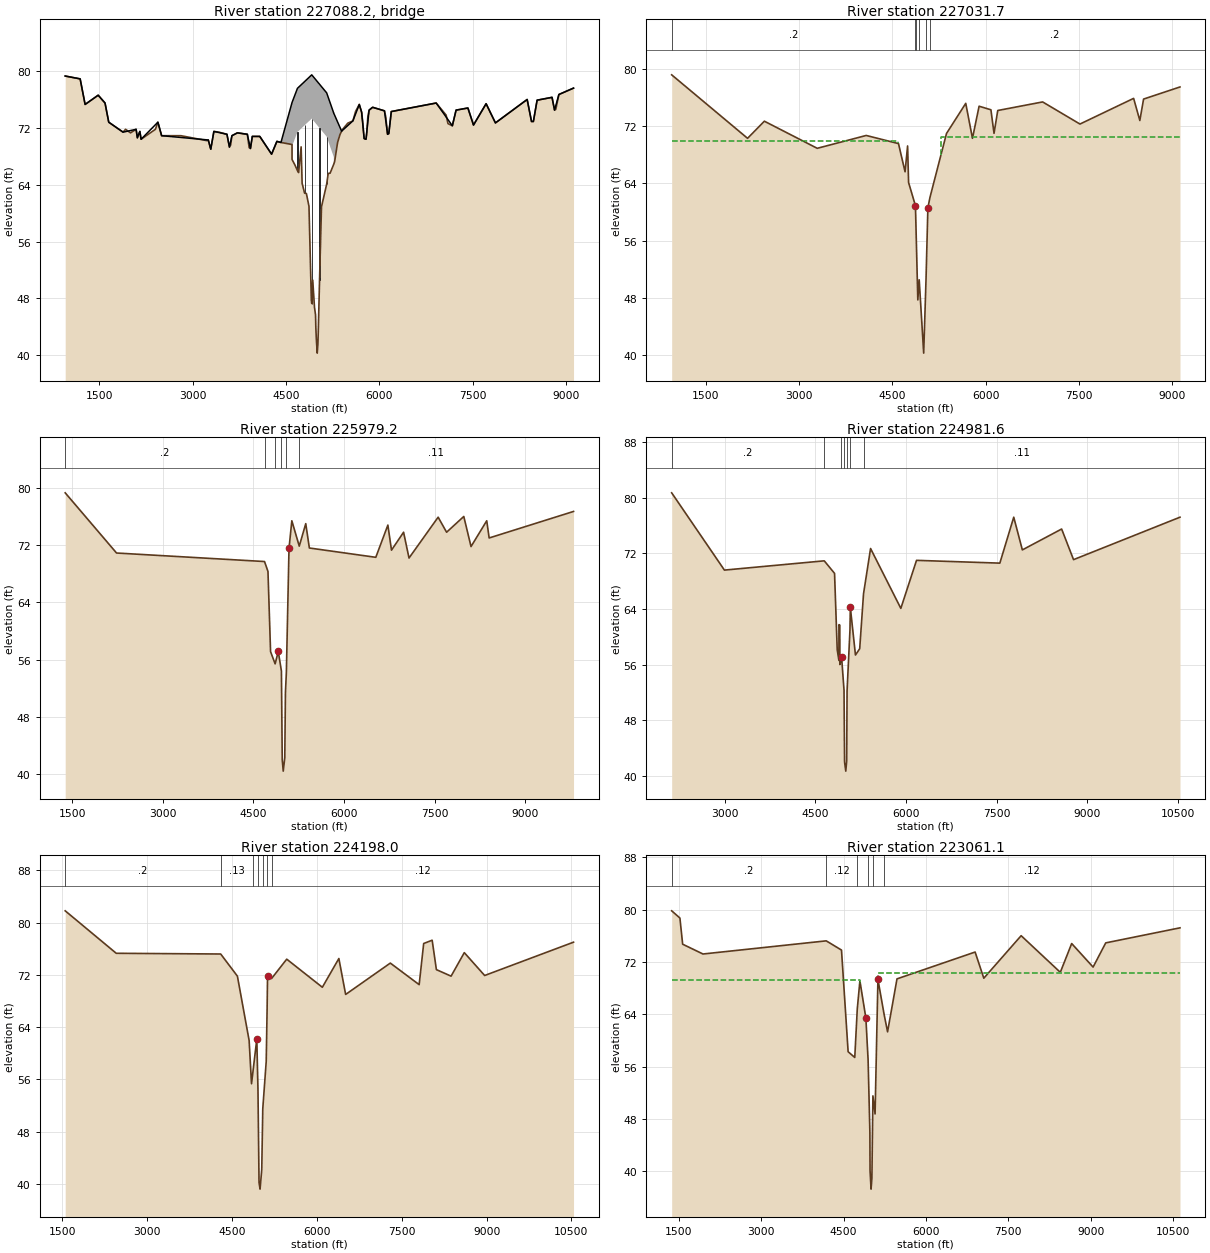
Type RM Length L Ch R = 3 ,227088.2,,,
BEGIN DESCRIPTION:
NORTH KIRKWOOD
Structure ID: WOO-77
END DESCRIPTION:
Bridge Culvert--1,0,-1,-1, 0
Deck Dist Width WeirC Skew NumUp NumDn MinLoCord MaxHiCord MaxSubmerge Is_Ogee
10,93,2.6,0, 60, 60, , , .95, 0, 1,1,,
   950.5  1190.5  1270.5  1480.5  1590.5  1650.5  1880.5  2090.5  2110.5  2150.5
  2170.5  2440.5  2500.5  3250.5  3290.5  3340.5  3550.5  3590.5  3630.5  3718.2
  3878.2  3928.2  3958.2  4078.2  4268.2  4353.5  4418.8  4597.3  4683.8  4913.6
  5153.8 5268.49  5268.6 5394.01  5575.5  5677.9    5716    5756    5786    5836
  5892.6  6082.6  6132.6  6152.6  6192.6  6914.1  7174.1  7234.1  7424.1  7514.1
  7716.7  7866.7  8376.7  8446.7  8476.7  8536.7  8776.7  8816.7  8886.7  9122.2
    79.3    78.9    75.3    76.6    75.5    72.8    71.4    71.8    70.6    71.5
    70.4    72.8    70.9    70.3      69    71.5    71.1    69.3    70.9    71.3
    71.1    69.1    70.8    70.8    68.3    70.1   69.95   75.58   77.57   79.47
   76.93   74.05   74.05   71.54   72.99    75.3    74.2    70.5    70.4    74.5
    74.9    74.4    71.1    71.2    74.3    75.5    72.3    74.5    74.8    72.4
    75.4    72.7      76    72.9    72.9    75.9    76.3    74.5    76.7    77.6
    79.3    78.9    75.3    76.6    75.5    72.8    71.4    71.8    70.6    71.5
    70.4    72.8    70.9    70.3      69    71.5    71.1    69.3    70.9    71.3
    71.1    69.1    70.8    70.8    68.3    70.1   69.95   69.42   71.41   73.31
   70.77   67.89   66.91   71.53   72.98    75.3    74.2    70.5    70.4    74.5
    74.9    74.4    71.1    71.2    74.3    75.5    72.3    74.5    74.8    72.4
    75.4    72.7      76    72.9    72.9    75.9    76.3    74.5    76.7    77.6
   950.5  1190.5  1270.5  1480.5  1590.5  1650.5  1880.5  2090.5  2110.5  2150.5
  2170.5  2440.5  2500.5  3250.5  3290.5  3340.5  3550.5  3590.5  3630.5  3718.2
  3878.2  3928.2  3958.2  4078.2  4268.2  4353.5  4418.8  4597.3  4683.8  4913.6
  5153.8 5268.49  5268.6 5394.01  5575.5  5677.9    5716    5756    5786    5836
  5892.6  6082.6  6132.6  6152.6  6192.6  6914.1  7174.1  7234.1  7424.1  7514.1
  7716.7  7866.7  8376.7  8446.7  8476.7  8536.7  8776.7  8816.7  8886.7  9122.2
    79.3    78.9    75.3    76.6    75.5    72.8    71.4    71.8    70.6    71.5
    70.4    72.8    70.9    70.3      69    71.5    71.1    69.3    70.9    71.3
    71.1    69.1    70.8    70.8    68.3    70.1   69.95   75.58   77.57   79.47
   76.93   74.05   74.05   71.54   72.99    75.3    74.2    70.5    70.4    74.5
    74.9    74.4    71.1    71.2    74.3    75.5    72.3    74.5    74.8    72.4
    75.4    72.7      76    72.9    72.9    75.9    76.3    74.5    76.7    77.6
   79.23   78.83   75.23   76.53   75.43   72.73   71.33   71.73   70.53   71.43
   70.33   72.73   70.83   70.23   68.93   71.43   71.03   69.23   70.83   71.23
   71.03   69.03   70.73   70.73   68.23   70.03   69.88   69.35   71.34   73.24
    70.7   67.82   66.84   71.46   72.91   75.23   74.13   70.43   70.33   74.43
   74.83   74.33   71.03   71.13   74.23   75.43   72.23   74.43   74.73   72.33
   75.33   72.63   75.93   72.83   72.83   75.83   76.23   74.43   76.63   77.53
Pier Skew, UpSta & Num, DnSta & Num=  ,4683.8, 2 ,4683.8, 2 , 0 , 0 , 0 ,,
     3.3     3.3
   64.97   72.43
     3.3     3.3
    64.9   72.36
Pier Skew, UpSta & Num, DnSta & Num=  ,4799, 2 ,4799, 2 , 0 , 0 , 0 ,,
     3.3     3.3
   61.81   73.82
     3.3     3.3
   61.74   73.75
Pier Skew, UpSta & Num, DnSta & Num=  ,4914.3, 2 ,4914.3, 2 , 0 , 0 , 0 ,,
     3.3     3.3
   46.39   74.31
     3.3     3.3
   46.32   74.24
Pier Skew, UpSta & Num, DnSta & Num=  ,5039.3, 2 ,5039.3, 2 , 0 , 0 , 0 ,,
     3.3     3.3
   49.01    73.8
     3.3     3.3
   48.94   73.73
Pier Skew, UpSta & Num, DnSta & Num=  ,5153.8, 2 ,5153.8, 2 , 0 , 0 , 0 ,,
     3.3     3.3
   63.01    71.8
     3.3     3.3
   62.94   71.73
Abutment Skew #Up #Dn= , 2 , 2
  4569.2  4641.6
    69.7   66.81
  4569.2  4641.6
   69.63   66.74
Abutment Skew #Up #Dn= , 2 , 2
  5267.6 5268.69
   66.88   67.89
  5267.6 5268.69
   66.81   67.82
BR Coef= 1 , 1 , 0 ,1.25, 0 ,,,.8,0,2,1,
WSPro=,,,, 1 ,,,, 0 ,,,, 0 ,,,,-1 ,-1 ,-1 , 0 , 0 , 0 , 0 , 0
BR U #Sta/Elev= 130
   950.5    79.3  1190.5    78.9  1270.5    75.3  1480.5    76.6  1590.5    75.5
  1650.5    72.8  1880.5    71.4  1920.5    71.8  2000.5    71.3  2090.5    71.8
  2110.5    70.6  2150.5    71.5  2170.5    70.4  2400.5    71.8  2440.5    72.8
  2500.5    70.9  2810.5    70.9  3230.5    70.2  3250.5    70.3  3290.5      69
  3340.5    71.5  3420.5    71.4  3550.5    71.1  3590.5    69.3  3610.5    69.6
  3630.5    70.9  3718.2    71.3  3878.2    71.1  3908.2    69.2  3928.2    69.1
  3958.2    70.8  4078.2    70.8  4268.2    68.3  4353.5    70.1  4418.7   69.96
  4418.8   69.95 4418.89   69.95    4419   69.95 4419.11   69.95  4422.4   69.94
  4569.1    69.7  4569.2    69.7 4569.31    69.7  4569.4    69.7  4596.7   69.66
  4597.3   67.55  4641.5   66.81  4641.6   66.81  4683.8   65.99  4683.9   65.99
  4702.5   65.71  4743.2   69.33  4759.1    64.2    4799   62.81  4817.9   62.78
  4827.7   62.76  4869.3   60.96  4876.8   58.37  4907.5   47.75  4913.6   47.32
  4914.3   47.27  4929.7   50.57  4957.8   46.74  4974.6   45.69  4979.8   43.88
  4987.4   42.27  5001.9   40.29  5013.1   41.61  5020.1   43.76  5038.9   50.46
  5039.3    50.6  5069.3   60.64  5070.3   60.88  5102.6   62.11  5153.8   64.07
  5154.1   64.09  5178.3   65.59  5208.8   65.62  5267.5   66.88  5267.6   66.88
  5268.4    66.9 5268.49    66.9  5268.6   66.91  5268.7   66.91    5282   67.26
  5329.2   69.94  5351.8   70.59  5368.7   71.08 5393.79   71.53  5393.9   71.53
 5394.01   71.53  5399.4   71.63  5405.5   71.74    5494   72.67  5575.5   72.98
  5576.9   73.02  5617.9    74.3  5677.9    75.3    5716    74.2    5736    72.6
    5756    70.5    5786    70.4    5796    71.1    5816    73.6    5836    74.5
  5892.6    74.9  6082.6    74.4  6102.6    73.6  6132.6    71.1  6152.6    71.2
  6192.6    74.3  6914.1    75.5  7074.1    73.8  7104.1    72.6  7174.1    72.3
  7234.1    74.5  7424.1    74.8  7514.1    72.4  7716.7    75.4  7826.7    73.4
  7866.7    72.7  8376.7      76  8446.7    72.9  8476.7    72.9  8536.7    75.9
  8776.7    76.3  8816.7    74.5  8836.7    74.6  8886.7    76.7  9122.2    77.6
BR U #Mann= 6
   950.5      .2  4869.3      .1  4876.8      .1  4929.7     .05  5039.3      .1
  5102.6      .2
BR U Banks=4869.3,5069.3
BR D #Sta/Elev= 130
   950.5   79.23  1190.5   78.83  1270.5   75.23  1480.5   76.53  1590.5   75.43
  1650.5   72.73  1880.5   71.33  1920.5   71.73  2000.5   71.23  2090.5   71.73
  2110.5   70.53  2150.5   71.43  2170.5   70.33  2400.5   71.73  2440.5   72.73
  2500.5   70.83  2810.5   70.83  3230.5   70.13  3250.5   70.23  3290.5   68.93
  3340.5   71.43  3420.5   71.33  3550.5   71.03  3590.5   69.23  3610.5   69.53
  3630.5   70.83  3718.2   71.23  3878.2   71.03  3908.2   69.13  3928.2   69.03
  3958.2   70.73  4078.2   70.73  4268.2   68.23  4353.5   70.03  4418.7   69.89
  4418.8   69.88 4418.89   69.88    4419   69.88 4419.11   69.88  4422.4   69.87
  4569.1   69.63  4569.2   69.63 4569.31   69.63  4569.4   69.63  4596.7   69.59
  4597.3   67.48  4641.5   66.74  4641.6   66.74  4683.8   65.92  4683.9   65.92
  4702.5   65.64  4743.2   69.26  4759.1   64.13    4799   62.74  4817.9   62.71
  4827.7   62.69  4869.3   60.89  4876.8    58.3  4907.5   47.68  4913.6   47.25
  4914.3    47.2  4929.7    50.5  4957.8   46.67  4974.6   45.62  4979.8   43.81
  4987.4    42.2  5001.9   40.22  5013.1   41.54  5020.1   43.69  5038.9   50.39
  5039.3   50.53  5069.3   60.57  5070.3   60.81  5102.6   62.04  5153.8      64
  5154.1   64.02  5178.3   65.52  5208.8   65.55  5267.5   66.81  5267.6   66.81
  5268.4   66.83 5268.49   66.83  5268.6   66.84  5268.7   66.84    5282   67.19
  5329.2   69.87  5351.8   70.52  5368.7   71.01 5393.79   71.46  5393.9   71.46
 5394.01   71.46  5399.4   71.56  5405.5   71.67    5494    72.6  5575.5   72.91
  5576.9   72.95  5617.9   74.23  5677.9   75.23    5716   74.13    5736   72.53
    5756   70.43    5786   70.33    5796   71.03    5816   73.53    5836   74.43
  5892.6   74.83  6082.6   74.33  6102.6   73.53  6132.6   71.03  6152.6   71.13
  6192.6   74.23  6914.1   75.43  7074.1   73.73  7104.1   72.53  7174.1   72.23
  7234.1   74.43  7424.1   74.73  7514.1   72.33  7716.7   75.33  7826.7   73.33
  7866.7   72.63  8376.7   75.93  8446.7   72.83  8476.7   72.83  8536.7   75.83
  8776.7   76.23  8816.7   74.43  8836.7   74.53  8886.7   76.63  9122.2   77.53
BR D #Mann= 6
   950.5      .2  4869.3      .1  4876.8      .1  4929.7     .05  5039.3      .1
  5102.6      .2
BR D Banks=4869.3,5069.3
BC Design=,, 0 ,, 0 ,,,,,,
BC HTab HWMax=79.31

Type RM Length L Ch R = 1 ,227031.7,1052.5,1052.5,1052.5
BEGIN DESCRIPTION:
Downstream Section of Bridge/Culvert/Weir
END DESCRIPTION:
XS GIS Cut Line= 6
      3048482.19     13843024.67      3050221.39     13840915.85
      3051094.87     13838029.88       3051652.5     13837290.14
      3051878.85     13836638.98      3051860.28     13835836.13
#Sta/Elev= 30
   950.5   79.23  2170.5   70.33  2440.5   72.73  3290.5   68.93  4078.2   70.73
  4596.7   69.59  4702.5   65.64  4743.2   69.26  4759.1   64.13  4869.3   60.89
  4876.8    58.3  4907.5   47.68  4929.7    50.5  5001.9   40.22  5039.3   50.53
  5069.3   60.57  5102.6   62.04  5368.7   71.01  5677.9   75.23    5786   70.33
  5892.6   74.83  6082.6   74.33  6132.6   71.03  6192.6   74.23  6914.1   75.43
  7514.1   72.33  8376.7   75.93  8476.7   72.83  8536.7   75.83  9122.2   77.53
#Mann= 6 ,-1 , 0
   950.5      .2       0  4869.3      .1       0  4876.8      .1       0
  4929.7     .05       0  5039.3      .1       0  5102.6      .2       0
#XS Ineff= 2 , 0
            4585      70    5280            70.5
Permanent Ineff=
       F       F
Bank Sta=4869.3,5069.3
XS Rating Curve= 0
Exp/Cntr=.5,.3

Type RM Length L Ch R = 1 ,225979.2,1030,997.6,958.5
BEGIN DESCRIPTION:
Cross Section 225979.2
END DESCRIPTION:
XS GIS Cut Line= 6
      3048635.37      13843124.5      3050610.55     13840810.79
      3051306.23     13840459.87      3051423.21     13840349.05
      3051644.84     13839748.79      3052051.17     13835977.94
#Sta/Elev= 30
  1385.7    79.3  2235.7    70.9  4685.7   69.71  4742.8   68.33  4785.8   57.13
  4861.4   55.43  4913.1   57.16  4965.4   54.44    4979   42.06  4995.5   40.46
    5021   42.32    5032   51.42  5047.3   54.22  5091.1   71.55  5137.9    75.4
    5261   71.86  5368.2      75  5428.2    71.6    6528    70.3    6728    74.8
    6788    71.3    6988    73.8    7078    70.2  7560.3    75.9  7700.3    73.8
  7984.8      76  8104.8    71.8  8364.8    75.4  8404.8      73  9801.8    76.7
#Mann= 6 ,-1 , 0
  1385.7      .2       0  4685.7      .1       0  4861.4      .1       0
  4965.4     .06       0  5047.3     .11       0    5261     .11       0
Bank Sta=4913.1,5091.1
XS Rating Curve= 0
Exp/Cntr=.3,.1

Type RM Length L Ch R = 1 ,224981.6,894.3,783.6,702
BEGIN DESCRIPTION:
Cross Section 224981.6
END DESCRIPTION:
XS GIS Cut Line= 6
      3049773.26     13843747.44      3050087.24     13843495.03
      3051620.21     13841358.72      3052014.23     13840527.59
      3052260.49     13838825.32       3052414.4     13836101.07
#Sta/Elev= 30
  2121.2    80.7  2994.1    69.6  4646.2   70.93  4816.6   69.13  4860.9   58.14
  4888.9   56.61  4889.5   61.76  4903.5   61.69  4904.2   56.03  4928.7   56.89
  4933.5   57.06  4973.4   52.35  4982.5   42.02  5002.5   40.72  5017.5   42.17
  5023.7   52.24  5071.4   60.93  5077.8   64.24  5162.7    57.4  5232.7    58.3
  5296.2    66.2  5412.7    72.7  5913.5    64.1  6173.2      71  7552.1    70.6
  7782.1    77.2  7924.5    72.5  8574.5    75.5  8771.6    71.1 10533.3    77.2
#Mann= 7 ,-1 , 0
  2121.2      .2       0  4646.2     .12       0  4928.7     .12       0
  4973.4     .06       0  5023.7     .12       0  5071.4      .2       0
  5296.2     .11       0
Bank Sta=4933.5,5077.8
XS Rating Curve= 0
Exp/Cntr=.3,.1

Type RM Length L Ch R = 1 ,224198.0,1105.8,1136.9,1152.8
BEGIN DESCRIPTION:
Cross Section 224198.0
END DESCRIPTION:
XS GIS Cut Line= 6
      3051540.18     13845221.92      3051577.12     13844440.05
      3052063.48     13842580.78      3052408.25     13840478.34
      3052334.37     13838825.32      3052475.97     13836335.01
#Sta/Elev= 30
  1548.2    81.8  2450.9    75.3  4298.2   75.19  4593.5    71.8  4800.7   61.96
  4843.1   55.33  4868.2   57.17  4936.5   62.16  4957.3   54.37    4976   40.22
  4994.2    39.2  5024.1   42.22  5042.1    51.5    5103   58.75  5118.5   66.62
  5126.5   71.79  5198.2   71.44  5465.6    74.4  6095.6    70.1  6387.7    74.5
  6507.7      69  7297.7    73.8  7807.7    70.5  7887.7    76.8  8037.7    77.3
  8112.3    72.8  8372.3    71.8  8605.9    75.4  8965.9    71.9 10537.7      77
#Mann= 7 ,-1 , 0
  1548.2      .2       0  4298.2     .13       0  4868.2     .12       0
  4957.3    .055       0  5042.1     .12       0  5118.5      .2       0
  5198.2     .12       0
Bank Sta=4936.5,5126.5
XS Rating Curve= 0
Exp/Cntr=.3,.1

Type RM Length L Ch R = 1 ,223061.1,1003.3,888.3,856.7
BEGIN DESCRIPTION:
Cross Section 223061.1
END DESCRIPTION:
XS GIS Cut Line= 6
      3051835.69     13845200.38      3052488.28     13844227.65
      3053337.88     13841740.42      3053066.99     13839191.63
      3052771.48     13838323.56        3052556.     13836362.72
#Sta/Elev= 30
  1370.4    79.8  1520.4    78.7  1570.4    74.7  1940.4    73.2  4185.4   75.21
  4463.3    73.8  4583.9   58.26  4704.7   57.39  4750.6   64.82  4798.2   69.09
  4906.8   63.44  4947.8   56.99  4980.1   45.94  4983.2   40.14  5001.4   37.26
  5016.7   38.91  5035.2   51.52  5074.6   48.75  5126.5   69.31  5240.6   63.91
  5302.2    61.3  5473.9    69.4  6896.6    73.5  7054.7    69.5  7734.7      76
    8448    70.4    8655    74.8    9045    71.2    9275    74.9 10627.6    77.2
#Mann= 6 ,-1 , 0
  1370.4      .2       0  4185.4     .12       0  4750.6     .12       0
  4947.8     .06       0  5035.2     .12       0  5240.6     .12       0
#XS Ineff= 2 , 0
            4792    69.2    5132            70.3
Permanent Ineff=
       F       F
Bank Sta=4906.8,5126.5
XS Rating Curve= 0
Exp/Cntr=.3,.1

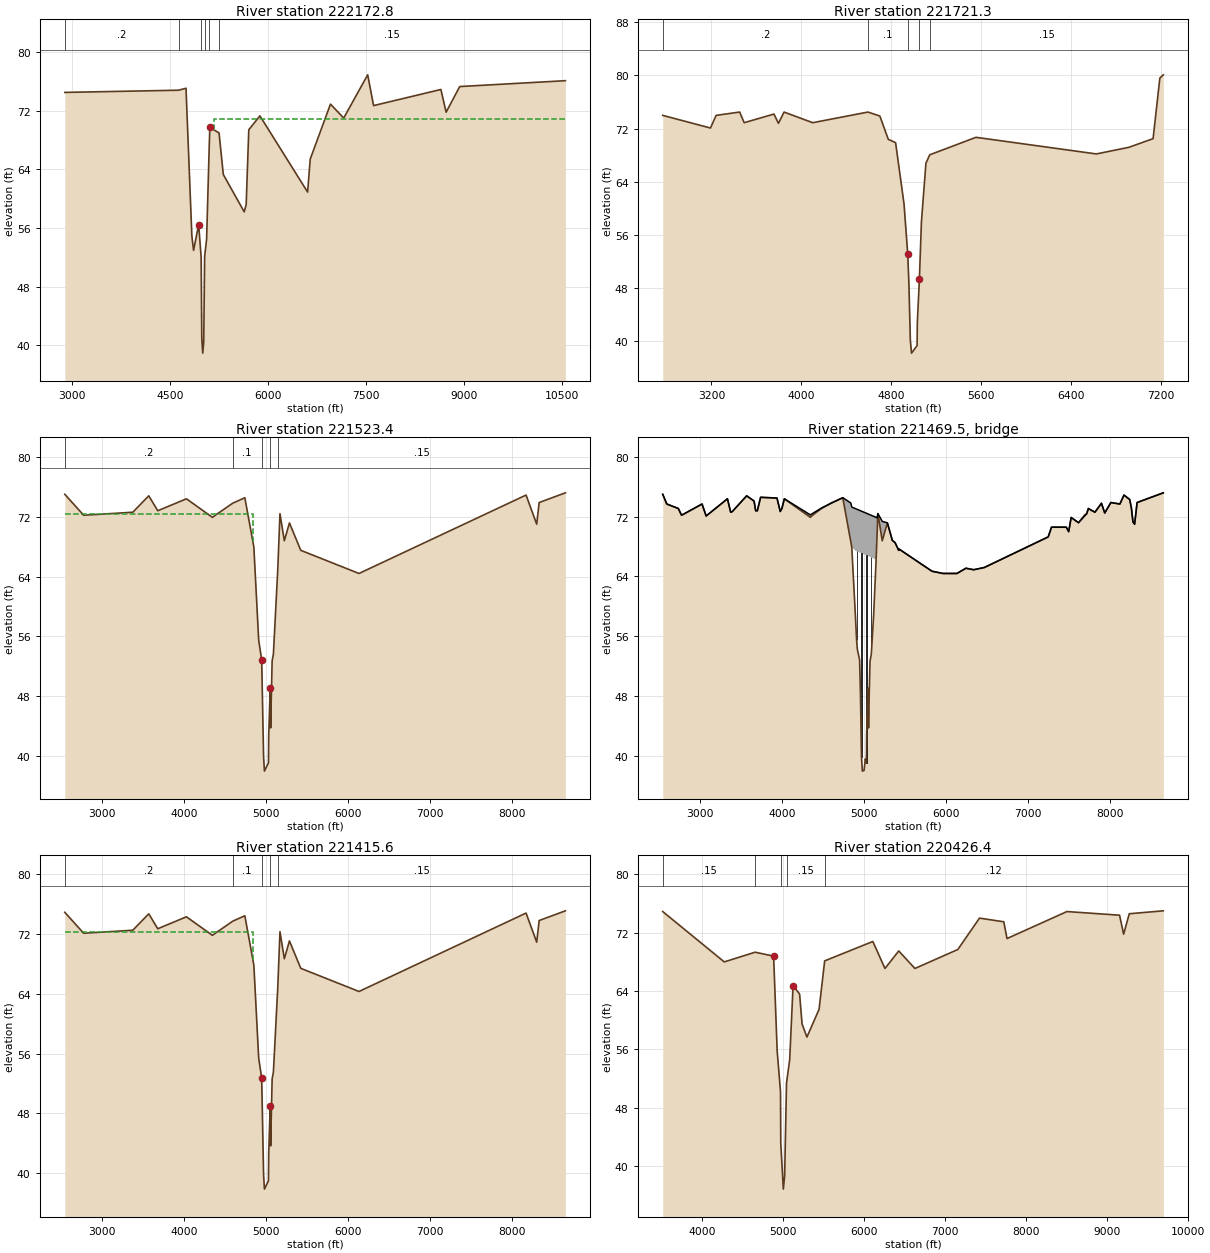
Type RM Length L Ch R = 1 ,222172.8,466.2,451.5,447.1
BEGIN DESCRIPTION:
Cross Section 222172.8
END DESCRIPTION:
XS GIS Cut Line= 6
       3054255.2     13844366.17      3054169.01     13842716.23
      3053941.22     13842051.33      3053707.27     13841466.46
      3053614.92     13839819.59      3053713.42     13836796.75
#Sta/Elev= 30
  2889.4    74.5  4629.5    74.8  4743.8   75.07  4833.4   54.91  4859.6   52.94
  4937.2   56.46  4975.5      52  4985.2   40.91  4999.9   38.92  5014.8   40.43
    5029   52.14  5058.8   54.43  5100.3   67.52  5108.8   69.75  5249.5   68.96
  5314.4    63.3  5634.4    58.2  5664.4    59.2  5704.4    69.4  5874.4    71.3
  6604.4    60.9  6644.4    65.4  6954.4    72.9  7156.5      71  7523.8    76.9
  7613.8    72.7  8643.8    74.9  8723.8    71.8  8931.9    75.3 10548.4    76.1
#Mann= 6 ,-1 , 0
  2889.4      .2       0  4629.5      .1       0  4975.5     .06       0
    5029     .15       0  5100.3      .2       0  5249.5     .15       0
#XS Ineff= 2 , 0
                            5171            70.9
Permanent Ineff=
       F       F
Bank Sta=4937.2,5108.8
XS Rating Curve= 0
Exp/Cntr=.3,.1

Type RM Length L Ch R = 1 ,221721.3,165.9,197.9,515.9
BEGIN DESCRIPTION:
Cross Section 221721.3 - Interpolated
END DESCRIPTION:
XS GIS Cut Line= 6
      3054377.92     13844252.53      3054570.28     13842825.31
      3054545.46     13842378.53      3054346.89     13841913.13
      3054092.47     13841106.44      3053850.46     13839915.02
#Sta/Elev= 30
  2766.3      74  3191.3    72.1  3241.3      74  3451.3    74.5  3491.3    72.9
  3756.3    74.2  3796.3    72.8  3846.3    74.5  4101.3    72.9    4593    74.5
  4698.9    73.9  4773.9    70.4  4838.9    69.9  4913.9    60.7  4947.1   53.12
  4957.3   48.73  4970.3   40.16  4980.7   38.24  5030.1   39.37  5032.7   42.94
  5050.7   49.34  5068.9      58  5108.9    66.8    5143   68.07  5554.5    70.7
  6625.9    68.2  6915.9    69.2  7130.9    70.5  7190.9    79.6  7221.6    80.1
#Mann= 5 ,-1 , 0
  2766.3      .2       0    4593      .1       0  4947.1     .05       0
  5050.7      .1       0    5143     .15       0
Bank Sta=4947.1,5050.7
XS Rating Curve= 0
Exp/Cntr=.5,.3

Type RM Length L Ch R = 1 ,221523.4,107.8,107.8,107.8
BEGIN DESCRIPTION:
Upstream Section of Bridge/Culvert/Weir
END DESCRIPTION:
XS GIS Cut Line= 6
      3054563.57     13844358.33      3054739.72     13843187.57
      3054610.93     13841690.49      3054794.29     13840883.76
      3054632.37     13840190.93      3054547.34      13838310.4
#Sta/Elev= 30
    2543   75.02    2773   72.22    3373   72.62  3568.1   74.82  3678.1   72.82
  4028.1   74.42  4344.9   71.94    4593   73.83  4741.4   74.56  4851.5   67.95
  4910.5   55.49  4947.1   52.83  4970.3   39.87  4980.7   37.95  5030.1   39.08
  5032.7   42.65  5050.7   49.05  5056.2   43.74  5074.6   52.69  5090.1   53.63
    5143   64.84  5170.3   72.43  5223.7    68.8  5286.1   71.19  5424.3   67.52
  6135.4   64.42  8175.5   74.92  8305.5   71.02  8335.5   73.92  8655.5   75.22
#Mann= 5 ,-1 , 0
    2543      .2       0    4593      .1       0  4947.1     .05       0
  5050.7      .1       0    5143     .15       0
#XS Ineff= 2 , 0
            4840    72.4  5154.7              68
Permanent Ineff=
       F       F
Bank Sta=4947.1,5050.7
XS Rating Curve= 0
Exp/Cntr=.5,.3

Type RM Length L Ch R = 3 ,221469.5,,,
BEGIN DESCRIPTION:
WILCREST DRIVE
Structure ID: WOO-74&75
END DESCRIPTION:
Bridge Culvert--1,0,-1,-1, 0
Deck Dist Width WeirC Skew NumUp NumDn MinLoCord MaxHiCord MaxSubmerge Is_Ogee
10,87.8,2.6,0, 60, 60, , , .95, 0, 1,1,,
    2543    2593    2733    2773    3023    3073    3333    3373    3393  3568.1
  3658.1  3678.1  3698.1  3738.1  3938.1  3978.1  3998.1  4028.1    4345  4485.4
  4741.4 4839.31  4851.5  4897.4  5147.1 5149.89 5160.21  5170.3  5223.7  5286.1
  5346.5  5380.3  5424.3  5427.8  5830.9  5965.4  6135.4  6245.4  6340.4  6470.4
  7250.4  7290.4  7470.4  7500.4  7530.4  7620.4  7720.4  7740.4  7820.4  7900.4
  7940.4  8015.5  8125.5  8175.5  8245.5  8265.5  8285.5  8305.5  8335.5  8655.5
      75    73.7    73.1    72.2    73.7    72.1    74.4    72.6    72.7    74.8
    74.1    72.8    72.8    74.6    74.5    72.7    73.1    74.4   72.25   73.19
   74.55   73.84   73.29   73.08   71.92   71.91   71.84   72.42   71.38   71.18
   68.84   68.53   67.51   67.68    64.7    64.4    64.4    65.1    64.9    65.2
    69.3    70.6    70.6      70    71.9    71.2    72.4    73.1    72.6    73.8
    72.5    73.9    73.7    74.9    74.3    73.2    71.3      71    73.9    75.2
      75    73.7    73.1    72.2    73.7    72.1    74.4    72.6    72.7    74.8
    74.1    72.8    72.8    74.6    74.5    72.7    73.1    74.4   71.92   73.12
   74.54   68.66   67.93   67.44   66.28   66.62   69.55   72.41   68.78   71.17
   68.83   68.52    67.5   67.67    64.7    64.4    64.4    65.1    64.9    65.2
    69.3    70.6    70.6      70    71.9    71.2    72.4    73.1    72.6    73.8
    72.5    73.9    73.7    74.9    74.3    73.2    71.3      71    73.9    75.2
    2543    2593    2733    2773    3023    3073    3333    3373    3393  3568.1
  3658.1  3678.1  3698.1  3738.1  3938.1  3978.1  3998.1  4028.1    4345  4485.4
  4741.4 4839.31  4851.5  4897.4  5147.1 5149.89 5160.21  5170.3  5223.7  5286.1
  5346.5  5380.3  5424.3  5427.8  5830.9  5965.4  6135.4  6245.4  6340.4  6470.4
  7250.4  7290.4  7470.4  7500.4  7530.4  7620.4  7720.4  7740.4  7820.4  7900.4
  7940.4  8015.5  8125.5  8175.5  8245.5  8265.5  8285.5  8305.5  8335.5  8655.5
      75    73.7    73.1    72.2    73.7    72.1    74.4    72.6    72.7    74.8
    74.1    72.8    72.8    74.6    74.5    72.7    73.1    74.4   72.25   73.19
   74.55   73.84   73.29   73.08   71.92   71.91   71.84   72.42   71.38   71.18
   68.84   68.53   67.51   67.68    64.7    64.4    64.4    65.1    64.9    65.2
    69.3    70.6    70.6      70    71.9    71.2    72.4    73.1    72.6    73.8
    72.5    73.9    73.7    74.9    74.3    73.2    71.3      71    73.9    75.2
   74.94   73.64   73.04   72.14   73.64   72.04   74.34   72.54   72.64   74.74
   74.04   72.74   72.74   74.54   74.44   72.64   73.04   74.34   71.86   73.06
   74.48    68.6   67.87   67.38   66.22   66.56   69.49   72.35   68.72   71.11
   68.77   68.46   67.44   67.61   64.64   64.34   64.34   65.04   64.84   65.14
   69.24   70.54   70.54   69.94   71.84   71.14   72.34   73.04   72.54   73.74
   72.44   73.84   73.64   74.84   74.24   73.14   71.24   70.94   73.84   75.14
Pier Skew, UpSta & Num, DnSta & Num=  ,4910.5, 2 ,4910.5, 2 , 0 , 0 , 0 ,,
     2.5     2.5
    54.3   68.39
     2.5     2.5
   54.24   68.33
Pier Skew, UpSta & Num, DnSta & Num=  ,4970.3, 2 ,4970.3, 2 , 0 , 0 , 0 ,,
     2.5     2.5
   38.62   68.11
     2.5     2.5
   38.56   68.05
Pier Skew, UpSta & Num, DnSta & Num=  ,5030.1, 2 ,5030.1, 2 , 0 , 0 , 0 ,,
     2.5     2.5
   38.11   67.83
     2.5     2.5
   38.05   67.77
Pier Skew, UpSta & Num, DnSta & Num=  ,5090.1, 2 ,5090.1, 2 , 0 , 0 , 0 ,,
     2.5     2.5
   52.53   67.56
     2.5     2.5
   52.47    67.5
Abutment Skew #Up #Dn= , 2 , 2
  5147.1 5150.09
   65.83   66.62
  5147.1 5150.09
   65.77   66.56
BR Coef= 1 , 1 , 0 ,1.25, 0 ,,,.8,-1,2,0,
WSPro=,,,, 1 ,,,, 0 ,,,, 0 ,,,,-1 ,-1 ,-1 , 0 , 0 , 0 , 0 , 0
BR U #Sta/Elev= 110
    2543      75    2593    73.7    2733    73.1    2773    72.2    3023    73.7
    3073    72.1    3333    74.4    3373    72.6    3393    72.7  3568.1    74.8
  3658.1    74.1  3678.1    72.8  3698.1    72.8  3738.1    74.6  3938.1    74.5
  3978.1    72.7  3998.1    73.1  4028.1    74.4    4300   72.27  4344.9   71.92
    4345   71.92  4348.9   71.96  4394.9   72.39  4485.4   73.12  4525.2   73.37
    4593   73.81  4599.8   73.85  4606.2   73.88  4740.2   74.53  4741.4   74.54
 4839.09   68.68  4839.2   68.67 4839.31   68.66 4851.01   67.96  4851.1   67.95
  4851.3   67.94  4851.4   67.94  4851.5   67.93  4897.4    58.4  4910.5   55.47
  4919.6   54.25  4947.1   52.81  4957.3   48.42  4968.3   41.07  4970.3   39.85
  4980.7   37.93  5001.2   38.02  5017.4   39.56  5030.1   39.06  5031.7   40.74
  5032.7   42.63  5044.9   47.72    5048   48.61  5050.7   49.03  5056.2   43.72
  5060.2   46.51  5064.6   48.27  5074.6   52.67  5090.1   53.61    5119   58.93
    5143   64.82    5147   65.81  5147.1   65.83 5149.89   66.62    5150   66.65
  5150.3   66.74 5159.99   69.49  5160.1   69.52 5160.21   69.55  5170.3   72.41
  5223.7   68.78    5256   70.02  5286.1   71.17  5297.8   70.72  5346.5   68.83
  5370.6   68.61  5380.3   68.52  5424.3    67.5  5424.4    67.5  5425.8   67.57
  5427.8   67.67  5448.4   67.52  5568.9   66.63  5830.9    64.7  5965.4    64.4
  6135.4    64.4  6245.4    65.1  6340.4    64.9  6470.4    65.2  7250.4    69.3
  7290.4    70.6  7470.4    70.6  7500.4      70  7530.4    71.9  7620.4    71.2
  7700.4    72.3  7720.4    72.4  7740.4    73.1  7820.4    72.6  7900.4    73.8
  7940.4    72.5  8015.5    73.9  8125.5    73.7  8175.5    74.9  8245.5    74.3
  8265.5    73.2  8285.5    71.3  8305.5      71  8335.5    73.9  8655.5    75.2
BR U #Mann= 5
    2543      .2    4593      .1  4947.1     .05  5050.7      .1    5143     .15
BR U Banks=4947.1,5050.7
BR D #Sta/Elev= 110
    2543   74.94    2593   73.64    2733   73.04    2773   72.14    3023   73.64
    3073   72.04    3333   74.34    3373   72.54    3393   72.64  3568.1   74.74
  3658.1   74.04  3678.1   72.74  3698.1   72.74  3738.1   74.54  3938.1   74.44
  3978.1   72.64  3998.1   73.04  4028.1   74.34    4300   72.21  4344.9   71.86
    4345   71.86  4348.9    71.9  4394.9   72.33  4485.4   73.06  4525.2   73.31
    4593   73.75  4599.8   73.79  4606.2   73.82  4740.2   74.47  4741.4   74.48
 4839.09   68.62  4839.2   68.61 4839.31    68.6 4851.01    67.9  4851.1   67.89
  4851.3   67.88  4851.4   67.88  4851.5   67.87  4897.4   58.34  4910.5   55.41
  4919.6   54.19  4947.1   52.75  4957.3   48.36  4968.3   41.01  4970.3   39.79
  4980.7   37.87  5001.2   37.96  5017.4    39.5  5030.1      39  5031.7   40.68
  5032.7   42.57  5044.9   47.66    5048   48.55  5050.7   48.97  5056.2   43.66
  5060.2   46.45  5064.6   48.21  5074.6   52.61  5090.1   53.55    5119   58.87
    5143   64.76    5147   65.75  5147.1   65.77 5149.89   66.56    5150   66.59
  5150.3   66.68 5159.99   69.43  5160.1   69.46 5160.21   69.49  5170.3   72.35
  5223.7   68.72    5256   69.96  5286.1   71.11  5297.8   70.66  5346.5   68.77
  5370.6   68.55  5380.3   68.46  5424.3   67.44  5424.4   67.44  5425.8   67.51
  5427.8   67.61  5448.4   67.46  5568.9   66.57  5830.9   64.64  5965.4   64.34
  6135.4   64.34  6245.4   65.04  6340.4   64.84  6470.4   65.14  7250.4   69.24
  7290.4   70.54  7470.4   70.54  7500.4   69.94  7530.4   71.84  7620.4   71.14
  7700.4   72.24  7720.4   72.34  7740.4   73.04  7820.4   72.54  7900.4   73.74
  7940.4   72.44  8015.5   73.84  8125.5   73.64  8175.5   74.84  8245.5   74.24
  8265.5   73.14  8285.5   71.24  8305.5   70.94  8335.5   73.84  8655.5   75.14
BR D #Mann= 5
    2543      .2    4593      .1  4947.1     .05  5050.7      .1    5143     .15
BR D Banks=4947.1,5050.7
BC Design=,, 0 ,, 0 ,,,,,,
BC HTab HWMax=75.22

Type RM Length L Ch R = 1 ,221415.6,989.2,989.2,989.2
BEGIN DESCRIPTION:
Downstream Section of Bridge/Culvert/Weir
END DESCRIPTION:
XS GIS Cut Line= 6
      3054652.33     13844297.15      3054828.48     13843126.39
      3054699.69     13841629.31      3054883.05     13840822.58
      3054721.13     13840129.75       3054636.1     13838249.22
#Sta/Elev= 30
    2543   74.93    2773   72.13    3373   72.53  3568.1   74.73  3678.1   72.73
  4028.1   74.33  4344.9   71.85    4593   73.74  4741.4   74.47  4851.5   67.86
  4910.5    55.4  4947.1   52.74  4970.3   39.78  4980.7   37.86  5030.1   38.99
  5032.7   42.56  5050.7   48.96  5056.2   43.65  5074.6    52.6  5090.1   53.54
    5143   64.75  5170.3   72.34  5223.7   68.71  5286.1    71.1  5424.3   67.43
  6135.4   64.33  8175.5   74.83  8305.5   70.93  8335.5   73.83  8655.5   75.13
#Mann= 5 ,-1 , 0
    2543      .2       0    4593      .1       0  4947.1     .05       0
  5050.7      .1       0    5143     .15       0
#XS Ineff= 2 , 0
            4840    72.3  5154.7              68
Permanent Ineff=
       F       F
Bank Sta=4947.1,5050.7
XS Rating Curve= 0
Exp/Cntr=.5,.3

Type RM Length L Ch R = 1 ,220426.4,844.3,849.3,877.7
BEGIN DESCRIPTION:
Cross Section 220426.4
END DESCRIPTION:
XS GIS Cut Line= 6
       3056332.1     13842577.78      3055734.55     13841641.99
      3055108.81     13840988.07      3054996.07     13840424.35
      3054937.37     13839054.49      3054522.27     13836877.55
#Sta/Elev= 30
    3510    74.9    4270      68  4650.8   69.33  4879.5   68.79  4923.3   55.81
  4964.7   50.18  4967.8   43.15  4999.6   36.86  5015.8    38.7  5038.8   51.41
  5078.1   54.62  5119.8   64.75  5200.3    63.6  5230.8    59.5  5290.8    57.7
  5440.8    61.5  5510.1   68.14  6104.7    70.8  6254.7    67.1  6424.7    69.5
  6624.7    67.1  7154.7    69.7    7422      74    7722    73.5    7762    71.2
    8502    74.9    9152    74.4    9202    71.8    9272    74.6    9692      75
#Mann= 5 ,-1 , 0
    3510     .15       0  4650.8      .1       0  4964.7    .055       0
  5038.8     .15       0  5510.1     .12       0
Bank Sta=4879.5,5119.8
XS Rating Curve= 0
Exp/Cntr=.3,.1

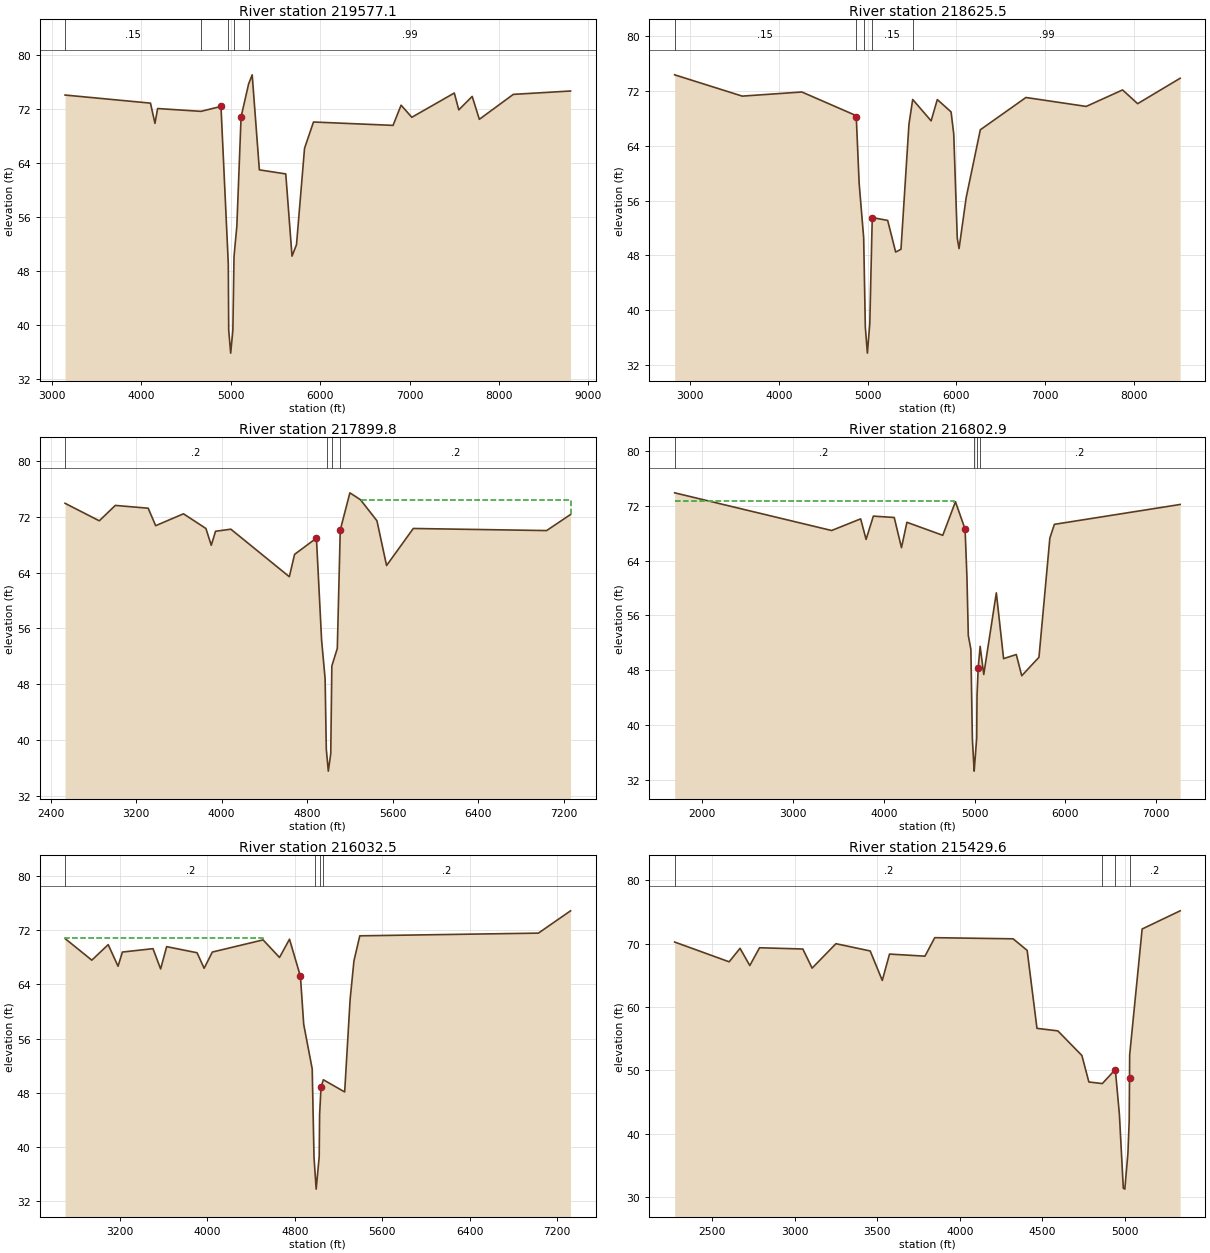
Type RM Length L Ch R = 1 ,219577.1,879.9,951.6,1001.5
BEGIN DESCRIPTION:
Cross Section 219577.1
END DESCRIPTION:
XS GIS Cut Line= 6
      3056625.23     13842605.96      3056675.97     13842233.91
      3056551.95     13841354.49      3056067.15     13840706.21
      3055042.19     13839019.55      3054747.36     13837442.57
#Sta/Elev= 30
  3146.3    74.1  4101.8    72.9  4151.8    69.9  4181.8    72.1  4666.3   71.68
  4890.3   72.41  4972.1   49.06  4976.7   39.23  4998.9   35.81  5023.3   39.21
  5036.2   50.16  5067.8   54.65  5115.2   70.85  5199.3   75.74  5239.5    77.1
  5319.5      63    5615    62.4    5685    50.2    5735    51.9    5825    66.2
    5925    70.1    6815    69.6    6905    72.6    7025    70.8  7500.3    74.4
  7550.3    71.9  7700.3    73.9  7780.3    70.5  8160.3    74.2  8800.3    74.7
#Mann= 5 ,-1 , 0
  3146.3     .15       0  4666.3      .1       0  4972.1     .06       0
  5036.2      .2       0  5199.3     .99       0
Bank Sta=4890.3,5115.2
XS Rating Curve= 0
Exp/Cntr=.3,.1

Type RM Length L Ch R = 1 ,218625.5,709,725.7,737.5
BEGIN DESCRIPTION:
Cross Section 218625.5
END DESCRIPTION:
XS GIS Cut Line= 6
       3056664.7     13842673.61      3057087.49      13840976.8
      3057048.03     13839683.05      3056777.44     13839333.54
      3056704.16     13838876.92       3056664.7     13837137.83
#Sta/Elev= 30
  2823.9    74.3  3586.4    71.2  4258.9    71.8  4869.3   68.37  4872.7   68.13
    4905   58.49  4955.9    50.6  4974.8   37.53  4997.9   33.78  5025.1   38.09
  5048.7   51.29  5053.2   53.52  5226.8    53.1  5316.8    48.5  5376.8    48.9
  5466.8    67.1  5509.1   70.71  5716.8    67.6  5786.8    70.7    5942    68.9
    5972    65.7    6012    50.5    6032      49    6112    56.4    6272    66.3
  6786.5      71  7466.5    69.7  7876.5    72.1  8046.5    70.1    8526    73.8
#Mann= 5 ,-1 , 0
  2823.9     .15       0  4869.3     .15       0  4955.9     .06       0
  5048.7     .15       0  5509.1     .99       0
Bank Sta=4872.7,5053.2
XS Rating Curve= 0
Exp/Cntr=.3,.1

Type RM Length L Ch R = 1 ,217899.8,1112.4,1096.9,1080.2
BEGIN DESCRIPTION:
Cross Section 217899.8
END DESCRIPTION:
XS GIS Cut Line= 6
      3056704.06     13842703.65      3057169.16     13842170.43
      3057678.27     13841498.24      3057759.45     13840939.03
      3057795.53     13840289.62      3058040.19      13838344.2
#Sta/Elev= 30
  2535.4    73.9  2855.4    71.4  3005.4    73.6    3313    73.2    3383    70.7
    3643    72.4    3853    70.3    3903    67.9    3943    69.9  4086.2    70.2
  4633.3    63.4  4682.4    66.6  4886.8   68.92  4935.1   54.34  4967.9   48.82
  4979.1   38.73  4985.8   37.62    4998   35.59  5020.8    38.1  5030.8   50.63
    5082   53.15  5106.1   67.83  5109.4   70.07  5199.7    75.4  5299.7    74.4
  5452.9    71.4  5542.9      65  5792.9    70.3  7039.9      70  7263.7    72.3
#Mann= 4 ,-1 , 0
  2535.4      .2       0  4985.8     .06       0  5030.8     .15       0
  5106.1      .2       0
#XS Ineff= 2 , 0
                            5300           74.35
Permanent Ineff=
       F       F
Bank Sta=4886.8,5109.4
XS Rating Curve= 0
Exp/Cntr=.3,.1

Type RM Length L Ch R = 1 ,216802.9,739.8,762.6,867.1
BEGIN DESCRIPTION:
Cross Section 216802.9
END DESCRIPTION:
XS GIS Cut Line= 6
       3056668.2      13842789.7      3058819.25     13841259.67
      3058909.45      13841086.5      3058858.94     13840408.22
      3058638.86     13839601.87      3058397.14     13838405.87
#Sta/Elev= 30
  1694.8    73.9  3424.8    68.4  3744.8    70.1  3804.8    67.1  3884.8    70.5
  4114.8    70.3  4194.8    65.9  4254.8    69.6  4649.8    67.7  4789.8    72.6
  4895.9    68.6  4916.5   61.53  4931.4   53.07  4959.8   51.06  4976.2      38
    4989   34.95    4996   33.28  5023.8    38.1  5027.4    44.3  5040.6    48.4
    5062   51.49  5101.6   47.39  5240.3    59.3  5320.3    49.7  5460.3    50.3
  5520.3    47.2  5710.3    49.9  5830.3    67.3  5880.3    69.3  7266.3    72.2
#Mann= 4 ,-1 , 0
  1694.8      .2       0    4989     .06       0  5027.4     .12       0
    5062      .2       0
#XS Ineff= 2 , 0
          4775.5   72.75
Permanent Ineff=
       F       F
Bank Sta=4895.9,5040.6
XS Rating Curve= 0
Exp/Cntr=.3,.1

Type RM Length L Ch R = 1 ,216032.5,120,600,580
BEGIN DESCRIPTION:
Cross Section 216040.3 - Interpolated
END DESCRIPTION:
XS GIS Cut Line= 5
 3058001.819872513841993.8001061 3058901.590054613841329.8299773
 3059615.199847913840746.5299629 3059646.229969513840088.7599529
 3059795.160117913838165.1200994
#Sta/Elev= 30
    2697    70.8    2942    67.6    3092    69.9    3182    66.7    3222    68.8
    3502    69.3    3572    66.3    3627    69.6  3905.2    68.7  3970.2    66.4
  4045.2    68.8  4510.2    70.6  4660.2      68  4751.9    70.7  4851.9    65.2
  4881.9    58.1  4959.8    51.5  4976.2   38.44    4989   35.39    4996   33.72
  5023.8   38.54  5027.4   44.74  5040.6   48.84    5062    49.9  5256.9    48.1
  5306.9    61.8  5341.9    67.5  5395.4    71.2  7030.4    71.6  7324.8    74.9
#Mann= 4 ,-1 , 0
    2697      .2       0    4989     .06       0  5027.4     .12       0
    5062      .2       0
#XS Ineff= 2 , 0
            4510   70.83
Permanent Ineff=
       F       F
Bank Sta=4851.9,5040.6
XS Rating Curve= 0
Exp/Cntr=.3,.1

Type RM Length L Ch R = 1 ,215429.6,450,400,300
XS GIS Cut Line= 6
 3058024.727963213842023.2101523 3059622.626014113840779.0200554
 3059802.020012313840492.1000255 3059965.060368613840297.6240365
 3060138.518683113840201.9030994 3060166.663311913839961.6204434
#Sta/Elev= 30
  2272.5   70.26 2602.61   67.14 2668.59   69.27  2727.7   66.55 2786.82   69.36
 3049.09   69.16 3105.33   66.14 3249.67      70 3457.32   68.85 3530.47    64.2
 3574.28   68.36 3789.11   68.03 3848.47   70.95 4323.52   70.77 4408.39   68.94
 4467.79   56.63 4594.41   56.23 4740.03   52.34 4782.25   48.16 4863.77   47.91
 4942.53   50.13  4967.4      43  4990.9   31.38 5000.05   31.24 5018.86    36.9
 5026.67   42.07  5028.5  48.751 5029.46   52.44 5105.03   72.32 5335.29   75.19
#Mann= 4 ,-1 , 0
  2272.5      .2       0 4863.77     .12       0 4942.53     .04       0
 5029.46      .2       0
Bank Sta=4942.53,5028.5
XS Rating Curve= 0
Exp/Cntr=.3,.1