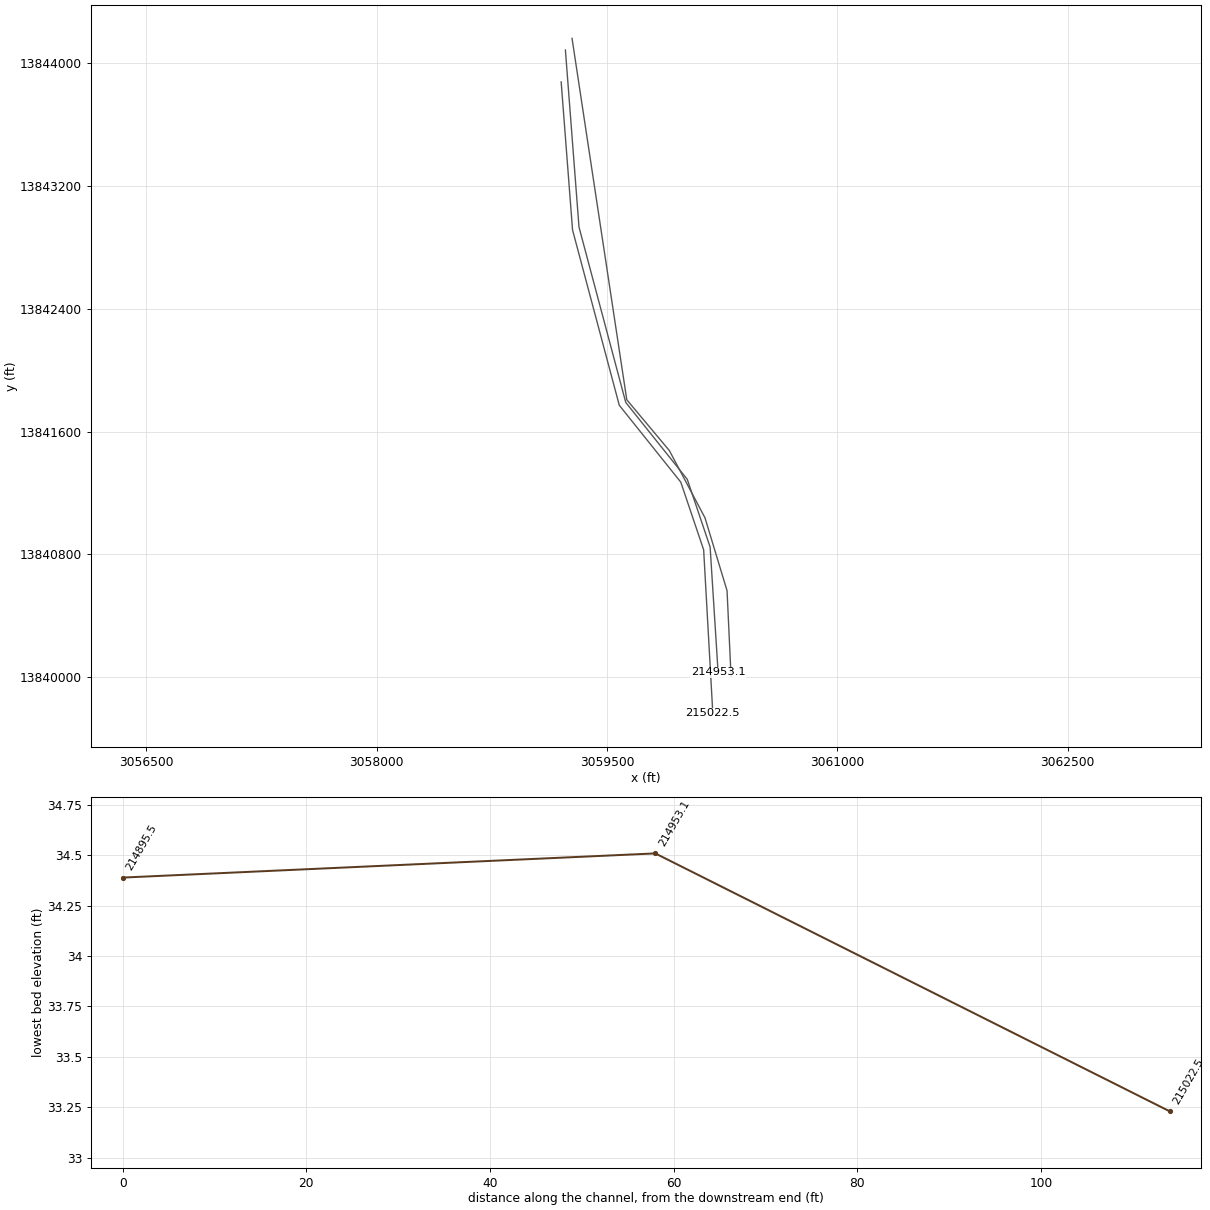
HEC-RAS study W100-00-00.prj: W100-00-00

--- W100-00-00.g01 (geometry) --- (continued)

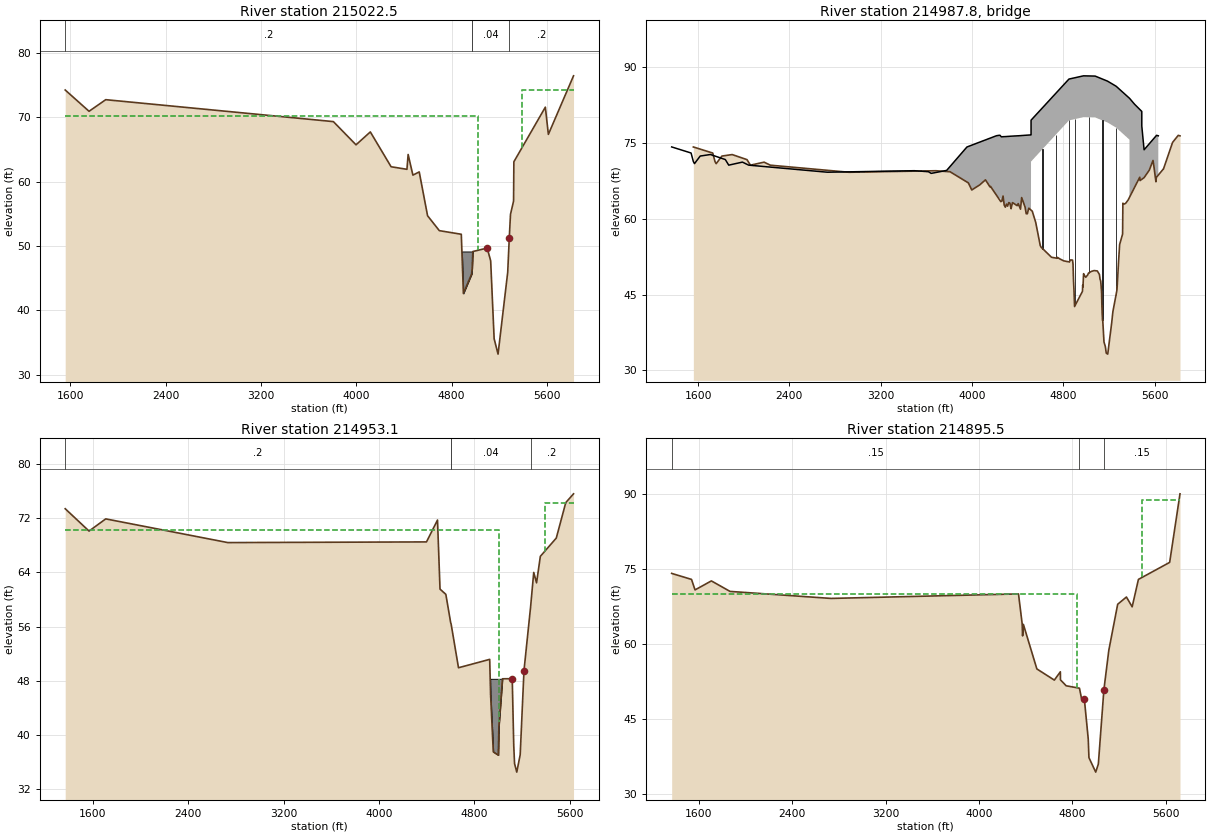
Type RM Length L Ch R = 1 ,215022.5,56,56,56
BEGIN DESCRIPTION:
Upstream Section of Bridge/Culvert/Weir
END DESCRIPTION:
XS GIS Cut Line= 6
 3059201.755691113843877.3582616 3059275.830119813842913.2798944
 3059580.250114613841771.2998949 3059980.9799562 13841270.379965
 3060129.830052213840829.5701511  3060189.47891813839764.4612527
#Sta/Elev= 30
  1558.6   74.19  1758.6   70.89  1898.6   72.69  3808.4   69.29  3998.4   65.69
  4118.4   67.69  4292.7   62.29  4425.6   61.89  4435.6   64.19  4475.6   60.99
  4528.7   61.49  4598.7   54.69 4697.25   52.38 4881.57   51.82 4899.24   42.64
  4968.5   45.65 4972.75    46.5 4978.34   49.14 5098.72   49.68 5128.07    47.7
 5157.12   35.62    5190   33.23    5271   45.93 5284.09   51.23 5294.36   54.91
 5320.21   56.97 5322.67   63.06  5586.7   71.53 5612.13   67.31  5823.2   76.39
#Mann= 4 ,-1 , 0
  1558.6      .2       0  4968.5    .055       0 4972.75     .04       0
 5284.09      .2       0
#XS Ineff= 2 , 0
            5020    70.2    5390            74.2
Permanent Ineff=
       F       F
#Block Obstruct= 1 ,-1
 4884.71 4978.54   49.15
Bank Sta=5098.72,5284.09
XS Rating Curve= 0
Exp/Cntr=.5,.3

Type RM Length L Ch R = 3 ,214987.8,,,
BEGIN DESCRIPTION:
SAM HOUSTON HWY 8 RAMP
Structure ID: WOO-72
END DESCRIPTION:
Bridge Culvert--1,0,-1,-1, 0
Deck Dist Width WeirC Skew NumUp NumDn MinLoCord MaxHiCord MaxSubmerge Is_Ogee
18.5,27,2.6,0, 60, 60, , , .95, 0, 1,1,,
  1368.6  1538.6  1558.6  1568.6  1618.6  1708.6  1838.6  1868.6  1988.6  2043.1
  2733.1  3494.6  3618.4  3642.9  3778.4  3808.4  3928.4  3956.2  4062.7  4072.7
  4082.7  4092.7  4102.7  4112.7  4122.7  4132.7  4142.7  4152.7  4165.6  4205.6
  4215.6  4235.6  4245.6  4257.6  4275.6  4285.6  4295.6  4308.7  4338.7  4368.7
  4408.7  4515.7 4517.51  4517.6 4517.89    4518    4850  4977.6  5079.4  5188.2
  5263.6 5380.69  5380.8  5425.9    5426  5488.4 5488.51  5508.5    5618  5633.2
    74.2      73    71.3    70.9    72.4    72.7    71.7    70.6    71.2    70.6
    69.2    69.5    69.3   68.97   69.56   70.34   73.47   74.19   75.11   75.19
   75.28   75.37   75.45   75.54   75.62   75.71    75.8   75.88   75.99   76.34
   76.42   76.49   76.51    76.2   76.23   76.24   76.25   76.27   76.32   76.36
   76.41   76.58   76.58   76.58   76.59   79.49   87.62   88.26   88.21   87.21
    86.2   83.82   83.82   82.62   82.62   81.22   78.32   73.64    76.5    76.4
    74.2      73    71.3    70.9    72.4    72.7    71.7    70.6    71.2    70.6
    69.2    69.5    69.3   68.96    67.1    65.7    67.7   66.73    63.4    63.5
    64.5    62.7    62.3    62.9    62.5    63.2    63.1      62    63.2    62.6
      63    61.9    64.2   63.44    62.3      61      61    62.1    61.5    59.3
    54.7    50.3   50.35    71.3   71.31   71.31   79.44   80.08   80.03   79.03
   78.02   75.64      60      60      65      65      65      65      65      65
  1368.6  1538.6  1558.6  1568.6  1618.6  1708.6  1838.6  1868.6  1988.6  2043.1
  2733.1  3494.6  3618.4  3642.9  3778.4  3808.4  3928.4  3956.2  4062.7  4072.7
  4082.7  4092.7  4102.7  4112.7  4122.7  4132.7  4142.7  4152.7  4165.6  4205.6
  4215.6  4235.6  4245.6  4257.6  4275.6  4285.6  4295.6  4308.7  4338.7  4368.7
  4408.7  4515.7 4517.51  4517.6 4517.89    4518    4850  4977.6  5079.4  5188.2
  5263.6 5380.69  5380.8    5426  5488.4 5488.51  5508.5    5568    5618  5633.2
    74.2      73    71.3    70.9    72.4    72.7    71.7    70.6    71.2    70.6
    69.2    69.5    69.3   68.97   69.56   70.34   73.47   74.19   75.11   75.19
   75.28   75.37   75.45   75.54   75.62   75.71    75.8   75.88   75.99   76.34
   76.42   76.49   76.51    76.2   76.23   76.24   76.25   76.27   76.32   76.36
   76.41   76.58   76.58   76.58   76.59   79.49   87.62   88.26   88.21   87.21
    86.2   83.82   83.82   82.62   81.22   78.32   73.64    75.1    76.5    76.4
    73.3    72.1    70.4      70    71.5    71.8    70.8    69.7    70.3    69.7
    68.3    68.6    68.4   68.06    66.2    64.8    66.8   65.83    62.5    62.6
    63.6    61.8    61.4      62    61.6    62.3    62.2    61.1    62.3    61.7
    62.1      61    63.3   62.54    61.4    60.1    60.1    61.2    60.6    58.4
    53.8    49.4   49.45    70.4   70.41   70.41   78.54   79.18   79.13   78.13
   77.12   74.74    63.6   67.28   68.97   68.97   70.27    74.2    75.6    75.5
Pier Skew, UpSta & Num, DnSta & Num=  ,4618.9, 2 ,4618.9, 2 , 0 , 0 , 0 ,,
       3       3
   49.02   74.82
       3       3
   48.12   73.92
Pier Skew, UpSta & Num, DnSta & Num=  ,4733.7, 2 ,4733.7, 2 , 0 , 0 , 0 ,,
       3       3
   51.22   77.63
       3       3
   50.32   76.73
Pier Skew, UpSta & Num, DnSta & Num=  ,4850.4, 2 ,4850.4, 2 , 0 , 0 , 0 ,,
       3       3
   50.18   80.45
       3       3
   49.28   79.55
Pier Skew, UpSta & Num, DnSta & Num=  ,4905, 2 ,4905, 2 , 0 , 0 , 0 ,,
       3       3
   50.22   80.73
       3       3
   49.32   79.83
Pier Skew, UpSta & Num, DnSta & Num=  ,5025, 2 ,5025, 2 , 0 , 0 , 0 ,,
       3       3
   38.49   81.06
       3       3
   37.59   80.16
Pier Skew, UpSta & Num, DnSta & Num=  ,5144.3, 2 ,5144.3, 2 , 0 , 0 , 0 ,,
       3       3
   37.52   80.44
       3       3
   36.62   79.54
Pier Skew, UpSta & Num, DnSta & Num=  ,5262.8, 2 ,5262.8, 2 , 0 , 0 , 0 ,,
       3       3
   52.35   79.05
       3       3
   51.45   78.15
Abutment Skew #Up #Dn= , 2 , 2
  4517.4  4530.2
    71.3   50.71
  4517.4  4530.2
    70.4   49.81
BR Coef= 1 , 1 , 0 ,1.25, 0 ,,,.8,0,2,0,
WSPro=,,,, 1 ,,,, 0 ,,,, 0 ,,,,-1 ,-1 ,-1 , 0 , 0 , 0 , 0 , 0
BR U #Sta/Elev= 122
  1558.6   74.19  1728.6   72.99  1748.6   71.29  1758.6   70.89  1808.6   72.39
  1898.6   72.69  2028.6   71.69  2058.6   70.59  2178.6   71.19  2233.1   70.59
  2923.1   69.19  3684.6   69.49  3808.4   69.29  3832.9   68.95  3968.4   67.09
  3998.4   65.69  4068.4   66.69  4118.4   67.69  4146.2   66.72  4158.4   66.29
  4162.7   66.39  4252.7   63.39  4262.7   63.49  4272.7   64.49  4282.7   62.69
  4292.7   62.29  4302.7   62.89  4312.7   62.49  4322.7   63.19  4332.7   63.09
  4342.7   61.99  4345.6   62.29  4355.6   63.19  4395.6   62.59  4405.6   62.99
  4407.4   62.89  4425.6   61.89  4435.6   64.19  4447.4   63.44  4447.6   63.43
  4465.6   62.29  4475.6   60.99  4485.6   60.99  4495.6   61.89  4498.7   62.09
  4517.6   61.71  4528.7   61.49  4558.7   59.29  4589.6   55.74  4598.7   54.69
  4605.7   54.39 4697.25   52.38  4745.8   52.19 4748.51   52.36 4774.21   52.01
  4805.2   51.67 4826.99   51.57 4854.25   51.47 4863.87   51.86 4881.57   51.82
 4884.27   51.33 4885.81   50.96 4890.32   47.66 4894.07   45.97 4899.24   42.64
  4968.5   45.65 4970.54   46.88 4972.75    46.5 4978.34   49.14  4981.1      49
 4988.09   48.72 4997.42   48.43 5013.78   48.87 5021.34   49.25 5047.69    49.6
 5070.91   49.75 5098.72   49.68 5117.44   48.96  5122.1    48.1 5128.07    47.7
  5131.9   46.74 5135.99   45.43 5138.77   42.71 5141.45   41.16 5144.15   39.93
 5146.07      40 5157.12   35.62 5168.97   34.73  5176.8   33.43    5190   33.23
 5224.82   39.46 5235.16   41.64    5271   45.93 5284.09   51.23 5294.36   54.91
 5320.21   56.97 5322.67   63.06  5323.4   63.05 5334.53    62.9    5347   63.05
 5369.02   63.72  5412.6   65.65 5470.45   68.21 5473.49   67.55 5505.19   68.07
 5508.55   68.12 5554.88   69.63  5586.7   71.53  5595.5    70.2 5612.13   67.31
  5615.9   68.16    5616   68.17 5678.29   69.86  5678.4   69.86 5678.51   69.86
  5678.6   69.86  5678.8   69.87  5678.9   69.87  5698.5   71.16    5758   75.09
    5808   76.49  5823.2   76.39
BR U #Mann= 4
  1558.6      .2  4968.5    .055 4972.75     .04    5271      .2
BR U Banks=5098.72,5284.09
BR D #Sta/Elev= 150
  1368.6    73.4  1538.6    72.2  1558.6    70.5  1568.6    70.1  1618.6    71.6
  1708.6    71.9  1838.6    70.9  1868.6    69.8  1988.6    70.4  2043.1    69.8
  2733.1    68.4  3494.6    68.7  3618.4    68.5  3642.9   68.16  3778.4    66.3
  3808.4    64.9  3878.4    65.9  3928.4    66.9  3956.2   65.93  3968.4    65.5
  3972.7    65.6  4062.7    62.6  4072.7    62.7  4082.7    63.7  4092.7    61.9
  4102.7    61.5  4112.7    62.1  4122.7    61.7  4132.7    62.4  4142.7    62.3
  4152.7    61.2  4155.6    61.5  4165.6    62.4  4205.6    61.8  4215.6    62.2
  4217.4    62.1  4235.6    61.1  4245.6    63.4  4257.4   62.65  4257.6   62.64
  4275.6    61.5  4285.6    60.2  4295.6    60.2  4305.6    61.1  4308.7    61.3
  4327.6   60.92  4338.7    60.7  4368.7    58.5  4399.6   54.95  4408.7    53.9
  4415.7    53.6 4560.16    60.7 4561.94   60.76  4581.1   58.97 4600.38   56.85
 4602.93   56.54 4605.04   56.52 4605.87   56.42 4631.61   53.98 4653.05   52.53
 4660.52   51.16 4661.18   51.08 4662.97   51.04 4668.11   49.92 4672.11   50.05
 4672.74    49.9 4697.48   50.84 4723.75   51.59 4745.62   51.53 4768.64   51.01
 4773.63   50.36 4775.66   50.61 4785.18   50.49 4793.73   50.37 4794.85   50.21
 4798.04   50.26  4824.4   50.66 4838.27   51.08 4853.17   52.03 4858.03   52.08
 4875.02   52.23 4896.38   52.34 4898.32   52.07 4919.83   51.67 4929.84   51.16
 4937.25   45.98    4960    37.5 5002.08   37.02 5006.07   39.69 5006.95   41.23
 5011.61   41.24 5013.53   42.58 5017.56    42.6 5018.64   43.87 5023.92   43.88
 5025.03   45.41 5030.05   45.38 5031.78   46.85 5035.89   46.73 5036.85   48.29
  5044.9   47.97  5049.3   47.55 5064.23   48.08 5087.14   48.49 5104.12   48.26
 5110.62    47.9 5115.28    47.7 5115.87   47.91 5118.98   48.31 5120.71   46.63
 5122.52   45.42 5124.59   43.98 5126.25   42.58 5128.15   41.35 5130.02   40.02
 5131.59   38.48 5138.48   35.77 5157.01   34.51 5172.91   35.09 5185.73   37.08
 5195.82   40.47 5198.52   41.25 5204.11   44.63 5217.56   49.51 5229.93   51.41
 5253.68   55.45 5273.26   58.95 5295.44   63.79 5298.11   63.88 5299.29   63.99
  5305.7   63.69 5313.12   63.68 5323.03   62.46 5334.55   62.94 5336.13   63.11
 5354.82   66.37  5364.4   66.55  5366.4   66.63 5393.72   67.75 5426.38   69.16
 5488.29   69.07  5488.4   69.07 5488.51   69.07  5488.6   69.07  5488.8   69.08
  5488.9   69.08  5508.5   70.37    5568    74.3    5618    75.7  5633.2    75.6
BR D #Mann= 4
  1368.6      .2 4602.93    .055 4605.87     .04 5273.26      .2
BR D Banks=5118.98,5217.56
BC Design=,, 0 ,, 0 ,,,,,,
BC HTab HWMax=76.49

Type RM Length L Ch R = 1 ,214953.1,20,58,65
BEGIN DESCRIPTION:
Downstream Section of Bridge/Culvert/Weir
END DESCRIPTION:
XS GIS Cut Line= 6
 3059229.300029113844085.3198732 3059317.930101213842931.7998705
  3059622.350096 13841789.819871 3060023.079937613841288.8999411
 3060171.930033613840848.0901272 3060223.8098511 13840033.169841
#Sta/Elev= 30
  1368.6    73.4  1568.6    70.1  1708.6    71.9  2733.1    68.4  4399.6    68.5
    4492   71.73 4513.16   61.53 4561.94   60.76 4602.93   56.54 4605.87   56.42
 4668.11   49.92 4929.84   51.16 4937.25   45.98    4960    37.5 5002.08   37.02
 5006.95   41.23 5036.85   48.29 5118.98   48.31 5131.59   38.48 5138.48   35.77
 5157.01   34.51 5185.73   37.08 5217.56   49.51 5273.26   58.95 5299.29   63.99
 5323.03   62.46 5354.82   66.37  5488.6   69.07    5568    74.3  5633.2    75.6
#Mann= 4 ,-1 , 0
  1368.6      .2       0 4602.93    .055       0 4605.87     .04       0
 5273.26      .2       0
#XS Ineff= 2 , 0
            5010    70.2    5390            74.2
Permanent Ineff=
       F       F
#Block Obstruct= 1 ,-1
 4925.91    5036   48.29
Bank Sta=5118.98,5217.56
XS Rating Curve= 0
Exp/Cntr=.5,.3

Type RM Length L Ch R = 1 ,214895.5,171,171,171
BEGIN DESCRIPTION:
Upstream Section of Bridge/Culvert/Weir
END DESCRIPTION:
XS GIS Cut Line= 6
 3059272.552567313844161.1701152 3059629.1574971 13841807.063931
 3059906.484042213841476.1869681 3060138.425179413841038.4017544
 3060282.185390513840563.6415491 3060308.355285713840004.2916179
#Sta/Elev= 30
  1368.6    74.1  1538.6    72.9  1568.6    70.8  1708.6    72.6  1868.6    70.5
  2733.1    69.1  4338.7      70 4369.88   64.07 4373.84   61.61 4380.52   63.91
    4496   55.01 4645.65   52.78 4697.21   54.44 4697.97   52.83 4747.27   51.64
 4860.74   51.16 4881.63   48.72 4902.81   48.97 4935.93      41 4941.93   37.29
    5000   34.39 5022.46      36    5070  50.862 5111.88   58.71 5188.03   67.93
 5262.91   69.38 5312.08   67.42  5365.7    72.9  5633.2    76.3  5721.7      90
#Mann= 3 ,-1 , 0
  1368.6     .15       0 4860.74     .04       0    5070     .15       0
#XS Ineff= 2 , 0
            4840      70    5400            88.8
Permanent Ineff=
       F       F
Bank Sta=4902.81,5070
XS Rating Curve= 0
Exp/Cntr=.5,.3