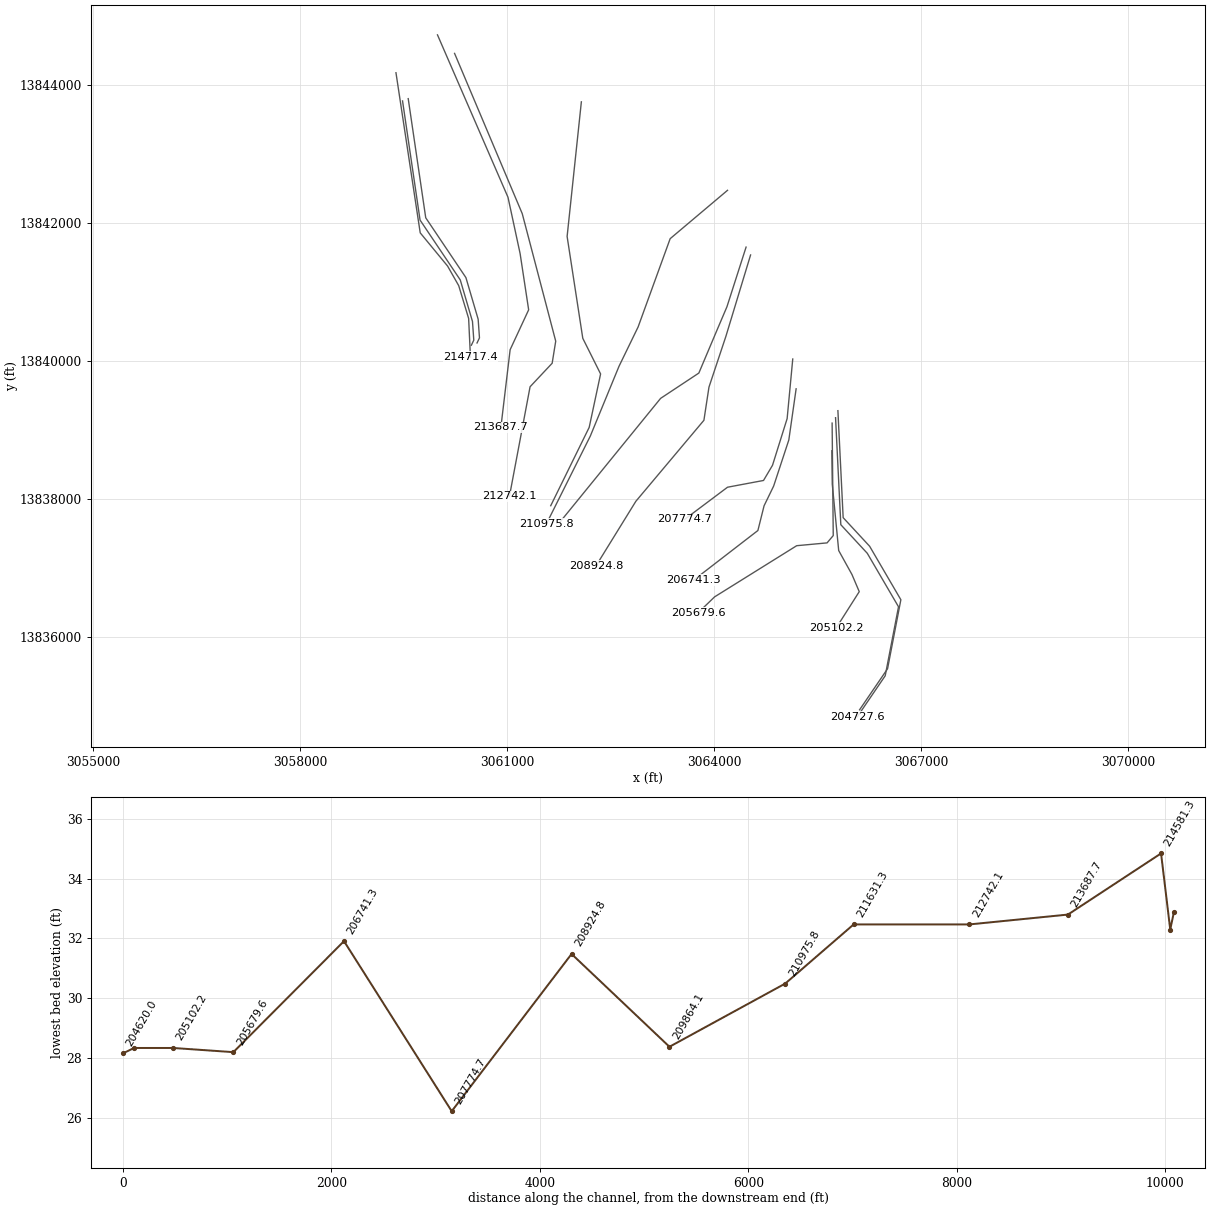
HEC-RAS study W100-00-00.prj: W100-00-00

--- W100-00-00.g01 (geometry) --- (continued)

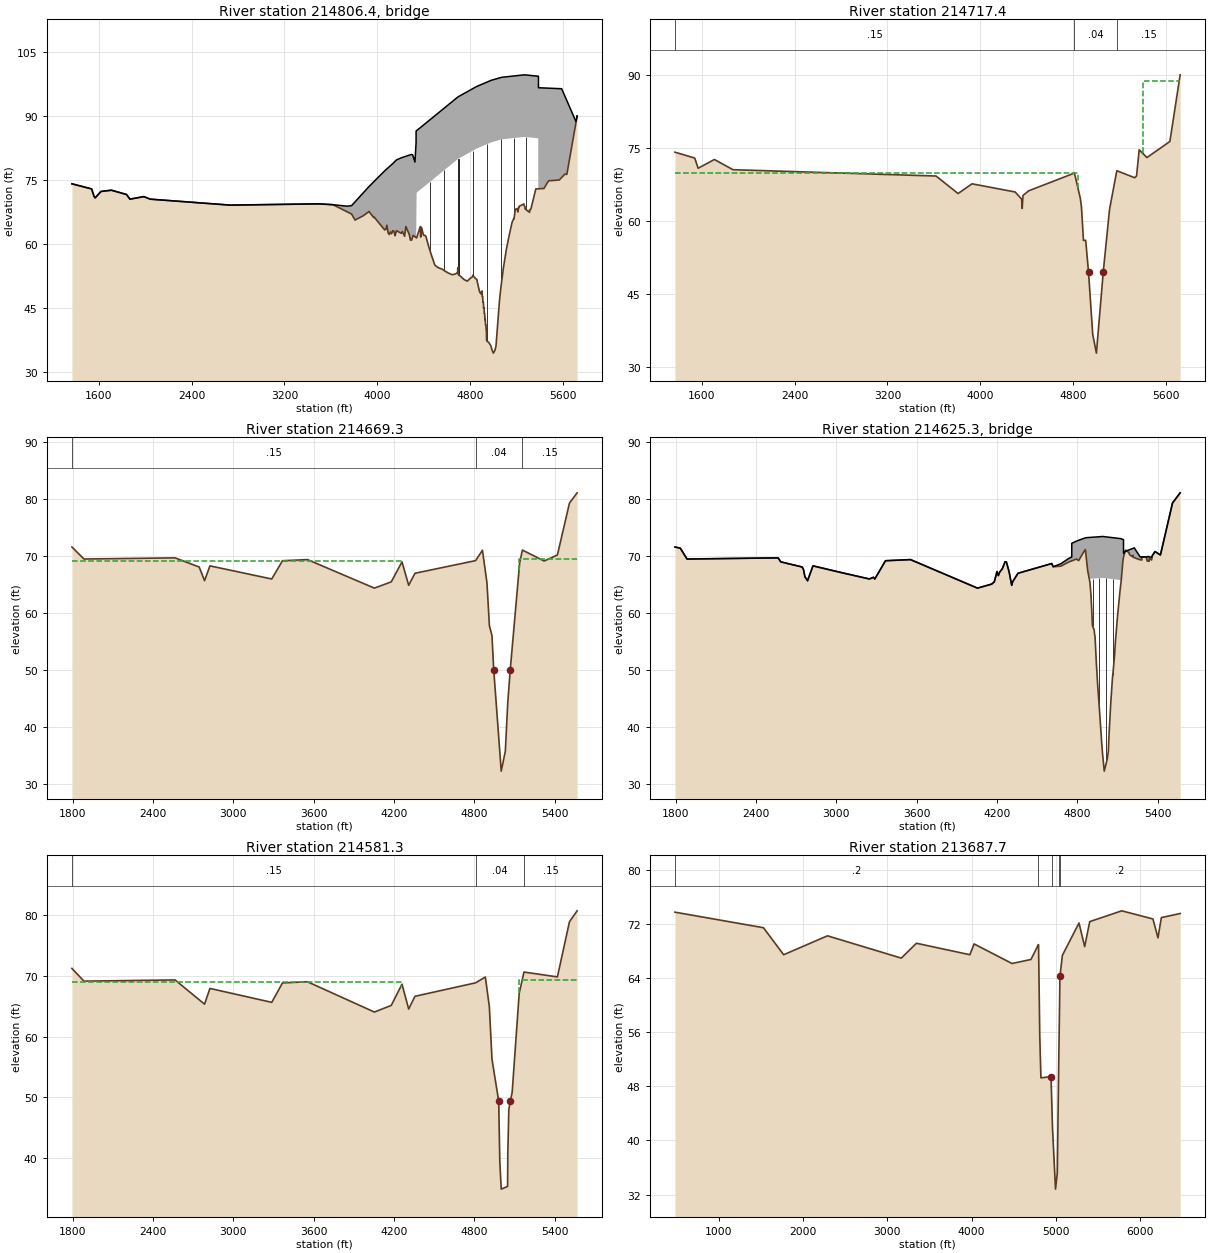
Type RM Length L Ch R = 3 ,214806.4,,,
BEGIN DESCRIPTION:
BELTWAY 8
Structure ID: WOO-71
END DESCRIPTION:
Bridge Culvert--1,0,-1,-1, 0
Deck Dist Width WeirC Skew NumUp NumDn MinLoCord MaxHiCord MaxSubmerge Is_Ogee
10,157,2.6,0, 60, 60, , , .95, 0, 1,1,,
  1368.6  1538.6  1558.6  1568.6  1618.6  1708.6  1838.6  1868.6  1988.6  2043.1
  2733.1  3494.6  3618.4  3740.5  3778.4  3808.4  3928.4  4062.7  4072.7  4082.7
  4092.7  4102.7  4112.7  4122.7  4132.7  4142.7  4152.7  4165.6  4205.6  4215.6
  4235.6  4245.6  4275.6  4285.6  4295.6  4304.4  4308.7  4324.4 4333.99  4334.1
  4334.7  4338.7  4696.3  4855.6    4981  5070.9  5267.7 5386.79  5386.9    5387
  5388.5 5388.61  5435.7  5475.7    5568  5588.5    5618  5633.2  5711.7  5721.7
    74.2      73    71.3    70.9    72.4    72.7    71.7    70.6    71.2    70.6
    69.2    69.5    69.3   68.95   69.08   69.98   73.56   77.22   77.47   77.71
   77.96   78.21   78.45    78.7   78.91   79.21   79.48   79.82   80.29   80.38
   80.56   80.65   80.93   81.02   81.09      81   80.63    79.3   83.88   86.58
   86.58   86.67   94.61   97.02   98.47   99.18   99.76   99.43   99.43   99.43
   99.43   96.73   96.68   96.63   96.52    96.5   94.66   93.71    88.8    90.1
  73.917  72.717  71.017  70.617  72.117  72.417  71.417  70.317  70.917  70.317
  68.917  69.217  69.017  67.337  66.817  65.417  67.417  63.117  63.217  64.217
  62.417  62.017  62.617  62.217  62.917  62.817  61.717  62.917  62.317  62.717
  61.617  63.917  62.017  60.717  60.717  61.507  61.817  61.507  61.307  61.307
  61.297   72.11   80.05   82.46   83.91   84.62    85.2   84.87   73.03  72.747
  72.747  72.747  72.817  74.617  74.817  75.387  76.217  76.117  88.267  89.817
  1368.6  1538.6  1558.6  1568.6  1618.6  1708.6  1838.6  1868.6  1988.6  2043.1
  2733.1  3494.6  3618.4  3740.5  3778.4  3808.4  3878.4  3928.4  4062.7  4072.7
  4082.7  4092.7  4102.7  4112.7  4122.7  4132.7  4142.7  4152.7  4165.6  4205.6
  4215.6  4235.6  4245.6  4275.6  4285.6  4295.6  4304.4  4308.7  4324.4 4333.99
  4334.1 4334.61  4334.7  4696.3  4855.6    4981  5070.9  5267.7 5386.79  5386.9
  5388.5 5388.61  5435.7  5475.7    5568  5588.5    5618  5633.2  5711.7  5721.7
    74.2      73    71.3    70.9    72.4    72.7    71.7    70.6    71.2    70.6
    69.2    69.5    69.3   68.95   69.08   69.98   72.14   73.56   77.22   77.47
   77.71   77.96   78.21   78.45    78.7   78.91   79.21   79.48   79.82   80.29
   80.38   80.56   80.65   80.93   81.02   81.09      81   80.63    79.3   83.88
   86.58   86.58   86.58   94.61   97.02   98.47   99.18   99.76   99.43   99.43
   99.43   96.73   96.68   96.63   96.52    96.5   94.66   93.71    88.8    90.1
   74.15   72.95   71.25   70.85   72.35   72.65   71.65   70.55   71.15   70.55
   69.15   69.45   69.25   67.57   67.05   65.65   66.65   67.65   63.35   63.45
   64.45   62.65   62.25   62.85   62.45   63.15   63.05   61.95   63.15   62.55
   62.95   61.85   64.15   62.25   60.95   60.95   61.74   62.05   61.74   61.54
   61.54   61.53   71.97      80   82.41   83.86   84.57   85.15   84.82   72.98
   72.98   72.98   73.05   74.85   75.05   75.62   76.45   76.35    88.5   90.05
Pier Skew, UpSta & Num, DnSta & Num=  ,4455.1, 2 ,4455.1, 2 , 0 , 0 , 0 ,,
       3       3
   62.24   75.78
       3       3
   62.19   75.73
Pier Skew, UpSta & Num, DnSta & Num=  ,4576.7, 2 ,4576.7, 2 , 0 , 0 , 0 ,,
       3       3
   64.05   78.45
       3       3
      64    78.4
Pier Skew, UpSta & Num, DnSta & Num=  ,4699.5, 2 ,4699.5, 2 , 0 , 0 , 0 ,,
       3       3
   65.65   81.12
       3       3
    65.6   81.07
Pier Skew, UpSta & Num, DnSta & Num=  ,4822.2, 2 ,4822.2, 2 , 0 , 0 , 0 ,,
       3       3
    69.3   82.97
       3       3
   69.25   82.92
Pier Skew, UpSta & Num, DnSta & Num=  ,4945.4, 2 ,4945.4, 2 , 0 , 0 , 0 ,,
       3       3
   47.21   84.52
       3       3
   47.16   84.47
Pier Skew, UpSta & Num, DnSta & Num=  ,5068.4, 2 ,5068.4, 2 , 0 , 0 , 0 ,,
       3       3
   50.22   85.61
       3       3
   50.17   85.56
Pier Skew, UpSta & Num, DnSta & Num=  ,5175.4, 2 ,5175.4, 2 , 0 , 0 , 0 ,,
       3       3
   70.06   85.93
       3       3
   70.01   85.88
Pier Skew, UpSta & Num, DnSta & Num=  ,5281.9, 2 ,5281.9, 2 , 0 , 0 , 0 ,,
       3       3
    68.7   86.16
       3       3
   68.65   86.11
Abutment Skew #Up #Dn= , 2 , 2
  4334.5  4364.7
   72.02    62.3
  4334.5  4364.7
   71.97   62.25
Abutment Skew #Up #Dn= , 2 , 2
  5345.2 5386.99
   69.41   84.87
  5345.2 5386.99
   69.36   84.82
BR Coef= 1 , 1 , 0 ,1.25, 0 ,,,.8,0,2,0,
WSPro=,,,, 1 ,,,, 0 ,,,, 0 ,,,,-1 ,-1 ,-1 , 0 , 0 , 0 , 0 , 0
BR U #Sta/Elev= 170
  1368.6    74.2  1538.6      73  1558.6    71.3  1568.6    70.9  1618.6    72.4
  1708.6    72.7  1838.6    71.7  1868.6    70.6  1988.6    71.2  2043.1    70.6
  2733.1    69.2  3494.6    69.5  3618.4    69.3  3740.5   67.62  3778.4    67.1
  3780.5      67  3800.5   66.07  3808.4    65.7  3820.5   65.87  3845.5   66.23
  3878.4    66.7  3895.5   67.04  3928.4    67.7  3960.5   66.58  3968.4    66.3
  3972.7    66.4  3985.5   65.97  3990.5   65.81  4010.5   65.14  4062.7    63.4
  4072.7    63.5  4082.7    64.5  4092.7    62.7  4102.7    62.3  4112.7    62.9
  4122.7    62.5  4125.5    62.7  4130.5   63.05  4132.7    63.2  4135.5   63.17
  4142.7    63.1  4152.7      62  4155.6    62.3  4165.6    63.2  4170.5   63.13
  4174.4   63.07  4205.6    62.6  4215.6      63  4235.6    61.9  4245.6    64.2
  4275.6    62.3  4285.6      61  4294.4      61  4295.6      61  4304.4   61.79
  4305.6    61.9  4308.7    62.1  4324.4   61.79 4333.99   61.59  4334.1   61.59
 4334.21   61.59  4334.4   61.59  4334.5   61.58 4334.61   61.58  4334.7   61.58
  4338.7    61.5 4369.88   64.17 4373.84   61.71 4379.58   63.98 4380.52   64.01
 4397.25   62.19  4407.5    62.1 4408.47    62.1 4412.18   62.09 4418.97   61.83
 4446.03    59.2 4468.72   57.27    4496   55.11 4525.22   54.53 4556.58   54.21
 4587.93   53.65  4617.4    53.2 4645.65   52.88 4675.34   53.07 4692.37   53.46
 4693.19   54.48 4697.21   54.54 4697.97   52.93 4724.04   52.34 4747.27   51.74
 4775.58   51.38 4799.63   52.01 4821.15   52.42 4821.97   52.75 4841.93   52.12
 4859.24    51.7 4860.74   51.26 4881.63   48.82 4892.77    48.4 4895.31   48.79
 4902.81   49.07 4904.64   47.74 4907.69   47.78 4909.89   46.39 4914.36   46.37
 4915.92   45.02 4920.45   45.15  4921.7   43.79  4925.1    43.8 4927.11   42.31
 4931.02    42.4 4932.27   41.05 4935.93    41.1  4938.3   39.78 4940.27   39.69
  4940.6   38.42 4941.93   37.39 4959.21   37.01  4976.8   36.31  4987.9   35.31
    5000   34.49 5012.42   35.08 5022.46    36.1 5034.49   40.35 5037.94   41.61
 5040.03   42.33 5052.45   46.72 5062.46   49.35    5070  50.962 5085.56   54.29
 5111.88   58.81 5136.38   62.12 5161.06   65.16 5179.78   66.31 5182.14   66.78
 5188.03   68.03 5191.94   68.25 5205.05   68.39 5210.79   67.61 5217.09   68.63
 5218.17   68.56 5224.14   68.96 5240.01   69.16 5262.91   69.48 5267.36   68.96
 5272.56    68.8 5273.07    68.8 5273.07   68.34 5292.46   67.91 5312.08   67.52
 5312.08   68.06 5312.65   68.06 5318.12   68.16 5323.62    68.3  5365.7      73
 5386.79   73.03  5386.9   73.03    5387   73.03  5387.2   73.03 5388.39   73.03
  5388.5   73.03 5388.61   73.03  5435.7    73.1  5475.7    74.9    5568    75.1
  5588.5   75.67    5618    76.5  5633.2    76.4  5711.7   88.55  5721.7    90.1
BR U #Mann= 3
  1368.6     .15 4860.74     .04    5070     .15
BR U Banks=4902.81,5070
BR D #Sta/Elev= 162
  1368.6   74.15  1538.6   72.95  1558.6   71.25  1568.6   70.85  1618.6   72.35
  1708.6   72.65  1838.6   71.65  1868.6   70.55  1988.6   71.15  2043.1   70.55
  2733.1   69.15  3494.6   69.45  3618.4   69.25  3740.5   67.57  3778.4   67.05
  3780.5   66.95  3800.5   66.02  3808.4   65.65  3820.5   65.82  3845.5   66.18
  3878.4   66.65  3895.5   66.99  3928.4   67.65  3960.5   66.53  3968.4   66.25
  3972.7   66.35  3985.5   65.92  3990.5   65.76  4010.5   65.09  4062.7   63.35
  4072.7   63.45  4082.7   64.45  4092.7   62.65  4102.7   62.25  4112.7   62.85
  4122.7   62.45  4125.5   62.65  4130.5      63  4132.7   63.15  4135.5   63.12
  4142.7   63.05  4152.7   61.95  4155.6   62.25  4165.6   63.15  4170.5   63.08
  4174.4   63.02  4205.6   62.55  4215.6   62.95  4235.6   61.85  4245.6   64.15
  4275.6   62.25  4285.6   60.95  4294.4   60.95  4295.6   60.95  4304.4   61.74
  4305.6   61.85  4308.7   62.05  4324.4   61.74 4355.63   64.51  4358.2   63.59
 4358.41   63.28 4360.72   62.59 4367.03   64.46 4367.29   65.25 4416.35   66.21
 4471.31   65.85 4519.94   66.45 4573.61   67.05 4604.61   67.41    4653   67.98
 4691.13   68.42 4691.63   68.91 4695.53      69  4698.2   68.98 4698.75   68.98
 4698.75   68.53 4717.97    68.8 4728.38   68.92 4728.38    69.4 4729.13    69.4
 4729.29   69.36 4745.77   69.62 4764.11   69.71 4766.74   69.71 4773.61   69.74
 4783.11    69.8  4783.7   69.76 4793.47   69.92 4811.06   69.86  4819.9   68.99
 4833.08   68.05 4861.38   64.68 4871.34   62.87 4876.51   60.96 4881.91   58.61
 4888.54   56.02 4892.41    56.1 4892.79   56.56 4899.03   56.56 4904.26    56.4
 4905.05   56.15 4907.74   56.03 4908.94   55.84 4915.18   54.23 4928.54   50.57
    4930  50.145    4932  49.563 4943.65   46.17    4945  45.641 4955.75   41.43
 4964.89   38.34 4967.27   37.38 4968.48   36.67 4977.59   34.55    5000   32.85
 5018.94   37.72 5021.07   37.79 5021.56   38.23 5023.81   39.46 5026.63   41.02
  5029.9   41.48 5035.02    43.1 5038.44   43.36 5040.94   44.27    5049  46.622
 5054.03   48.09    5059  49.517 5066.53   51.68 5073.69   53.36 5075.33   53.91
 5094.35   58.28 5113.25   62.39 5133.03   65.84 5155.36   68.25 5176.05   70.34
 5183.12   70.24 5184.43      70 5192.01   70.02 5197.93   69.97 5199.09   70.37
  5208.2   70.54 5228.63   70.51 5255.31   70.15 5273.18    69.4 5274.87   69.33
 5275.43   69.33 5275.43   68.81 5303.43   69.13 5329.84    68.9 5329.84    69.5
 5330.38    69.5 5339.92   69.34  5345.9   69.27 5368.87   74.64  5435.7   73.05
  5475.7   74.85    5568   75.05  5588.5   75.62    5618   76.45  5633.2   76.35
  5711.7    88.5  5721.7   90.05
BR D #Mann= 3
  1368.6     .15 4811.06     .04 5176.05     .15
BR D Banks=4932,5059
BC Design=,, 0 ,, 0 ,,,,,,
BC HTab HWMax=90

Type RM Length L Ch R = 1 ,214717.4,35,35,35
BEGIN DESCRIPTION:
Downstream Section of Bridge/Culvert/Weir
END DESCRIPTION:
XS GIS Cut Line= 6
 3059392.800030213844176.7701496 3059744.2999834 13841856.429974
 3060140.830030213841375.2199784 3060301.990140913841091.2300608
  3060445.75002413840616.4698555 3060471.910076713840057.1199244
#Sta/Elev= 30
  1368.6   74.18  1538.6   72.98  1568.6   70.88  1708.6   72.68  1868.6   70.58
  3618.4   69.28  3808.4   65.68  3928.4   67.68    4300      66 4355.63   64.54
 4360.72   62.62 4367.29   65.28 4416.35   66.24 4811.06   69.89 4861.38   64.71
 4871.34    62.9 4888.54   56.05 4907.74   56.06    4932  49.593 4968.48    36.7
    5000   32.88    5059  49.547 5113.25   62.42 5176.05   70.37 5329.84   68.93
  5345.9    69.3 5368.87   74.67  5435.7   73.08  5633.2   76.38  5721.7   90.08
#Mann= 3 ,-1 , 0
  1368.6     .15       0 4811.06     .04       0 5176.05     .15       0
#XS Ineff= 2 , 0
            4840    69.9    5400            88.8
Permanent Ineff=
       F       F
Bank Sta=4932,5059
XS Rating Curve= 0
Exp/Cntr=.5,.3

Type RM Length L Ch R = 1 ,214669.3,88.5,88.1,90.7
BEGIN DESCRIPTION:
Upstream Section of Bridge/Culvert/Weir
END DESCRIPTION:
XS GIS Cut Line= 6
 3059488.069852813843768.3798903 3059741.920066913842041.6100499
 3060324.280122613841174.7200513 3060501.559951813840571.9699445
 3060520.519887613840301.7900387 3060485.3700235 13840228.019845
#Sta/Elev= 30
  1795.7   71.57  1885.7   69.47  2565.7   69.67  2745.7   68.07  2785.7   65.67
  2825.7   68.27  3287.2   65.97  3367.2   69.17  3553.5   69.37  4053.5   64.37
  4179.3   65.47  4259.3   68.97  4309.3   64.87    4356   66.97  4808.7   69.19
 4859.88   71.01 4893.39   65.33 4911.73    57.8 4930.85   56.05    4944  50.064
    5000    32.3  5030.6    35.8 5048.83   44.33    5067   49.97 5137.71   68.82
 5158.14   71.04  5320.7   69.12  5419.3   70.17  5509.3   79.27  5566.5   81.07
#Mann= 3 ,-1 , 0
  1795.7     .15       0  4808.7     .04       0 5158.14     .15       0
#XS Ineff= 2 , 0
            4250    69.1 5132.51            69.4
Permanent Ineff=
       F       F
Bank Sta=4944,5067
XS Rating Curve= 0
Exp/Cntr=.5,.3

Type RM Length L Ch R = 3 ,214625.3,,,
BEGIN DESCRIPTION:
SAM HOUSTON PARKWAY
Structure ID: WOO-70
END DESCRIPTION:
Bridge Culvert--1,0,-1,-1, 0
Deck Dist Width WeirC Skew NumUp NumDn MinLoCord MaxHiCord MaxSubmerge Is_Ogee
10,68.6,2.6,0, 56, 54, , , .95, 0, 1,1,,
  1795.7  1835.7  1885.7  2565.7  2585.7  2745.7  2755.7  2765.7  2785.7  2825.7
  3247.2  3277.2  3287.2  3367.2  3553.5  4053.5  4159.3  4179.3  4199.3  4209.3
  4219.3  4239.3  4259.3  4269.3  4289.3  4309.3    4316    4356  4608.1  4618.7
  4676.7  4733.3 4757.39  4757.5    4793  4845.4    4864  4884.1  4989.3 5126.53
  5143.7 5143.81  5157.6  5224.6  5235.5  5269.1  5320.7  5327.6  5335.1  5335.3
  5353.2    5359    5379  5419.3  5509.3  5566.5
    71.6    71.4    69.5    69.7      69    68.1    67.6    66.4    65.7    68.3
      66    66.3      66    69.2    69.4    64.4    65.1    65.5    67.3    66.6
    67.2    67.8      69      69    67.3    64.9    65.5      67   68.71   68.15
   68.68   69.58   69.85   72.25   72.64    73.1   73.24   73.27   73.45   73.06
   72.88   70.48   70.85   71.46   71.03   69.84   69.88   69.96    69.9    69.9
   69.77   70.11   70.81   70.21   79.31    81.1
    71.6    71.4    69.5    69.7      69    68.1    67.6    66.4    65.7    68.3
      66    66.3      66    69.2    69.4    64.4    65.1    65.5    67.3    66.6
    67.2    67.8      69      69    67.3    64.9    65.5      67    68.7   68.14
   68.25   68.96   69.18   69.18    69.5   68.57   66.92   66.01   66.19    65.8
   69.65   69.65   69.65   69.65   69.45    69.1   69.15   69.13   69.11   69.66
   69.32    70.1    70.8    70.2    79.3    81.1
  1795.7  1835.7  1885.7  2565.7  2585.7  2745.7  2755.7  2765.7  2785.7  2825.7
  3247.2  3277.2  3287.2  3367.2  3553.5  4053.5  4159.3  4179.3  4199.3  4209.3
  4219.3  4239.3  4259.3  4269.3  4289.3  4309.3    4316    4356  4608.1  4618.7
  4676.7  4733.3 4757.39  4757.5    4793  4845.4    4864  4884.1  4989.3  5113.7
  5143.7 5143.81  5157.6  5183.1  5224.6  5269.1  5320.7  5327.6  5353.2    5359
    5379  5419.3  5509.3  5566.5
    71.6    71.4    69.5    69.7      69    68.1    67.6    66.4    65.7    68.3
      66    66.3      66    69.2    69.4    64.4    65.1    65.5    67.3    66.6
    67.2    67.8      69      69    67.3    64.9    65.5      67   68.71   68.15
   68.68   69.58   69.85   72.25   72.64    73.1   73.24   73.27   73.45    73.1
   72.88   70.48   70.85   71.08   71.46   69.84   69.88   69.96   69.77   70.11
   70.81   70.21   79.31    81.1
   71.28   71.08   69.18   69.38   68.68   67.78   67.28   66.08   65.38   67.98
   65.68   65.98   65.68   68.88   69.08   64.08   64.78   65.18   66.98   66.28
   66.88   67.48   68.68   68.68   66.98   64.58   65.18   66.68   68.38   67.82
   67.93   68.64   68.86   68.86   69.18   68.25    66.6   65.69   65.87   65.52
   65.44   65.44      66      67      68      68      68      68      68   69.78
   70.48   69.88   78.98   80.78
Pier Skew, UpSta & Num, DnSta & Num=  ,4913.7, 2 ,4913.7, 2 , 0 , 0 , 0 ,,
     1.5     1.5
   53.95   67.06
     1.5     1.5
   53.63   66.74
Pier Skew, UpSta & Num, DnSta & Num=  ,4963.7, 2 ,4963.7, 2 , 0 , 0 , 0 ,,
     1.5     1.5
   39.23   67.15
     1.5     1.5
   38.91   66.83
Pier Skew, UpSta & Num, DnSta & Num=  ,5013.7, 2 ,5013.7, 2 , 0 , 0 , 0 ,,
     1.5     1.5
   35.32   67.12
     1.5     1.5
      35    66.8
Pier Skew, UpSta & Num, DnSta & Num=  ,5063.7, 2 ,5063.7, 2 , 0 , 0 , 0 ,,
     1.5     1.5
   52.12   66.98
     1.5     1.5
    51.8   66.66
Abutment Skew #Up #Dn= , 2 , 2
  5077.2 5131.39
    51.9   65.84
    5088 5142.19
   51.58   65.52
BR Coef= 1 , 1 , 0 ,1.25, 0 ,,,.8,0,2,0,
WSPro=,,,, 1 ,,,, 0 ,,,, 0 ,,,,-1 ,-1 ,-1 , 0 , 0 , 0 , 0 , 0
BR U #Sta/Elev= 108
  1795.7    71.6  1835.7    71.4  1885.7    69.5  2565.7    69.7  2585.7      69
  2745.7    68.1  2755.7    67.6  2765.7    66.4  2785.7    65.7  2825.7    68.3
  3037.2    67.1  3247.2      66  3277.2    66.3  3287.2      66  3367.2    69.2
  3553.5    69.4  4053.5    64.4  4159.3    65.1  4179.3    65.5  4199.3    67.3
  4209.3    66.6  4219.3    67.2  4239.3    67.8  4259.3      69  4269.3      69
  4289.3    67.3  4309.3    64.9    4316    65.5    4356      67  4585.4   68.55
  4608.1    68.7  4615.9   68.29  4618.7   68.14  4676.7   68.25  4707.7   68.64
  4733.3   68.96  4733.5   68.96 4757.39   69.18  4757.5   69.18 4757.61   69.18
    4793    69.5  4808.7   69.22 4843.54   70.61 4858.54   71.14 4859.88   71.04
 4875.71   67.56 4893.39   65.36 4901.18   63.08 4905.88   60.82 4911.73   57.83
 4917.88   57.42 4924.18   57.18 4925.58   56.89 4927.79   56.21 4930.85   56.08
 4931.46   55.78 4941.35   51.12    4944  50.094 4950.62   47.53 4960.78   44.17
 4969.11   41.39 4977.87    38.4 4979.81   37.57 4986.61   35.56    5000   32.33
 5021.99   34.39  5030.6   35.83 5034.57   38.23 5038.15   39.79  5040.5  40.796
 5048.83   44.36 5060.73   48.52 5064.83   49.43    5067      50  5077.2   52.68
 5082.86   54.94 5100.16   59.71 5117.44   63.88 5125.73   65.54 5132.51    67.3
 5137.71   68.85 5142.63   69.72 5158.14   71.07 5184.99   70.61 5187.78    70.3
 5200.08   70.06 5210.42   69.94 5214.06   70.16 5216.54   69.82 5253.34   69.47
 5280.21   69.31 5280.21   69.88 5281.36   69.88 5282.89   69.89 5313.34   69.83
  5320.7   69.15  5327.6   69.13  5335.1   69.11  5335.3   69.66  5353.1   69.32
  5353.2   69.32    5359    70.1    5379    70.8  5419.3    70.2  5484.7   76.81
  5509.3    79.3  5544.7   80.41  5566.5    81.1
BR U #Mann= 3
  1795.7     .15  4808.7     .04 5158.14     .15
BR U Banks=4944,5067
BR D #Sta/Elev= 97
  1795.7   71.28  1835.7   71.08  1885.7   69.18  2565.7   69.38  2585.7   68.68
  2745.7   67.78  2755.7   67.28  2765.7   66.08  2785.7   65.38  2825.7   67.98
  3037.2   66.78  3247.2   65.68  3277.2   65.98  3287.2   65.68  3367.2   68.88
  3553.5   69.08  4053.5   64.08  4159.3   64.78  4179.3   65.18  4199.3   66.98
  4209.3   66.28  4219.3   66.88  4239.3   67.48  4259.3   68.68  4269.3   68.68
  4289.3   66.98  4309.3   64.58    4316   65.18    4356   66.68  4585.4   68.23
  4608.1   68.38  4615.9   67.97  4618.7   67.82  4676.7   67.93  4707.7   68.32
  4733.3   68.64  4733.5   68.64 4757.39   68.86  4757.5   68.86 4757.61   68.86
    4793   69.18  4808.7   68.68 4844.38   70.16 4863.87   69.58 4865.04   69.67
 4881.55   69.64 4882.31   69.41 4899.59   67.18 4911.33   64.74 4922.29   59.25
 4929.43   56.55 4931.06   56.08 4937.19   55.92 4941.94   55.72 4942.65   55.56
 4951.85   53.87 4962.68   52.68 4971.53   49.51 4981.06   49.18 4984.83   45.14
  4986.7   43.47  4989.5   39.15    5000   34.65 5010.66   35.09 5024.97   34.71
  5040.5  34.974 5047.35   35.09 5049.07   40.39  5056.7   47.79 5067.97   49.18
 5081.63    50.6 5097.81      55 5115.47   60.67 5134.11   66.94 5143.66   68.53
 5154.36   69.48 5165.61   69.94 5169.89   70.46 5183.98   69.94 5189.95   70.33
 5211.57    70.1 5237.86   70.13 5288.23   70.09 5318.38   69.09  5320.7   68.61
  5327.6   68.81  5335.1   68.79  5335.3   69.34  5353.1      69  5353.2      69
    5359   69.78    5379   70.48  5419.3   69.88  5484.7   76.49  5509.3   78.98
  5544.7   80.09  5566.5   80.78
BR D #Mann= 3
  1795.7     .15  4808.7     .04 5169.89     .15
BR D Banks=4981.06,5067.97
BC Design=,, 0 ,, 0 ,,,,,,
BC HTab HWMax=81.07

Type RM Length L Ch R = 1 ,214581.3,896.5,893.57,896.5
BEGIN DESCRIPTION:
Downstream Section of Bridge/Culvert/Weir
END DESCRIPTION:
XS GIS Cut Line= 6
 3059570.309845813843801.3299556 3059824.160059913842074.5699577
 3060406.520115613841207.6799592 3060583.799944813840604.9298524
 3060602.759880613840334.7499465 3060567.610016513840260.9800809
#Sta/Elev= 30
  1795.7   71.26  1885.7   69.16  2565.7   69.36  2785.7   65.36  2825.7   67.96
  3287.2   65.66  3367.2   68.86  3553.5   69.06  4053.5   64.06  4179.3   65.16
  4259.3   68.66  4309.3   64.56    4356   66.66  4808.7   68.88 4881.55   69.84
 4911.33   64.94 4931.06   56.28 4981.06   49.38  4989.5   39.35    5000   34.85
 5047.35   35.29 5049.07   40.59  5056.7   47.99 5067.97   49.38 5081.63    50.8
 5134.11   67.14 5169.89   70.66  5419.3   69.86  5509.3   78.96  5566.5   80.76
#Mann= 3 ,-1 , 0
  1795.7     .15       0  4808.7     .04       0 5169.89     .15       0
#XS Ineff= 2 , 0
            4250    69.1 5134.11            69.4
Permanent Ineff=
       F       F
Bank Sta=4981.06,5067.97
XS Rating Curve= 0
Exp/Cntr=.5,.3

Type RM Length L Ch R = 1 ,213687.7,844.9,945.6,792
BEGIN DESCRIPTION:
Cross Section 213687.7
END DESCRIPTION:
XS GIS Cut Line= 6
 3059994.339837613844725.2700368  3061016.17014313842371.9601109
 3061191.639936513841556.5499963 3061315.499924913840741.1500524
 3061047.139897413840163.1400535 3060912.960047613839038.0901383
#Sta/Elev= 30
   479.5    73.8  1529.5    71.5  1769.5    67.5  2289.5    70.3  3165.1      67
  3345.1    69.2  3979.2    67.5  4029.2    69.1  4479.2    66.2  4703.9    66.8
  4791.6   68.99  4793.9      69  4808.5   55.36  4822.1   49.27  4941.8   49.46
  4959.4    41.9  4995.2    32.8  5016.3   35.16  5032.6   50.62  5047.9    64.3
  5050.4   64.58  5076.7   67.41  5273.9    72.2  5341.2    68.7  5401.2    72.4
  5781.2      74  6151.2    72.8  6211.2      70  6251.2      73  6474.2    73.6
#Mann= 5 ,-1 , 0
   479.5      .2       0  4791.6     .15       0  4959.4     .05       0
  5032.6     .15       0  5050.4      .2       0
Bank Sta=4941.8,5047.9
XS Rating Curve= 0
Exp/Cntr=.3,.1

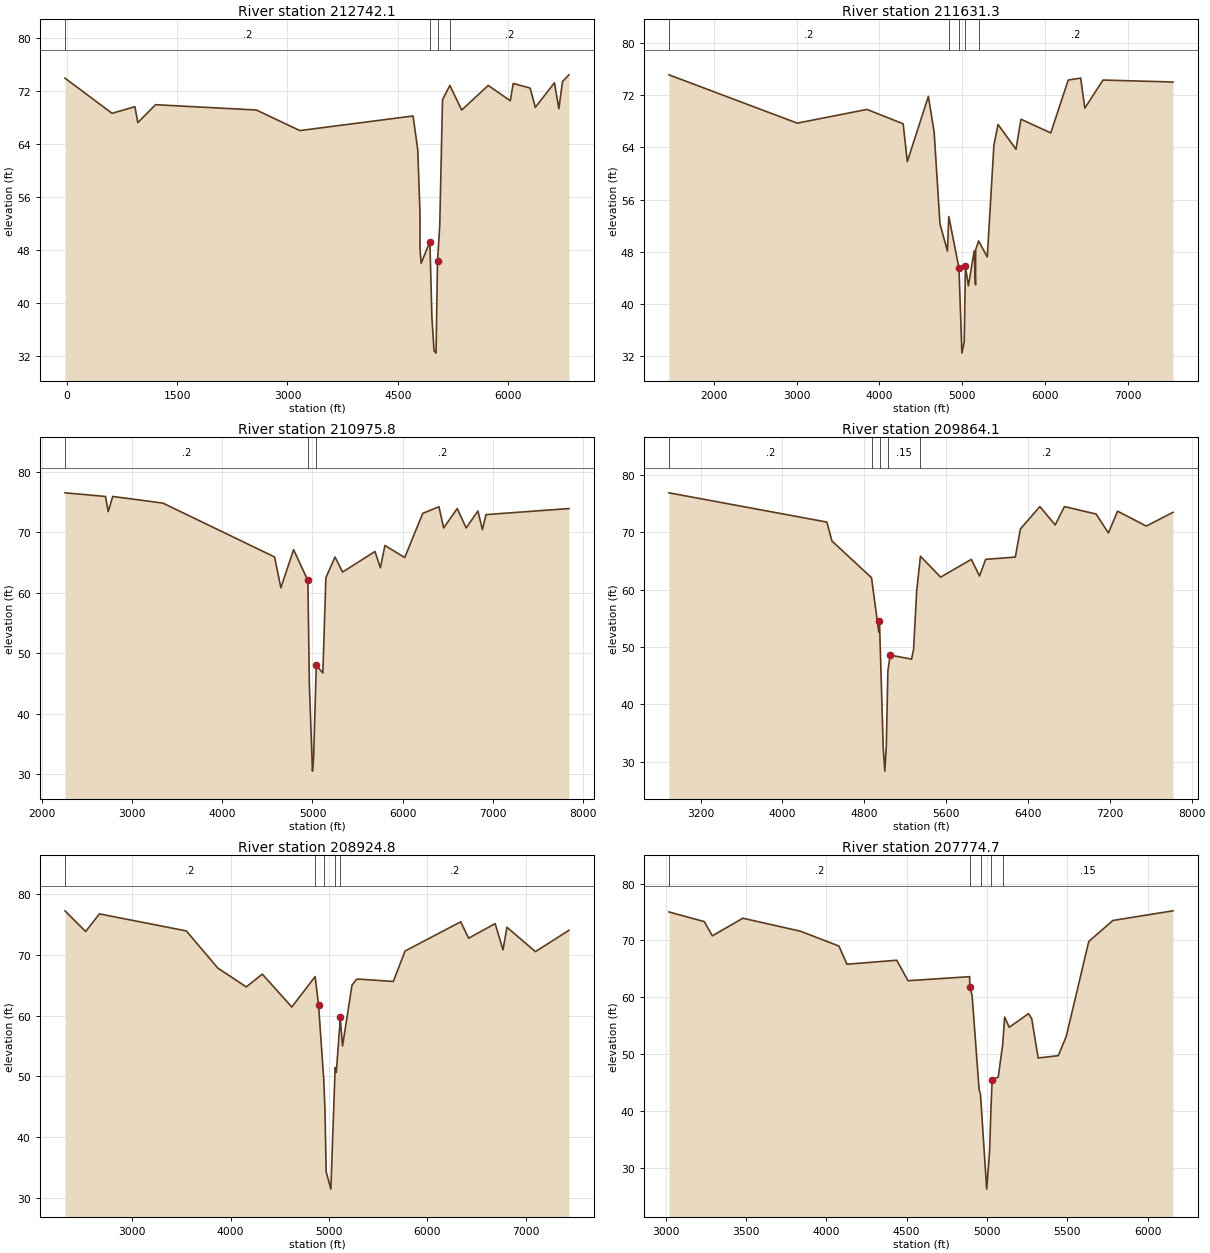
Type RM Length L Ch R = 1 ,212742.1,730.9,1110.8,1018.4
BEGIN DESCRIPTION:
Cross Section 212742.1
END DESCRIPTION:
XS GIS Cut Line= 6
      3060242.05     13844456.91       3061222.6     13842134.56
      3061707.72       13840287.      3061656.11     13839967.03
      3061336.14     13839626.42      3061036.81      13838036.9
#Sta/Elev= 30
   -23.3    73.9   616.7    68.6   926.7    69.6   966.7    67.2  1206.7    69.9
  2577.6    69.1  3167.6      66  4706.5    68.2  4770.6    63.1  4800.6    53.6
  4801.4   48.09  4816.4   46.01  4935.3   49.24  4962.9   37.86    4992   32.82
  5018.8   32.47  5039.1   46.33  5069.6   51.78    5107   70.67  5206.7    72.8
  5367.9    69.1  5727.9    72.8  6027.9    70.5  6067.9    73.1  6297.9    72.4
  6367.9    69.5  6627.9    73.2  6687.9    69.3  6737.9    73.4  6825.4    74.4
#Mann= 4 ,-1 , 0
   -23.3      .2       0  4935.3     .05       0  5039.1     .15       0
  5206.7      .2       0
Bank Sta=4935.3,5039.1
XS Rating Curve= 0
Exp/Cntr=.3,.1

Type RM Length L Ch R = 1 ,211631.3,751.4,655.5,492.9
BEGIN DESCRIPTION:
Cross Section 211631.3
END DESCRIPTION:
XS GIS Cut Line= 6
      3062079.29     13843755.04      3061872.86     13841804.27
      3062099.93     13840328.29      3062357.97     13839812.21
      3062192.83     13839038.09      3061635.46     13837902.72
#Sta/Elev= 30
  1456.5    75.1  3006.5    67.7  3848.2    69.8  4286.2    67.6  4336.2    61.8
  4590.6    71.8  4660.6    66.3  4730.6    52.3  4820.6    48.1  4837.3    53.4
  4960.3   45.53  4995.9   32.47  5024.2   34.25  5037.9   45.76  5074.4   42.78
    5144   48.13  5160.1   42.94  5162.3    48.3  5197.4   49.66  5302.3    47.2
  5382.3    64.3  5432.3    67.5  5649.3    63.7  5709.3    68.3  6069.3    66.2
  6280.8    74.3  6430.8    74.6  6480.8      70  6700.8    74.3  7545.6      74
#Mann= 5 ,-1 , 0
  1456.5      .2       0  4837.3     .15       0  4960.3     .05       0
  5037.9     .15       0  5197.4      .2       0
Bank Sta=4960.3,5037.9
XS Rating Curve= 0
Exp/Cntr=.3,.1

Type RM Length L Ch R = 1 ,210975.8,1084,1111.7,923.5
BEGIN DESCRIPTION:
Cross Section 210975.8
END DESCRIPTION:
XS GIS Cut Line= 6
      3064197.22     13842472.98      3063366.08     13841772.22
      3062901.63     13840492.93      3062624.58     13839922.54
      3062209.01     13838912.14      3061573.44     13837640.99
#Sta/Elev= 30
    2252    76.5    2702    75.9    2732    73.4    2782    75.9  3339.1    74.8
  4579.1    65.9  4649.1    60.8  4790.1    67.1  4948.9   62.01  4965.3   44.86
  4999.8   30.49  5012.5    32.7  5042.1   47.96  5115.3   46.73  5148.7   62.45
  5250.1    65.9  5334.2    63.4  5694.2    66.8  5754.2    64.1  5804.2    67.8
  6024.2    65.8  6224.2    73.1  6404.2    74.2  6456.8    70.7  6606.8    73.9
  6706.8    70.7  6836.8    73.5  6886.8    70.4  6926.8    72.9    7848    73.9
#Mann= 3 ,-1 , 0
    2252      .2       0  4948.9     .05       0  5042.1      .2       0
Bank Sta=4948.9,5042.1
XS Rating Curve= 0
Exp/Cntr=.3,.1

Type RM Length L Ch R = 1 ,209864.1,760.6,939.3,863.1
BEGIN DESCRIPTION:
Cross Section 209864.1
END DESCRIPTION:
XS GIS Cut Line= 6
      3064466.12       13841650.      3064189.07     13840786.27
       3064026.1     13840403.29      3063781.65     13839824.76
      3063227.56     13839458.08        3061769.     13837665.43
#Sta/Elev= 30
  2890.5    76.9  4433.8    71.8  4483.8    68.5  4870.5    62.1  4941.8    52.6
  4948.3   54.61  4953.7   51.28  4984.9   32.55  5000.8   28.37  5015.1   32.69
  5030.5   45.83  5052.7    48.6  5261.8    47.9  5281.8    49.6  5311.8    59.7
  5348.9   65.84  5546.3    62.2  5846.3    65.3  5926.3    62.4  5986.3    65.3
  6276.3    65.7  6326.3    70.6  6516.3    74.5  6666.3    71.3  6756.3    74.5
  7066.3    73.2  7186.3    69.9  7276.3    73.7  7556.3    71.1  7817.3    73.5
#Mann= 5 ,-1 , 0
  2890.5      .2       0  4870.5     .15       0  4953.7     .05       0
  5030.5     .15       0  5348.9      .2       0
Bank Sta=4948.3,5052.7
XS Rating Curve= 0
Exp/Cntr=.3,.1

Type RM Length L Ch R = 1 ,208924.8,1216.9,1150.1,998.9
BEGIN DESCRIPTION:
Cross Section 208924.8
END DESCRIPTION:
XS GIS Cut Line= 6
       3064531.3     13841535.92      3064172.77      13840354.4
      3063928.32     13839621.05      3063854.99     13839140.29
      3062869.03     13837966.92       3062290.5     13837029.86
#Sta/Elev= 30
  2314.1    77.2  2524.1    73.8  2664.1    76.7  3548.8    73.9  3868.8    67.8
  4158.8    64.7  4321.8    66.8  4621.8    61.4  4859.5    66.4  4894.1   61.71
  4946.6   49.57  4959.1   44.57  4971.6   34.32  5019.3   31.48  5062.9   51.46
  5074.5   50.65  5112.2   58.86  5114.3    59.7  5138.2      55  5234.4      65
  5284.4      66  5654.4    65.6  5774.4    70.6  6340.8    75.4  6420.8    72.7
  6690.8    75.1  6770.8    70.8  6810.8    74.5  7100.8    70.5    7442      74
#Mann= 5 ,-1 , 0
  2314.1      .2       0  4859.5     .15       0  4946.6     .05       0
  5062.9     .15       0  5112.2      .2       0
Bank Sta=4894.1,5114.3
XS Rating Curve= 0
Exp/Cntr=.3,.1

Type RM Length L Ch R = 1 ,207774.7,445.1,1033.4,952.1
BEGIN DESCRIPTION:
Cross Section 207774.7
END DESCRIPTION:
XS GIS Cut Line= 6
      3065142.43     13840028.47      3065060.95     13839164.74
      3064849.09     13838488.42      3064718.72     13838268.42
      3064197.22     13838170.63      3063577.94     13837706.18
#Sta/Elev= 30
  3020.8      75  3240.8    73.3  3290.8    70.8  3480.8    73.9  3840.8    71.6
  4078.8      69  4128.8    65.8  4438.8    66.5  4508.8    62.9  4892.4   63.61
  4893.8   61.77  4907.8   60.31  4951.6   43.69  4960.1   42.87  4998.7   26.21
  5016.9   32.88  5025.1   40.39  5032.8   45.49  5070.4   45.92  5098.2   51.63
  5110.4    56.5  5139.1    54.7  5259.1    57.1  5279.1    56.2  5319.1    49.3
    5444    49.7    5494    53.1    5634    69.8    5784    73.5  6158.1    75.2
#Mann= 5 ,-1 , 0
  3020.8      .2       0  4892.4     .15       0  4960.1     .05       0
  5025.1     .15       0  5098.2     .15       0
Bank Sta=4893.8,5032.8
XS Rating Curve= 0
Exp/Cntr=.3,.1

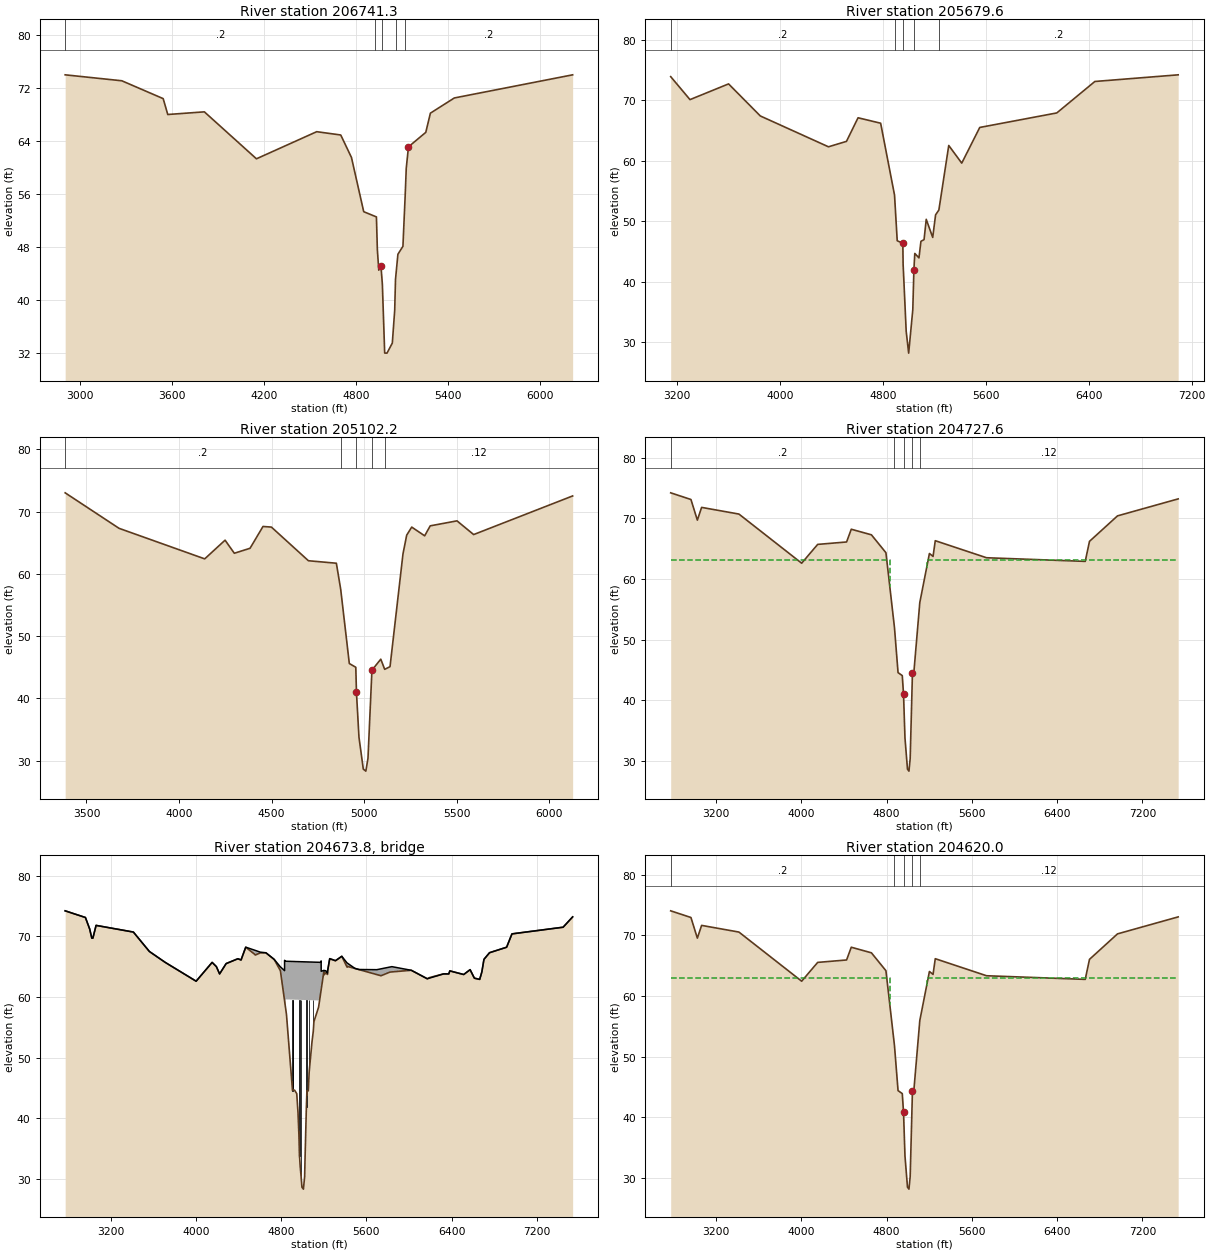
Type RM Length L Ch R = 1 ,206741.3,1125.8,1061.7,819.2
BEGIN DESCRIPTION:
Cross Section 206741.3
END DESCRIPTION:
XS GIS Cut Line= 6
      3065191.32      13839596.6      3065085.39      13838855.1
      3064865.39     13838186.93      3064726.87     13837901.74
      3064637.23     13837543.21      3063708.32     13836826.15
#Sta/Elev= 30
  2901.9      74  3271.9    73.1  3541.9    70.4  3571.9      68  3810.9    68.4
  4150.9    61.3  4544.4    65.4  4701.4    64.9  4771.4    61.5  4851.4    53.3
    4928   52.57  4934.3   52.51  4940.4   47.59  4949.7   44.46    4964   45.06
  4973.1   42.35  4988.3   31.92  5003.3   31.91  5038.1   33.43  5053.7    38.4
  5058.9   43.05  5074.6   46.86  5107.4   48.06  5122.3   55.84  5129.1   59.86
  5143.6   63.11  5256.7    65.3  5286.7    68.2    5443    70.5  6215.6      74
#Mann= 5 ,-1 , 0
  2901.9      .2       0    4928     .12       0  4973.1     .05       0
  5058.9     .12       0  5122.3      .2       0
Bank Sta=4964,5143.6
XS Rating Curve= 0
Exp/Cntr=.3,.1

Type RM Length L Ch R = 1 ,205679.6,162.4,577.4,846.2
BEGIN DESCRIPTION:
Cross Section 205679.6
END DESCRIPTION:
XS GIS Cut Line= 6
      3065712.82     13839099.55      3065729.12     13837469.87
      3065639.48     13837363.94      3065199.47      13837323.2
      3064009.81      13836581.7       3063773.5     13836353.54
#Sta/Elev= 30
  3148.6    73.9  3298.6    70.1  3598.6    72.7  3845.5    67.4  4375.5    62.3
  4515.5    63.2  4605.5    67.1  4781.2    66.2  4889.2   54.32  4910.1   46.77
  4953.7   46.35  4955.9   42.88  4979.9   31.79  4999.1   28.19  5031.3   35.41
  5039.7   41.93  5046.8   44.67  5079.1   43.94  5094.6   46.68  5118.8   46.95
  5135.7   50.31  5186.1   47.32  5208.4   51.05    5234   51.85  5310.8   62.52
  5411.9    59.6  5551.9    65.5  6150.9    67.9    6447    73.1  7094.9    74.2
#Mann= 5 ,-1 , 0
  3148.6      .2       0  4889.2     .15       0  4953.7     .05       0
  5039.7     .15       0    5234      .2       0
Bank Sta=4953.7,5039.7
XS Rating Curve= 0
Exp/Cntr=.3,.1

Type RM Length L Ch R = 1 ,205102.2,350.3,374.6,369.1
BEGIN DESCRIPTION:
Cross Section 205102.2 - Interpolated
END DESCRIPTION:
XS GIS Cut Line= 6
      3065708.82     13838698.77      3065715.03     13838214.76
      3065808.11     13837252.94      3066000.47     13836905.44
      3066105.96     13836657.23      3065770.87     13836129.77
#Sta/Elev= 30
  3384.9      73  3676.2    67.3    4139    62.4    4249    65.4    4299    63.3
    4384    64.1    4454    67.6  4499.4    67.5  4699.4    62.1  4850.4    61.7
    4874   57.48  4920.4    45.6  4955.4      45    4959   40.96  4972.5   33.79
    4996   28.65  5009.7   28.33  5021.3   30.41  5042.6   44.53  5090.4    46.3
  5111.5   44.67  5140.4    45.1  5210.4    63.2  5230.4    66.2  5257.6    67.5
  5327.6    66.1  5357.6    67.7  5502.3    68.5  5592.3    66.3  6127.2    72.5
#Mann= 5 ,-1 , 0
  3384.9      .2       0    4874     .12       0    4959     .05       0
  5042.6     .12       0  5111.5     .12       0
Bank Sta=4959,5042.6
XS Rating Curve= 0
Exp/Cntr=.5,.3

Type RM Length L Ch R = 1 ,204727.6,107.6,107.6,107.6
BEGIN DESCRIPTION:
Upstream Section of Bridge/Culvert/Weir
END DESCRIPTION:
XS GIS Cut Line= 6
      3065762.62     13839177.96      3065838.81     13837627.35
      3066222.39     13837213.07      3066674.97     13836438.07
      3066482.14     13835438.19      3066076.74     13834843.34
#Sta/Elev= 30
  2774.7    74.2  2964.7    73.1  3024.7    69.7  3064.7    71.8  3414.7    70.7
  4003.4    62.6  4153.4    65.7  4424.7    66.1  4468.7    68.2  4657.6   67.28
  4793.8   64.33    4874   51.98  4907.5   44.57  4947.2   44.07    4959   40.96
  4972.5   33.79    4996   28.65  5009.7   28.33  5021.3   30.41  5042.6   44.53
  5055.4   44.53  5111.5   56.11  5201.8    64.2  5235.8   63.72  5256.6   66.31
  5737.4    63.5  6663.4    62.9  6703.4    66.2    6966    70.4  7535.4    73.2
#Mann= 5 ,-1 , 0
  2774.7      .2       0    4874     .12       0    4959     .05       0
  5042.6     .12       0  5111.5     .12       0
#XS Ineff= 2 , 0
            4830    63.1    5175            63.1
Permanent Ineff=
       F       F
Bank Sta=4959,5042.6
XS Rating Curve= 0
Exp/Cntr=.5,.3

Type RM Length L Ch R = 3 ,204673.8,,,
BEGIN DESCRIPTION:
SOUTH GESSNER
Structure ID: WOO-68&69
END DESCRIPTION:
Bridge Culvert--1,0,-1,-1, 0
Deck Dist Width WeirC Skew NumUp NumDn MinLoCord MaxHiCord MaxSubmerge Is_Ogee
10,87.6,2.6,0, 60, 60, , , .95, 0, 1,1,,
  2774.7  2964.7  3004.7  3024.7  3034.7  3064.7  3414.7  3564.7  3713.4  4003.4
  4153.4  4193.4  4223.4  4284.7  4394.7  4424.7  4468.7  4558.2  4604.9  4657.6
  4735.4  4793.8 4832.89    4833 4842.61  4842.7    5152  5167.2  5176.2 5176.31
  5201.8    5202  5218.9  5235.8  5236.3  5256.6  5310.3  5369.8  5418.6  5493.2
  5530.3  5698.5  5737.4  5839.6  6021.8  6171.8  6323.4  6373.4  6383.4  6513.4
  6573.4  6613.4  6663.4  6683.4  6703.4    6756    6916    6966    7446  7535.4
    74.2    73.1    71.2    69.7    69.7    71.8    70.7    67.5    65.7    62.6
    65.7      65    63.8    65.5    66.3    66.1   68.21   67.68   67.39   67.29
    66.2   64.96   64.34   66.04   65.89   65.89   65.72   65.71   65.94   64.24
   64.38   64.38   64.32   63.94   64.27   66.32   65.98   66.71   65.62   64.71
   64.53    64.5   64.64      65    64.4      63    63.8    63.8    64.3    63.7
    64.5    63.1    62.9    64.1    66.2    67.3    68.2    70.4    71.5    73.2
    74.2    73.1    71.2    69.7    69.7    71.8    70.7    67.5    65.7    62.6
    65.7      65    63.8    65.5    66.3    66.1    68.2   66.91   67.26   67.28
   66.19   64.33   59.39   59.37   58.16    59.6   59.43   60.11   61.18   61.19
    64.2   63.65   63.98   63.72   64.26   66.31   65.97    66.7   64.94    64.7
   64.52   63.69    63.5   64.13    64.4      63    63.8    63.8    64.3    63.7
    64.5    63.1    62.9    64.1    66.2    67.3    68.2    70.4    71.5    73.2
  2774.7  2964.7  3004.7  3024.7  3034.7  3064.7  3414.7  3564.7  3713.4  4003.4
  4153.4  4193.4  4223.4  4284.7  4394.7  4424.7  4468.7  4558.2  4604.9  4657.6
  4735.4  4793.8 4832.89    4833 4842.61  4842.7    5152  5167.2  5176.2 5176.31
  5201.8    5202  5218.9  5235.8  5236.3  5256.6  5310.3  5369.8  5418.6  5493.2
  5530.3  5698.5  5737.4  5839.6  6021.8  6171.8  6323.4  6373.4  6383.4  6513.4
  6573.4  6613.4  6663.4  6683.4  6703.4    6756    6916    6966    7446  7535.4
    74.2    73.1    71.2    69.7    69.7    71.8    70.7    67.5    65.7    62.6
    65.7      65    63.8    65.5    66.3    66.1   68.21   67.68   67.39   67.29
    66.2   64.96   64.34   66.04   65.89   65.89   65.72   65.71   65.94   64.24
   64.38   64.38   64.32   63.94   64.27   66.32   65.98   66.71   65.62   64.71
   64.53    64.5   64.64      65    64.4      63    63.8    63.8    64.3    63.7
    64.5    63.1    62.9    64.1    66.2    67.3    68.2    70.4    71.5    73.2
   74.01   72.91   71.01   69.51   69.51   71.61   70.51   67.31   65.51   62.41
   65.51   64.81   63.61   65.31   66.11   65.91   68.01   66.72   67.07   67.09
      66   64.14    59.2   59.18   57.97   59.41   59.24   59.92   60.99      61
   64.01   63.46   63.79   63.53   64.07   66.12   65.78   66.51   64.75   64.51
   64.33    63.5   63.31   63.94   64.21   62.81   63.61   63.61   64.11   63.51
   64.31   62.91   62.71   63.91   66.01   67.11   68.01   70.21   71.31   73.01
Pier Skew, UpSta & Num, DnSta & Num=  ,4907.5, 2 ,4907.5, 2 , 0 , 0 , 0 ,,
     2.5     2.5
   43.59   60.56
     2.5     2.5
    43.4   60.37
Pier Skew, UpSta & Num, DnSta & Num=  ,4912.1, 2 ,4912.1, 2 , 0 , 0 , 0 ,,
     2.5     2.5
   43.63   60.56
     2.5     2.5
   43.44   60.37
Pier Skew, UpSta & Num, DnSta & Num=  ,4972.5, 2 ,4972.5, 2 , 0 , 0 , 0 ,,
     2.5     2.5
    32.6   60.53
     2.5     2.5
   32.41   60.34
Pier Skew, UpSta & Num, DnSta & Num=  ,4987.7, 2 ,4987.7, 2 , 0 , 0 , 0 ,,
     2.5     2.5
   29.21   60.52
     2.5     2.5
   29.02   60.33
Pier Skew, UpSta & Num, DnSta & Num=  ,5037.5, 2 ,5037.5, 2 , 0 , 0 , 0 ,,
     2.5     2.5
   39.96   60.49
     2.5     2.5
   39.77    60.3
Pier Skew, UpSta & Num, DnSta & Num=  ,5063.7, 2 ,5063.7, 2 , 0 , 0 , 0 ,,
     2.5     2.5
   46.16   60.48
     2.5     2.5
   45.97   60.29
Pier Skew, UpSta & Num, DnSta & Num=  ,5102.6, 2 ,5102.6, 2 , 0 , 0 , 0 ,,
     2.5     2.5
   53.21   60.46
     2.5     2.5
   53.02   60.27
Abutment Skew #Up #Dn= , 2 , 2
  4842.5  4850.8
    59.6   57.12
  4842.5  4850.8
   59.41   56.93
Abutment Skew #Up #Dn= , 2 , 2
    5152 5167.59
   58.32   60.14
    5152 5167.59
   58.13   59.95
BR Coef= 1 , 1 , 0 ,1.25, 0 ,,,.8,-1,2,0,
WSPro=,,,, 1 ,,,, 0 ,,,, 0 ,,,,-1 ,-1 ,-1 , 0 , 0 , 0 , 0 , 0
BR U #Sta/Elev= 110
  2774.7    74.2  2964.7    73.1  3004.7    71.2  3024.7    69.7  3034.7    69.7
  3064.7    71.8  3414.7    70.7  3564.7    67.5  3713.4    65.7  4003.4    62.6
  4153.4    65.7  4193.4      65  4223.4    63.8  4284.7    65.5  4394.7    66.3
  4424.7    66.1  4428.2   66.27  4468.7    68.2  4551.2   67.05  4557.8   66.96
  4558.2   66.91  4604.9   67.26  4612.3   67.26  4657.6   67.28  4714.1   66.49
  4735.4   66.19  4793.8   64.33 4832.89   59.39    4833   59.37 4833.11   59.36
  4842.5   58.17 4842.61   58.16  4842.7   58.14  4842.8   58.13  4850.7   57.13
  4850.8   57.12    4874   51.98  4907.5   44.57  4912.1   44.65  4926.2   44.65
  4947.2   44.07    4959   40.96  4968.2      37  4972.5   33.79  4974.4    33.5
  4979.7   32.05  4987.7   30.49    4996   28.65  5009.7   28.33  5021.3   30.41
  5025.6   33.76  5037.5   41.81  5042.6   44.53  5055.4   44.53  5063.7   47.63
  5090.2    52.6  5102.6   54.39  5108.1   55.92  5111.5   56.11  5151.9   58.31
    5152   58.32  5167.2   60.11  5167.3   60.13 5167.39   60.14  5167.5   60.15
  5167.6   60.16  5175.9   61.14 5176.09   61.16  5176.2   61.18 5176.31   61.19
  5201.8    64.2    5202   63.65  5213.7   63.84  5214.8   63.86  5218.9   63.98
  5235.8   63.72  5236.3   64.26  5236.8   64.31  5237.8   64.41  5256.6   66.31
  5295.4   66.06  5310.3   65.97  5346.5   66.41  5369.8    66.7  5418.6   64.94
  5418.7   65.05  5420.6   65.04  5493.2    64.7  5530.3   64.52  5698.5   63.69
  5737.4    63.5  5821.8    64.1  5839.6   64.13  6021.8    64.4  6171.8      63
  6193.4    63.2  6323.4    63.8  6373.4    63.8  6383.4    64.3  6513.4    63.7
  6573.4    64.5  6613.4    63.1  6663.4    62.9  6683.4    64.1  6703.4    66.2
    6756    67.3    6916    68.2    6966    70.4    7446    71.5  7535.4    73.2
BR U #Mann= 5
  2774.7      .2    4874     .12    4959     .05  5042.6     .12  5111.5     .12
BR U Banks=4959,5042.6
BR D #Sta/Elev= 110
  2774.7   74.01  2964.7   72.91  3004.7   71.01  3024.7   69.51  3034.7   69.51
  3064.7   71.61  3414.7   70.51  3564.7   67.31  3713.4   65.51  4003.4   62.41
  4153.4   65.51  4193.4   64.81  4223.4   63.61  4284.7   65.31  4394.7   66.11
  4424.7   65.91  4428.2   66.08  4468.7   68.01  4551.2   66.86  4557.8   66.77
  4558.2   66.72  4604.9   67.07  4612.3   67.07  4657.6   67.09  4714.1    66.3
  4735.4      66  4793.8   64.14 4832.89    59.2    4833   59.18 4833.11   59.17
  4842.5   57.98 4842.61   57.97  4842.7   57.95  4842.8   57.94  4850.7   56.94
  4850.8   56.93    4874   51.79  4907.5   44.38  4912.1   44.46  4926.2   44.46
  4947.2   43.88    4959   40.77  4968.2   36.81  4972.5    33.6  4974.4   33.31
  4979.7   31.86  4987.7    30.3    4996   28.46  5009.7   28.14  5021.3   30.22
  5025.6   33.57  5037.5   41.62  5042.6   44.34  5055.4   44.34  5063.7   47.44
  5090.2   52.41  5102.6    54.2  5108.1   55.73  5111.5   55.92  5151.9   58.12
    5152   58.13  5167.2   59.92  5167.3   59.94 5167.39   59.95  5167.5   59.96
  5167.6   59.97  5175.9   60.95 5176.09   60.97  5176.2   60.99 5176.31      61
  5201.8   64.01    5202   63.46  5213.7   63.65  5214.8   63.67  5218.9   63.79
  5235.8   63.53  5236.3   64.07  5236.8   64.12  5237.8   64.22  5256.6   66.12
  5295.4   65.87  5310.3   65.78  5346.5   66.22  5369.8   66.51  5418.6   64.75
  5418.7   64.86  5420.6   64.85  5493.2   64.51  5530.3   64.33  5698.5    63.5
  5737.4   63.31  5821.8   63.91  5839.6   63.94  6021.8   64.21  6171.8   62.81
  6193.4   63.01  6323.4   63.61  6373.4   63.61  6383.4   64.11  6513.4   63.51
  6573.4   64.31  6613.4   62.91  6663.4   62.71  6683.4   63.91  6703.4   66.01
    6756   67.11    6916   68.01    6966   70.21    7446   71.31  7535.4   73.01
BR D #Mann= 5
  2774.7      .2    4874     .12    4959     .05  5042.6     .12  5111.5     .12
BR D Banks=4959,5042.6
BC Design=,, 0 ,, 0 ,,,,,,
BC HTab HWMax=74.2

Type RM Length L Ch R = 1 ,204620.0,961.1,961.1,961.1
BEGIN DESCRIPTION:
Downstream Section of Bridge/Culvert/Weir
END DESCRIPTION:
XS GIS Cut Line= 6
      3065796.64     13839280.04      3065872.83     13837729.43
      3066256.41     13837315.15      3066708.99     13836540.15
      3066516.16     13835540.27      3066110.76     13834945.42
#Sta/Elev= 30
  2774.7   74.02  2964.7   72.92  3024.7   69.52  3064.7   71.62  3414.7   70.52
  4003.4   62.42  4153.4   65.52  4424.7   65.92  4468.7   68.02  4657.6    67.1
  4793.8   64.15    4874    51.8  4907.5   44.39  4947.2   43.89    4959   40.78
  4972.5   33.61    4996   28.47  5009.7   28.15  5021.3   30.23  5042.6   44.35
  5055.4   44.35  5111.5   55.93  5201.8   64.02  5235.8   63.54  5256.6   66.13
  5737.4   63.32  6663.4   62.72  6703.4   66.02    6966   70.22  7535.4   73.02
#Mann= 5 ,-1 , 0
  2774.7      .2       0    4874     .12       0    4959     .05       0
  5042.6     .12       0  5111.5     .12       0
#XS Ineff= 2 , 0
            4830      63    5175              63
Permanent Ineff=
       F       F
Bank Sta=4959,5042.6
XS Rating Curve= 0
Exp/Cntr=.5,.3