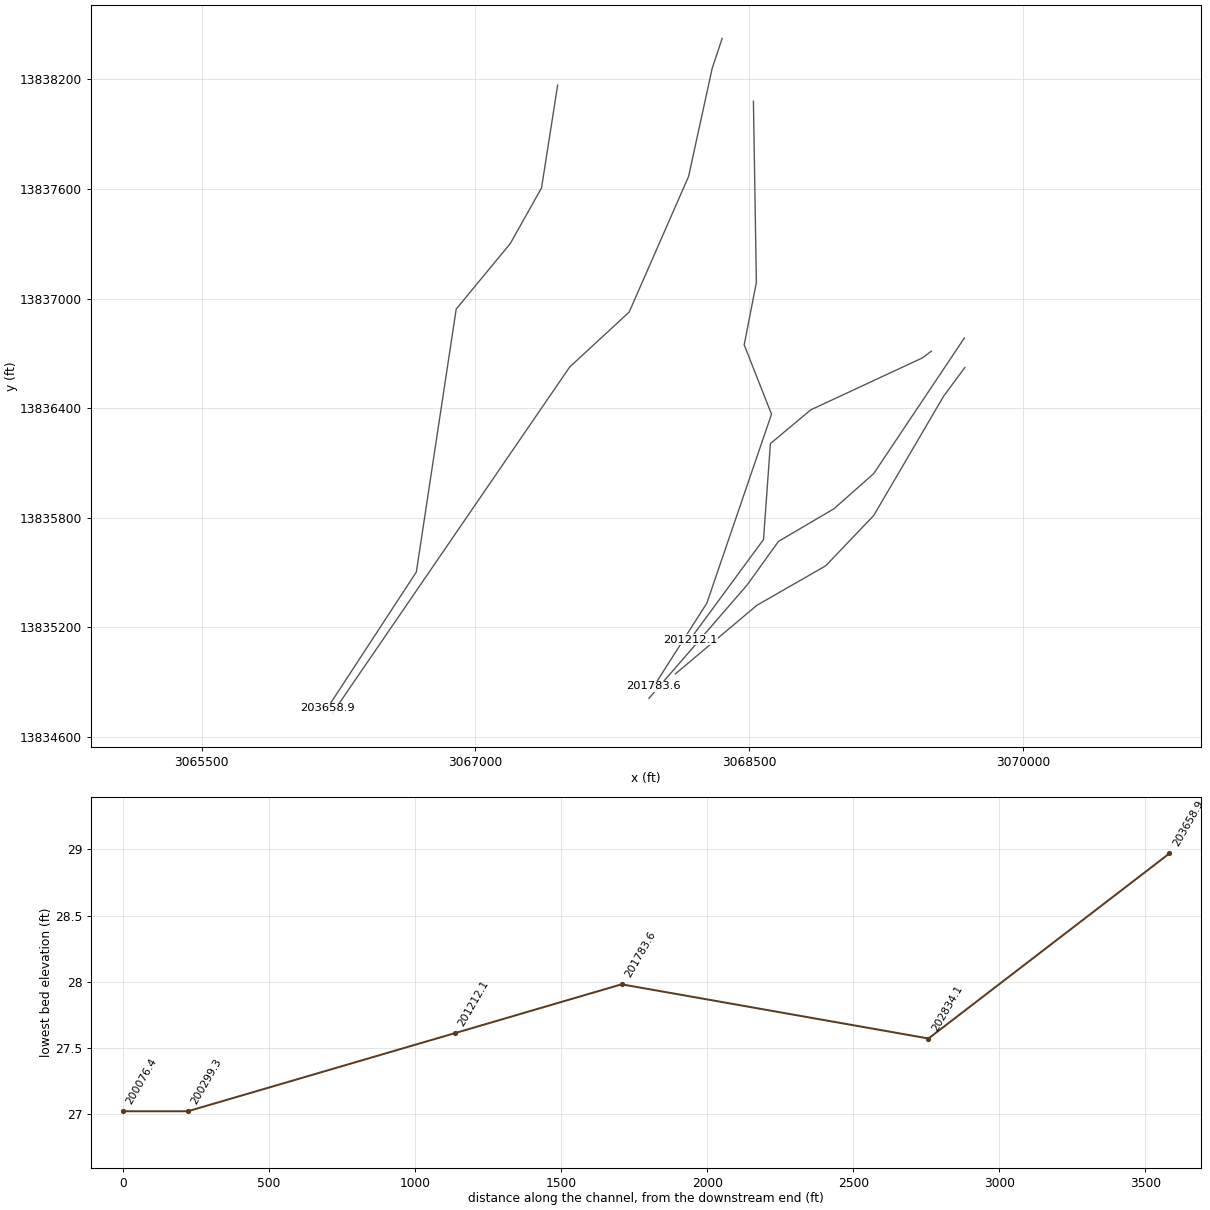
HEC-RAS study W100-00-00.prj: W100-00-00

--- W100-00-00.g01 (geometry) --- (continued)

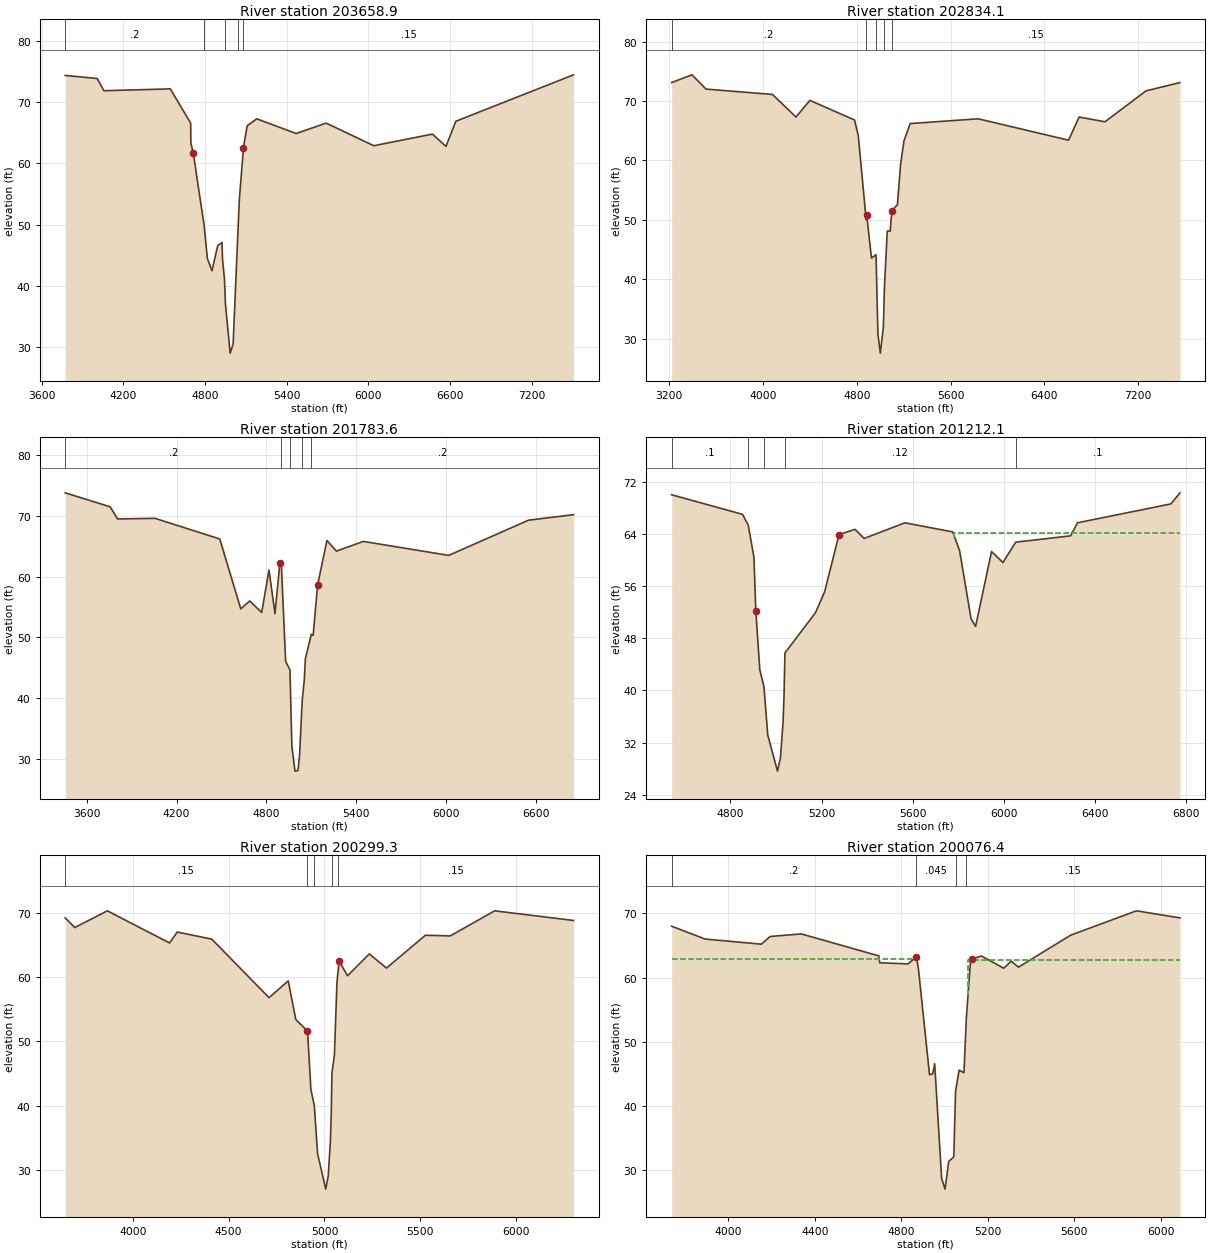
Type RM Length L Ch R = 1 ,203658.9,766.5,824.8,755.8
BEGIN DESCRIPTION:
Cross Section 203658.9
END DESCRIPTION:
XS GIS Cut Line= 6
      3067449.94     13838169.35      3067361.66     13837606.21
      3067190.61     13837301.66       3066894.4     13836942.87
      3066676.12     13835503.12      3066188.92     13834757.55
#Sta/Elev= 30
  3772.7    74.4  4007.3    73.9  4057.3    71.9  4544.8    72.2  4694.1    66.6
  4695.7   63.33  4713.7   61.65  4793.6   49.77  4816.7   44.47  4850.5   42.45
  4893.2   46.58  4924.6   47.07  4928.3   44.31  4942.8      41  4949.3   37.07
  4984.3   28.97  5005.9   30.42  5041.2   48.81  5051.8   54.16  5080.2   62.01
    5082   62.61  5109.1   66.16  5179.4    67.3  5469.4    64.9  5689.4    66.6
  6039.4    62.9  6469.4    64.8  6569.4    62.8  6641.7    66.9  7506.2    74.5
#Mann= 5 ,-1 , 0
  3772.7      .2       0  4793.6     .15       0  4942.8    .055       0
  5041.2     .15       0  5080.2     .15       0
Bank Sta=4713.7,5082
XS Rating Curve= 0
Exp/Cntr=.3,.1

Type RM Length L Ch R = 1 ,202834.1,780.6,1050.5,1212.9
BEGIN DESCRIPTION:
Cross Section 202834.1
END DESCRIPTION:
XS GIS Cut Line= 6
      3068350.91     13838425.37      3068296.19     13838261.21
      3068166.85     13837668.79      3067841.44     13836926.18
      3067516.03      13836625.8        3066216.     13834728.75
#Sta/Elev= 30
  3222.3    73.1  3395.3    74.4  3515.3      72  4081.7    71.1  4281.7    67.3
  4400.8    70.1  4780.8    66.8  4812.6    64.2    4880   50.05  4884.7   50.82
  4925.3   43.57  4964.2   44.12  4980.5   30.75    5001   27.57  5026.9   32.01
  5036.2   38.83    5060   48.12    5085    48.1  5098.8   51.56  5099.3   51.56
  5146.7   52.54  5173.3   59.31  5202.6    63.3  5255.4    66.2  5835.4      67
  6605.4    63.4  6695.4    67.3  6915.4    66.5  7265.4    71.7  7555.2    73.1
#Mann= 5 ,-1 , 0
  3222.3      .2       0    4880     .11       0  4964.2    .055       0
  5036.2     .11       0  5099.3     .15       0
Bank Sta=4884.7,5098.8
XS Rating Curve= 0
Exp/Cntr=.3,.1

Type RM Length L Ch R = 1 ,201783.6,795.2,571.5,341.2
BEGIN DESCRIPTION:
Cross Section 201783.6
END DESCRIPTION:
XS GIS Cut Line= 6
      3068521.96     13838080.97      3068538.16     13837088.89
      3068471.41     13836746.78      3068621.03     13836367.11
      3068266.98     13835332.48      3067976.63     13834877.16
#Sta/Elev= 30
  3456.2    73.8  3756.2    71.5  3806.2    69.5  4056.2    69.6  4488.4    66.2
  4628.4    54.7  4688.4      56  4768.4    54.1    4817    61.1    4857    53.9
  4889.4   62.21  4899.6   61.94  4928.2   46.04  4957.1   44.65  4969.7   32.09
  4990.7   27.98  5010.8   28.09  5020.8   30.44  5039.2   39.75  5053.2    43.1
  5059.8   46.46  5099.6   50.51  5111.9   50.33  5141.6    58.6  5203.9   65.95
  5267.2    64.2  5447.2    65.8  6017.2    63.5  6550.7    69.3  6850.7    70.2
#Mann= 5 ,-1 , 0
  3456.2      .2       0  4899.6      .1       0  4957.1    .055       0
  5039.2      .1       0  5099.6      .2       0
Bank Sta=4889.4,5141.6
XS Rating Curve= 0
Exp/Cntr=.3,.1

Type RM Length L Ch R = 1 ,201212.1,581.2,912.8,742.4
BEGIN DESCRIPTION:
Cross Section 201212.1-Interpolated
END DESCRIPTION:
XS GIS Cut Line= 6
      3069496.02     13836712.14      3069447.47     13836675.43
      3068836.82     13836391.27      3068614.93      13836206.1
      3068577.25     13835680.68      3068174.34     13835132.86
#Sta/Elev= 30
  4542.3      70  4853.2      67  4878.3   65.34  4903.2    60.4  4911.4   52.23
    4929   43.15  4947.1   40.56  4963.8   33.17  5006.6   27.61  5019.7   29.68
  5030.8   34.97  5035.1   38.95  5039.3   45.74  5173.2    51.9  5213.2    55.1
  5276.7    63.9  5346.7    64.7  5386.7    63.3  5565.7    65.7  5775.7    64.3
  5805.7    61.4  5855.7      51  5875.7    49.8  5945.7    61.3  5995.7    59.6
  6051.7   62.73  6292.5    63.7  6322.5    65.7  6732.5    68.6  6772.5    70.3
#Mann= 5 ,-1 , 0
  4542.3      .1       0  4878.3     .12       0  4947.1     .05       0
  5039.3     .12       0  6051.7      .1       0
#XS Ineff= 2 , 0
                            5783            64.2
Permanent Ineff=
       F       F
Bank Sta=4911.4,5276.7
XS Rating Curve= 0
Exp/Cntr=.3,.1

Type RM Length L Ch R = 1 ,200299.3,166.8,222.9,221.4
BEGIN DESCRIPTION:
Cross Section 200299.3
END DESCRIPTION:
XS GIS Cut Line= 6
      3069677.11     13836784.33      3069180.64     13836041.72
       3068963.7     13835849.81      3068659.15     13835670.42
       3068488.1     13835432.61      3067949.91     13834810.99
#Sta/Elev= 30
  3646.7    69.2  3696.7    67.7  3866.7    70.3  4191.5    65.3  4231.5      67
  4411.5    65.9  4710.8    56.8  4810.8    59.4  4850.4    53.4  4910.1   51.64
  4911.4   51.64    4929   42.56  4947.1   39.97  4963.8   32.58  5006.6   27.02
  5019.7   29.09  5030.8   34.38  5035.1   38.36  5039.3   45.15    5052   47.88
  5065.2   59.16  5071.9   61.14  5076.4   62.47  5120.4    60.2  5233.9    63.6
  5323.9    61.4  5526.8    66.5  5656.8    66.4  5888.6    70.3  6300.1    68.8
#Mann= 5 ,-1 , 0
  3646.7     .15       0  4910.1     .12       0  4947.1     .05       0
  5039.3     .12       0  5071.9     .15       0
Bank Sta=4911.4,5076.4
XS Rating Curve= 0
Exp/Cntr=.5,.3

Type RM Length L Ch R = 1 ,200076.4,111.8,111.8,111.8
BEGIN DESCRIPTION:
Upstream Section of Bridge/Culvert/Weir
END DESCRIPTION:
XS GIS Cut Line= 6
      3069680.08     13836622.92      3069564.48     13836467.12
      3069180.66     13835812.12      3068917.82     13835536.77
      3068540.68     13835320.39      3068095.36      13834945.5
#Sta/Elev= 30
  3737.5      68  3892.5      66  4152.5    65.2  4192.5    66.4  4336.9    66.8
  4695.2   63.38  4699.9    62.3    4830   62.13  4869.5    63.2  4878.4   61.48
    4930   44.85  4944.7   44.99  4953.8   46.58    4986   28.69  5001.8   27.02
  5018.8   31.33  5042.2   32.04  5050.5   42.31  5066.8   45.56  5089.3   45.17
  5100.1   53.56  5119.1   62.32  5124.9   62.88    5170   63.36  5273.3   61.46
  5307.8   62.55  5341.3   61.62  5582.5    66.6  5886.9    70.4  6088.4    69.3
#Mann= 4 ,-1 , 0
  3737.5      .2       0  4869.5    .045       0  5050.5     .12       0
  5100.1     .15       0
#XS Ineff= 2 , 0
            4872    62.9    5108            62.8
Permanent Ineff=
       F       F
Bank Sta=4869.5,5124.9
XS Rating Curve= 0
Exp/Cntr=.5,.3