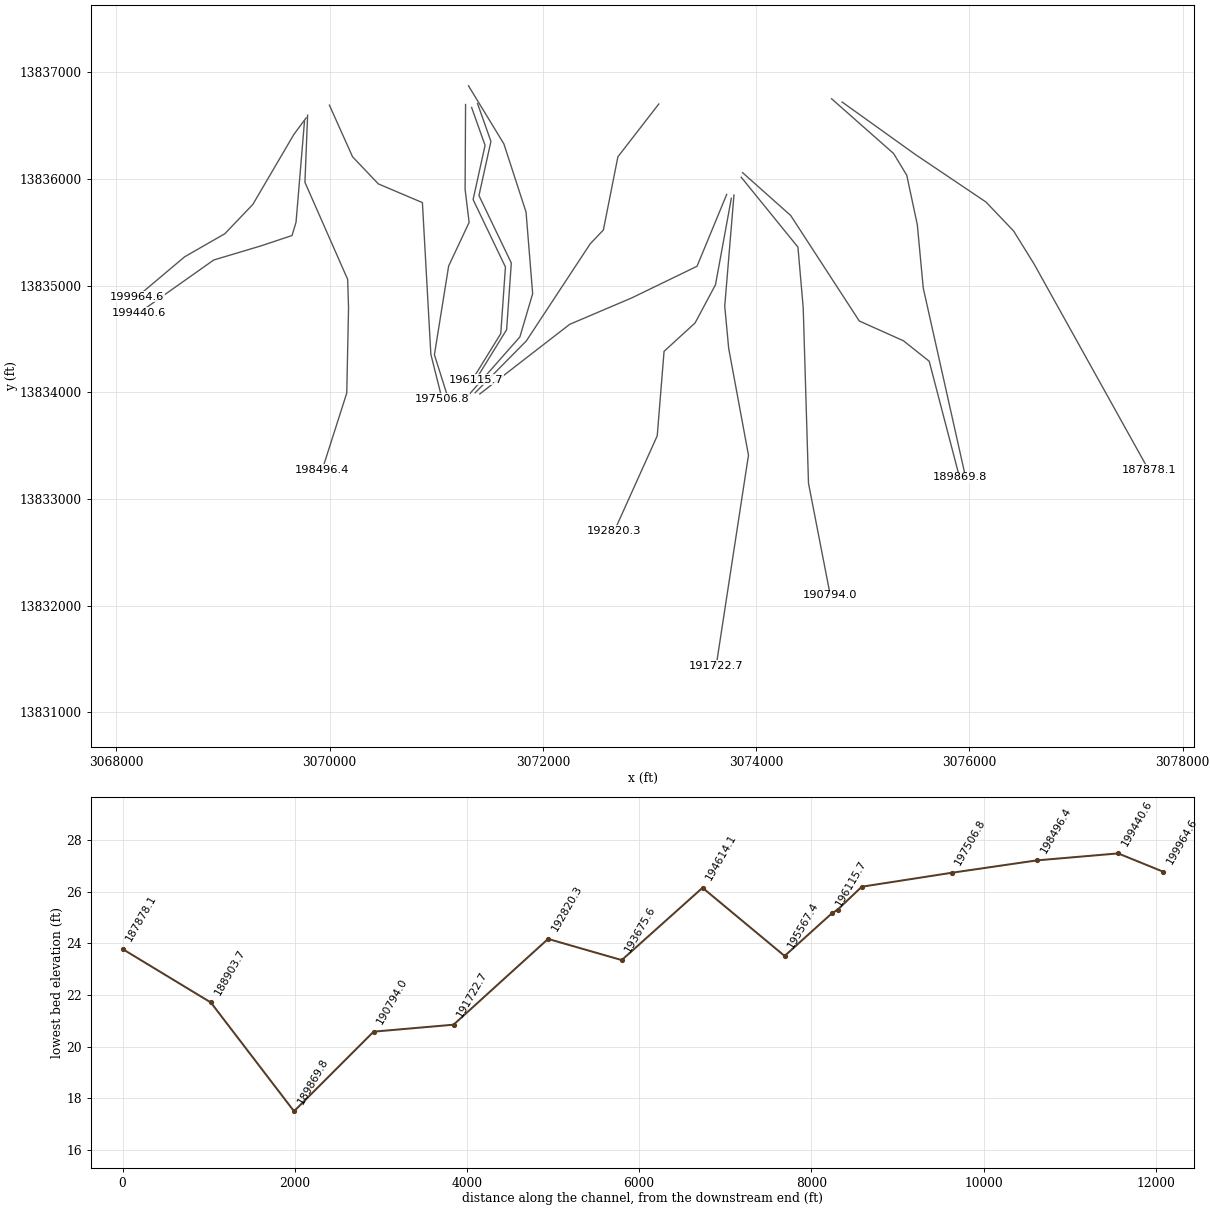
HEC-RAS study W100-00-00.prj: W100-00-00

--- W100-00-00.g01 (geometry) --- (continued)

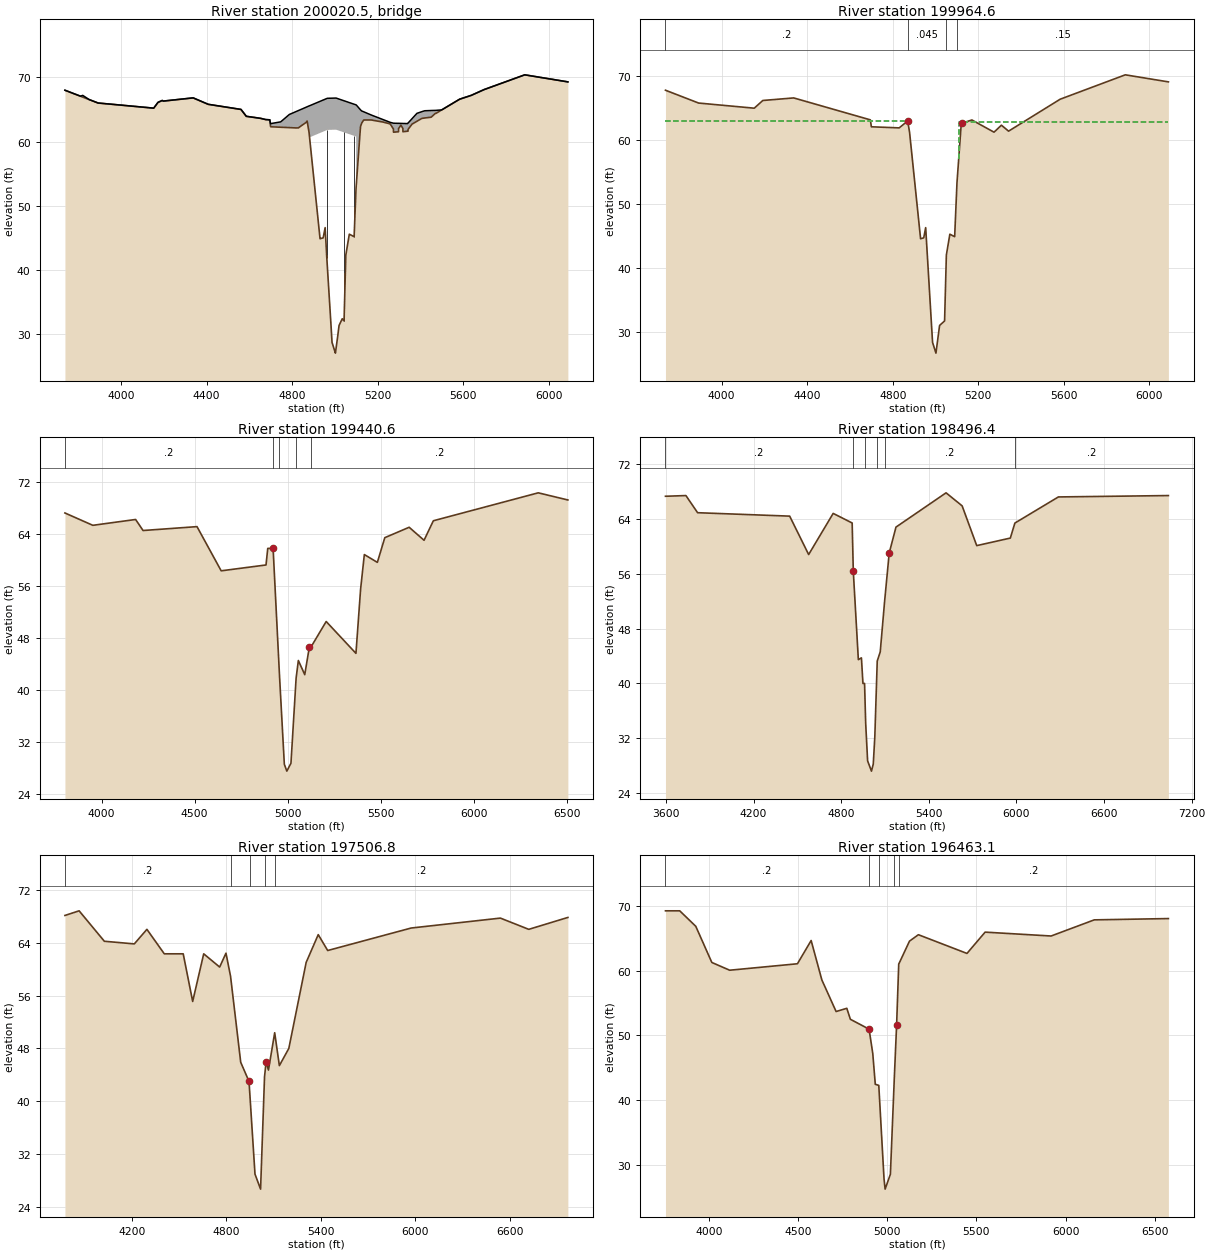
Type RM Length L Ch R = 3 ,200020.5,,,
BEGIN DESCRIPTION:
BRIAR FOREST DRIVE
Structure ID: WOO-66&67
END DESCRIPTION:
Bridge Culvert--1,0,-1,-1, 0
Deck Dist Width WeirC Skew NumUp NumDn MinLoCord MaxHiCord MaxSubmerge Is_Ogee
10,91.8,2.6,0, 58, 58, , , .95, 0, 1,1,,
  3737.5  3810.5  3820.5  3850.5  3892.5  4152.5  4172.5  4192.5  4196.9  4336.9
  4406.9  4560.4  4584.9  4652.3  4675.8  4695.2  4695.8  4698.5  4699.9    4746
 4786.29    4830  4868.9  4869.5  4878.4 4881.61  4881.7  4963.6  5004.9 5098.89
  5099.1  5119.1  5124.9  5134.7    5170  5257.4    5273  5273.3  5296.8  5296.9
  5307.8  5317.3  5317.5  5338.9  5341.3  5341.5  5360.4  5382.9    5406  5419.1
  5449.6  5469.6  5498.3  5582.5  5636.9  5696.9  5886.9  6088.4
      68   67.07    67.2   66.55   66.01   65.21   66.11   66.41   66.31   66.81
   65.81   65.01   63.94   63.62   63.43   63.39   63.21    62.8    62.8   63.07
   64.22   64.85   65.41   65.42   65.55   65.59   65.59   66.74   66.78   65.71
   65.71   64.94   64.76   64.63   64.13      63   62.86   62.86   62.84   62.84
   62.83   62.82   62.82    62.8   62.89   62.89   63.58    64.4   64.66    64.8
   64.84   64.86   64.93    66.6    67.2    68.1    70.4    69.3
      68   67.06   66.93   66.54      66    65.2    66.1    66.4    66.3    66.8
    65.8      65   63.93   63.61   63.42   63.38    63.2   62.39    62.3   62.23
   62.17   62.13   63.08    63.2   61.48   60.45   60.66   61.81   61.85   60.78
    53.1   62.32   62.88   63.36   63.36   62.76   61.95   61.46   61.52      62
   62.55   62.04   61.53   61.61   61.62    61.9   62.72   63.16   63.61   63.67
    63.8    64.4   64.92    66.6    67.2    68.1    70.4    69.3
  3737.5  3810.5  3820.5  3850.5  3892.5  4152.5  4172.5  4192.5  4196.9  4336.9
  4406.9  4560.4  4584.9  4652.3  4675.8  4695.2  4695.8  4698.5  4699.9    4746
 4786.29    4830  4868.9  4869.5  4878.4 4881.61  4881.7  4963.6  5004.9 5098.89
  5099.1  5119.1  5124.9  5134.7    5170  5257.4    5273  5273.3  5296.8  5296.9
  5307.8  5317.3  5317.5  5338.9  5341.3  5341.5  5360.4  5382.9    5406  5419.1
  5449.6  5469.6  5498.3  5582.5  5636.9  5696.9  5886.9  6088.4
      68   67.07    67.2   66.55   66.01   65.21   66.11   66.41   66.31   66.81
   65.81   65.01   63.94   63.62   63.43   63.39   63.21    62.8    62.8   63.07
   64.22   64.85   65.41   65.42   65.55   65.59   65.59   66.74   66.78   65.71
   65.71   64.94   64.76   64.63   64.13      63   62.86   62.86   62.84   62.84
   62.83   62.82   62.82    62.8   62.89   62.89   63.58    64.4   64.66    64.8
   64.84   64.86   64.93    66.6    67.2    68.1    70.4    69.3
   67.74    66.8   66.67   66.28   65.74   64.94   65.84   66.14   66.04   66.54
   65.54   64.74   63.67   63.35   63.16   63.12   62.94   62.13   62.04   61.97
   61.91   61.87   62.82   62.94   61.22   60.19    60.4   61.55   61.59   60.52
   52.84   62.06   62.62    63.1    63.1    62.5   61.69    61.2   61.26   61.74
   62.29   61.78   61.27   61.35   61.36   61.64   62.46    62.9   63.35   63.41
   63.54   64.14   64.66   66.34   66.94   67.84   70.14   69.04
Pier Skew, UpSta & Num, DnSta & Num=  ,4961.5, 2 ,4961.5, 2 , 0 , 0 , 0 ,,
     2.5     2.5
   40.25    62.8
     2.5     2.5
   39.99   62.54
Pier Skew, UpSta & Num, DnSta & Num=  ,5042.2, 2 ,5042.2, 2 , 0 , 0 , 0 ,,
     2.5     2.5
   31.09   62.44
     2.5     2.5
   30.83   62.18
Pier Skew, UpSta & Num, DnSta & Num=  ,5089.3, 2 ,5089.3, 2 , 0 , 0 , 0 ,,
     1.4     1.4
   44.18    61.9
     1.4     1.4
   43.92   61.64
Abutment Skew #Up #Dn= , 2 , 2
  4881.5  4930.1
   60.66   44.85
  4881.5  4930.1
    60.4   44.59
BR Coef= 1 , 1 , 0 ,1.25, 0 ,,,.8,0,2,0,
WSPro=,,,, 1 ,,,, 0 ,,,, 0 ,,,,-1 ,-1 ,-1 , 0 , 0 , 0 , 0 , 0
BR U #Sta/Elev= 106
  3737.5      68  3770.5   67.57  3810.5   67.06  3820.5   66.93  3850.5   66.54
  3892.5      66  3931.5   65.88  3981.5   65.73  4071.5   65.45  4152.5    65.2
  4172.5    66.1  4192.5    66.4  4196.9    66.3  4214.2   66.36  4294.2   66.65
  4336.9    66.8  4406.9    65.8  4560.4      65  4571.3   64.54  4583.9      64
  4584.8   63.96  4584.9   63.93  4640.2   63.67  4652.3   63.61  4675.8   63.42
    4679   63.41  4695.2   63.38  4695.8    63.2  4698.5   62.39  4699.9    62.3
    4746   62.23 4786.29   62.17  4786.4   62.17 4786.51   62.17  4817.7   62.12
    4830   62.13  4831.2   62.19    4860   62.87  4868.9   63.08  4869.5    63.2
  4878.4   61.48 4881.61   60.45  4881.7   60.42    4930   44.85  4930.1   44.85
  4944.7   44.99  4953.8   46.58  4961.5   41.92  4963.6    40.8  4981.2   31.37
    4986   28.69  4999.8   27.23  5001.8   27.02  5004.9   27.78  5012.1   29.53
  5018.8   31.33  5033.8   32.38  5042.2   32.04  5050.5   42.31  5066.8   45.56
  5089.3   45.17    5098   52.56  5098.1   52.64 5098.89      53  5099.1    53.1
  5099.2   53.15  5099.3   53.19  5100.1   53.56  5119.1   62.32  5122.9   62.69
  5124.9   62.88  5133.5   63.33  5134.7   63.36    5170   63.36  5198.1   63.19
  5220.8   63.06 5255.69   62.77  5255.8   62.77 5255.91   62.77  5257.4   62.76
  5267.8   62.22    5273   61.95  5273.3   61.46  5296.8   61.52  5296.9      62
  5307.8   62.55  5317.3   62.04  5317.5   61.53  5338.9   61.61  5341.3   61.62
  5341.5    61.9  5360.4   62.72  5382.9   63.16    5406   63.61  5406.2   63.61
  5419.1   63.67  5449.6    63.8  5469.6    64.4  5472.3    64.4  5498.3   64.92
  5551.7   65.99  5582.5    66.6  5636.9    67.2  5696.9    68.1  5886.9    70.4
  6088.4    69.3
BR U #Mann= 4
  3737.5      .2  4869.5    .045  5050.5     .12  5100.1     .15
BR U Banks=4869.5,5124.9
BR D #Sta/Elev= 106
  3737.5   67.74  3770.5   67.31  3810.5    66.8  3820.5   66.67  3850.5   66.28
  3892.5   65.74  3931.5   65.62  3981.5   65.47  4071.5   65.19  4152.5   64.94
  4172.5   65.84  4192.5   66.14  4196.9   66.04  4214.2    66.1  4294.2   66.39
  4336.9   66.54  4406.9   65.54  4560.4   64.74  4571.3   64.28  4583.9   63.74
  4584.8    63.7  4584.9   63.67  4640.2   63.41  4652.3   63.35  4675.8   63.16
    4679   63.15  4695.2   63.12  4695.8   62.94  4698.5   62.13  4699.9   62.04
    4746   61.97 4786.29   61.91  4786.4   61.91 4786.51   61.91  4817.7   61.86
    4830   61.87  4831.2   61.93    4860   62.61  4868.9   62.82  4869.5   62.94
  4878.4   61.22 4881.61   60.19  4881.7   60.16    4930   44.59  4930.1   44.59
  4944.7   44.73  4953.8   46.32  4961.5   41.66  4963.6   40.54  4981.2   31.11
    4986   28.43  4999.8   26.97  5001.8   26.76  5004.9   27.52  5012.1   29.27
  5018.8   31.07  5033.8   32.12  5042.2   31.78  5050.5   42.05  5066.8    45.3
  5089.3   44.91    5098    52.3  5098.1   52.38 5098.89   52.74  5099.1   52.84
  5099.2   52.89  5099.3   52.93  5100.1    53.3  5119.1   62.06  5122.9   62.43
  5124.9   62.62  5133.5   63.07  5134.7    63.1    5170    63.1  5198.1   62.93
  5220.8    62.8 5255.69   62.51  5255.8   62.51 5255.91   62.51  5257.4    62.5
  5267.8   61.96    5273   61.69  5273.3    61.2  5296.8   61.26  5296.9   61.74
  5307.8   62.29  5317.3   61.78  5317.5   61.27  5338.9   61.35  5341.3   61.36
  5341.5   61.64  5360.4   62.46  5382.9    62.9    5406   63.35  5406.2   63.35
  5419.1   63.41  5449.6   63.54  5469.6   64.14  5472.3   64.14  5498.3   64.66
  5551.7   65.73  5582.5   66.34  5636.9   66.94  5696.9   67.84  5886.9   70.14
  6088.4   69.04
BR D #Mann= 4
  3737.5      .2  4869.5    .045  5050.5     .12  5100.1     .15
BR D Banks=4869.5,5124.9
BC Design=,, 0 ,, 0 ,,,,,,
BC HTab HWMax=70.4

Type RM Length L Ch R = 1 ,199964.6,524,524,524
BEGIN DESCRIPTION:
Downstream Section of Bridge/Culvert/Weir
END DESCRIPTION:
XS GIS Cut Line= 6
      3069780.18     13836573.14      3069664.58     13836417.34
      3069280.76     13835762.34      3069017.92     13835486.99
      3068640.78     13835270.61      3068195.46     13834895.72
#Sta/Elev= 30
  3737.5   67.75  3892.5   65.75  4152.5   64.95  4192.5   66.15  4336.9   66.55
  4695.2   63.13  4699.9   62.05    4830   61.88  4869.5   62.95  4878.4   61.23
    4930    44.6  4944.7   44.74  4953.8   46.33    4986   28.44  5001.8   26.77
  5018.8   31.08  5042.2   31.79  5050.5   42.06  5066.8   45.31  5089.3   44.92
  5100.1   53.31  5119.1   62.07  5124.9   62.63    5170   63.11  5273.3   61.21
  5307.8    62.3  5341.3   61.37  5582.5   66.35  5886.9   70.15  6088.4   69.05
#Mann= 4 ,-1 , 0
  3737.5      .2       0  4869.5    .045       0  5050.5     .12       0
  5100.1     .15       0
#XS Ineff= 2 , 0
            4872    62.9    5108            62.8
Permanent Ineff=
       F       F
Bank Sta=4869.5,5124.9
XS Rating Curve= 0
Exp/Cntr=.5,.3

Type RM Length L Ch R = 1 ,199440.6,484.9,944.2,1164.2
BEGIN DESCRIPTION:
Cross Section 199440.6
END DESCRIPTION:
XS GIS Cut Line= 6
      3069764.72     13836542.36      3069685.45     13835595.32
      3069647.91     13835470.16      3069360.04      13835374.2
      3068913.64      13835240.7      3068216.92     13834748.41
#Sta/Elev= 30
  3802.7    67.2  3952.7    65.3  4182.7    66.2  4222.7    64.5  4512.7    65.1
  4642.7    58.3  4883.7    59.2  4893.1   61.75  4920.3   61.75  4921.7   61.82
  4956.1   42.25  4982.2   28.54  4995.6   27.48  5017.8   28.69  5045.5   41.78
  5057.6    44.5    5092   42.32  5116.9   46.61    5123   46.46  5207.2    50.5
  5367.2    45.6  5392.3    55.5  5412.3    60.8  5482.3    59.6  5522.3    63.4
  5653.3      65  5733.3      63  5783.3      66  6347.2    70.3  6506.5    69.2
#Mann= 5 ,-1 , 0
  3802.7      .2       0  4920.3     .12       0  4956.1    .055       0
  5045.5     .12       0    5123      .2       0
Bank Sta=4921.7,5116.9
XS Rating Curve= 0
Exp/Cntr=.3,.1

Type RM Length L Ch R = 1 ,198496.4,865.7,989.6,938.3
BEGIN DESCRIPTION:
Cross Section 198496.4
END DESCRIPTION:
XS GIS Cut Line= 6
      3069793.93     13836598.68      3069768.89     13835968.71
       3070169.4     13835059.22      3070177.75     13834792.21
      3070161.06     13833993.28       3069931.6      13833275.7
#Sta/Elev= 30
  3596.4    67.3  3736.4    67.4  3816.4    64.9  4446.9    64.4  4576.9    58.8
  4744.8    64.8  4874.8    63.4  4879.6   59.06  4882.6   56.34  4917.2   43.47
  4938.2   43.73  4948.7   39.99  4959.7      40  4967.4   34.19  4980.6   28.71
    5007   27.21  5019.3   28.24    5030   32.24  5046.5   43.27    5067    44.6
  5097.2   52.03  5128.5   59.02  5174.8    62.8  5517.8    67.8  5627.8    65.9
  5727.8    60.1  5957.8    61.2  5989.1   63.39  6286.9    67.2  7040.3    67.4
#Mann= 6 ,-1 , 0
  3596.4      .2       0  4879.6      .1       0  4959.7    .055       0
  5046.5      .1       0  5097.2      .2       0  5989.1      .2       0
Bank Sta=4882.6,5128.5
XS Rating Curve= 0
Exp/Cntr=.3,.1

Type RM Length L Ch R = 1 ,197506.8,1041.6,1043.7,353.8
BEGIN DESCRIPTION:
Cross Section 197506.8
END DESCRIPTION:
XS GIS Cut Line= 6
      3069998.35     13836692.55      3070215.29      13836208.6
      3070457.27     13835954.11       3070870.3     13835778.89
      3070949.56     13834356.24      3071053.86     13833941.13
#Sta/Elev= 30
  3776.7    68.1  3866.7    68.8  4026.7    64.2  4216.7    63.8  4296.7      66
    4407    62.3    4527    62.3    4587    55.1    4657    62.3  4758.2    60.3
  4798.2    62.4  4827.2   58.92  4891.8    45.9  4944.4   43.01  4950.2   40.88
  4982.3      29  5017.7   26.73  5042.8   43.71  5052.7   45.95  5067.8   44.73
  5107.3   50.37  5136.9    45.4  5196.9      48  5306.9      61  5383.5    65.2
  5443.5    62.8  5972.9    66.2    6539    67.7    6719      66    6967    67.8
#Mann= 5 ,-1 , 0
  3776.7      .2       0  4827.2     .15       0  4950.2    .055       0
  5042.8     .15       0  5107.3      .2       0
Bank Sta=4944.4,5052.7
XS Rating Curve= 0
Exp/Cntr=.3,.1

Type RM Length L Ch R = 1 ,196463.1,90.3,280.8,364
BEGIN DESCRIPTION:
Cross Section 196463.1
END DESCRIPTION:
XS GIS Cut Line= 6
      3071274.98     13836698.81       3071270.8     13835901.96
      3071308.35     13835593.23      3071116.44     13835184.38
      3070982.94     13834352.07       3071108.1     13833955.73
#Sta/Elev= 30
  3756.6    69.3  3836.6    69.3  3926.6    66.9  4016.6    61.3  4116.6    60.1
  4496.6    61.1  4573.5    64.7  4633.5    58.6  4713.5    53.7  4773.5    54.2
  4793.5    52.5  4896.4      51  4898.1   51.02    4919   47.22  4933.2   42.43
  4952.8   42.26  4982.2    27.8  4988.3   26.19  5017.9    28.5  5040.4   43.74
  5052.8   51.63  5064.7   61.07    5067   61.18  5124.9    64.6  5174.9    65.6
  5447.3    62.7  5549.1      66  5919.1    65.4  6161.2    67.9  6576.9    68.1
#Mann= 5 ,-1 , 0
  3756.6      .2       0  4896.4     .12       0  4952.8     .05       0
  5040.4     .12       0    5067      .2       0
Bank Sta=4898.1,5052.8
XS Rating Curve= 0
Exp/Cntr=.5,.3

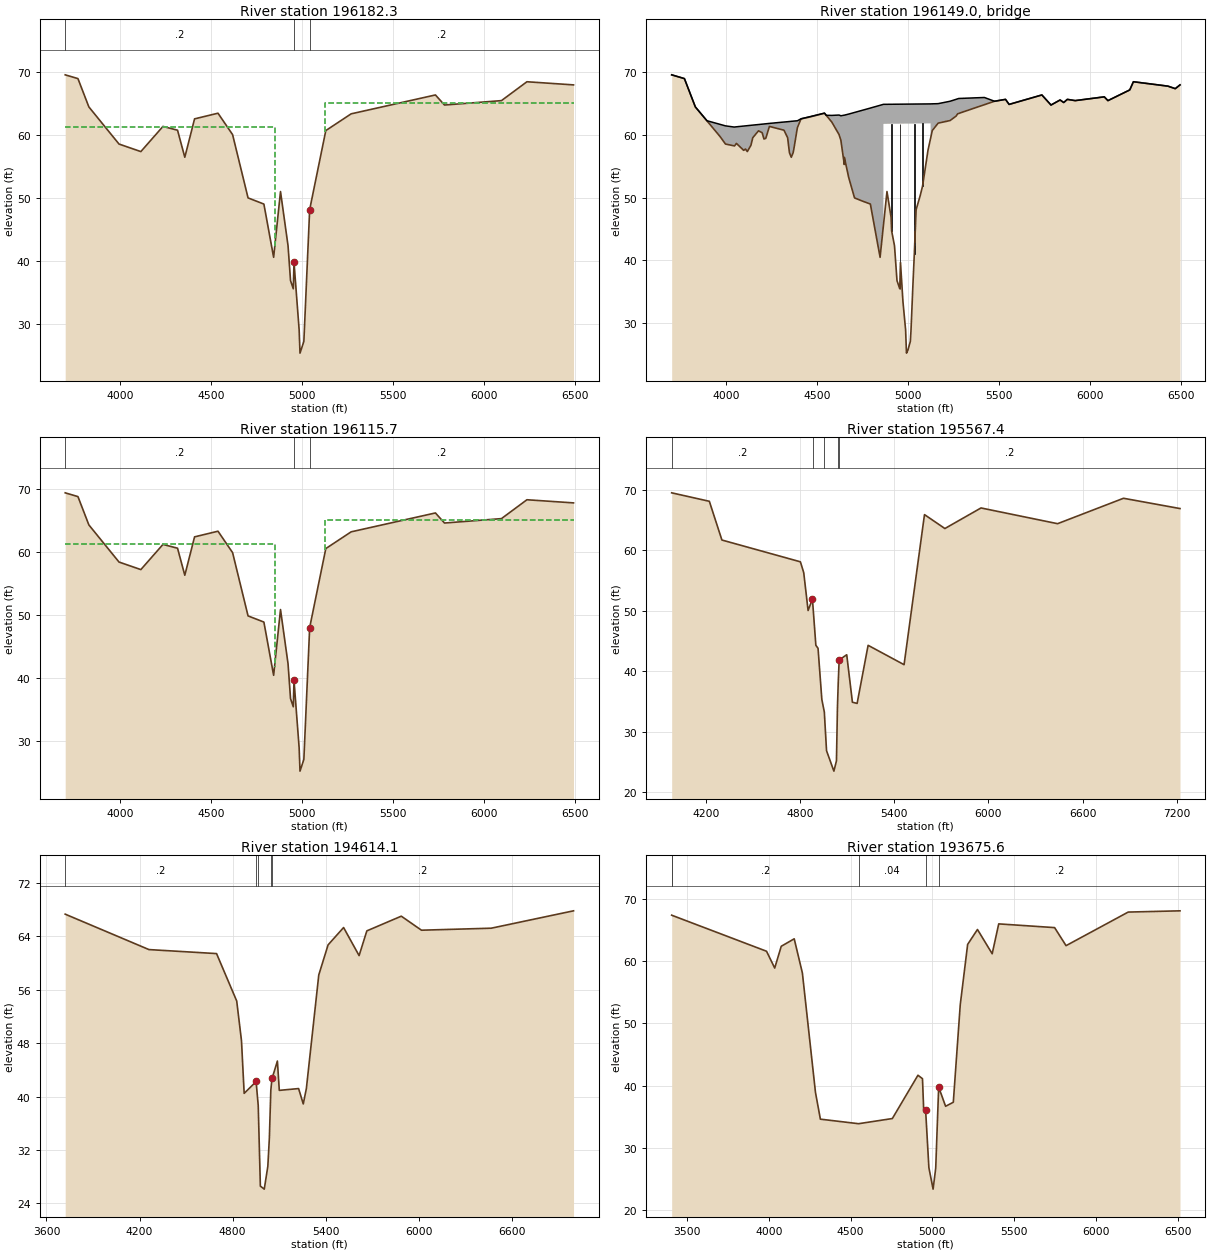
Type RM Length L Ch R = 1 ,196182.3,66.6,66.6,66.6
BEGIN DESCRIPTION:
Upstream Section of Bridge/Culvert/Weir
END DESCRIPTION:
XS GIS Cut Line= 6
      3071331.77     13836671.09      3071457.79     13836315.45
      3071345.56     13835807.31      3071648.88     13835175.04
      3071605.04     13834549.99      3071314.64     13834079.38
#Sta/Elev= 30
    3700   69.53    3770   68.93    3830   64.43  3995.6   58.53  4115.6   57.33
  4237.1   61.33  4317.1   60.73  4357.1   56.43  4410.7   62.53  4539.4   63.43
  4619.6   60.03  4704.6   49.97  4791.6   48.99  4845.1   40.53  4882.9   50.98
  4924.3   42.36    4938   36.82  4953.1   35.53    4957   39.74  4985.3   28.99
    4990    25.3  5011.2   27.16  5043.1   48.11  5131.8   60.67    5271   63.33
    5734   66.33    5784   64.73  6096.8   65.43  6236.8   68.43  6492.8   67.93
#Mann= 3 ,-1 , 0
    3700      .2       0    4957     .06       0  5043.1      .2       0
#XS Ineff= 2 , 0
            4850    61.2    5130              65
Permanent Ineff=
       F       F
Bank Sta=4957,5043.1
XS Rating Curve= 0
Exp/Cntr=.5,.3

Type RM Length L Ch R = 3 ,196149.0,,,
BEGIN DESCRIPTION:
PINEY POINT ROAD
Structure ID: WOO-65
END DESCRIPTION:
Bridge Culvert--1,0,-1,-1, 0
Deck Dist Width WeirC Skew NumUp NumDn MinLoCord MaxHiCord MaxSubmerge Is_Ogee
10,46.6,2.6,0, 60, 60, , , .95, 0, 1,1,,
    3700    3770    3830  3893.5  3995.6  4043.5  4055.6  4095.6  4105.6  4115.6
  4135.6  4145.6  4177.1  4197.1  4207.1  4217.1  4237.1  4317.1  4337.1  4347.1
  4357.1  4370.7  4390.7  4410.7  4539.4  4549.2  4579.6  4619.6  4629.6  4648.3
  4648.6  4672.2  4704.6  4791.6  4845.1 4863.21  4863.3 5122.59  5122.7  5131.8
  5164.1  5229.4  5277.1  5417.9    5474    5534    5554    5734    5784    5834
    5854    5874  5916.8  6076.8  6096.8  6216.8  6236.8  6426.8  6466.8  6492.8
    69.5    68.9    64.4   62.21   61.39    61.2   61.24   61.36   61.39   61.42
   61.48   61.51    61.6   61.66   61.69   61.72   61.78      62   62.05   62.08
   62.11   62.15    62.2   62.51   63.41   63.07   63.05   63.11   62.99   63.09
   63.09   63.26   63.52   64.22   64.66   64.81   64.81   64.88   64.88   64.89
   64.92    65.3   65.74    65.9    65.3    65.6    64.8    66.3    64.7    65.5
    65.1    65.6    65.4      66    65.4    67.1    68.4    67.7    67.3    67.9
    69.5    68.9    64.4    62.2    58.5   58.21    58.6    57.5    57.7    57.3
    58.3    59.5    60.6    60.3    59.3    59.4    61.3    60.7    59.5    57.1
    56.4    57.6    61.1    62.5    63.4   63.06      62      60    59.1   55.25
   56.39   53.23   49.94   48.96    40.5   45.51   61.71   61.78   59.43   60.64
   61.82   62.23   63.36   64.75    65.3    65.6    64.8    66.3    64.7    65.5
    65.1    65.6    65.4      66    65.4    67.1    68.4    67.7    67.3    67.9
    3700    3770    3830  3893.5  3995.6  4043.5  4055.6  4095.6  4105.6  4115.6
  4135.6  4145.6  4177.1  4197.1  4207.1  4217.1  4237.1  4317.1  4337.1  4347.1
  4357.1  4370.7  4390.7  4410.7  4539.4  4549.2  4579.6  4619.6  4629.6  4648.3
  4648.6  4672.2  4704.6  4791.6  4845.1 4863.21  4863.3 5122.59  5122.7  5131.8
  5164.1  5229.4  5277.1  5417.9    5474    5534    5554    5734    5784    5834
    5854    5874  5916.8  6076.8  6096.8  6216.8  6236.8  6426.8  6466.8  6492.8
    69.5    68.9    64.4   62.21   61.39    61.2   61.24   61.36   61.39   61.42
   61.48   61.51    61.6   61.66   61.69   61.72   61.78      62   62.05   62.08
   62.11   62.15    62.2   62.51   63.41   63.07   63.05   63.11   62.99   63.09
   63.09   63.26   63.52   64.22   64.66   64.81   64.81   64.88   64.88   64.89
   64.92    65.3   65.74    65.9    65.3    65.6    64.8    66.3    64.7    65.5
    65.1    65.6    65.4      66    65.4    67.1    68.4    67.7    67.3    67.9
   69.42   68.82   64.32   62.12   58.42   58.13   58.52   57.42   57.62   57.22
   58.22   59.42   60.52   60.22   59.22   59.32   61.22   60.62   59.42   57.02
   56.32   57.52   61.02   62.42   63.32   62.98   61.92   59.92   59.02   55.17
   56.31   53.15   49.86   48.88   40.42   45.43   61.63    61.7   59.35   60.56
   61.74   62.15   63.28   64.67   65.22   65.52   64.72   66.22   64.62   65.42
   65.02   65.52   65.32   65.92   65.32   67.02   68.32   67.62   67.22   67.82
Pier Skew, UpSta & Num, DnSta & Num=  ,4908.4, 2 ,4908.4, 2 , 0 , 0 , 0 ,,
     2.5     2.5
   43.52   62.67
     2.5     2.5
   43.44   62.59
Pier Skew, UpSta & Num, DnSta & Num=  ,4953.1, 2 ,4953.1, 2 , 0 , 0 , 0 ,,
     2.5     2.5
   34.61   62.64
     2.5     2.5
   34.53   62.56
Pier Skew, UpSta & Num, DnSta & Num=  ,5033.2, 2 ,5033.2, 2 , 0 , 0 , 0 ,,
     2.5     2.5
    39.3   62.67
     2.5     2.5
   39.22   62.59
Pier Skew, UpSta & Num, DnSta & Num=  ,5078.2, 2 ,5078.2, 2 , 0 , 0 , 0 ,,
     2.5     2.5
   50.64   62.72
     2.5     2.5
   50.56   62.64
Abutment Skew #Up #Dn= , 2 , 2
  4863.1  4895.4
   61.71   48.69
  4863.1  4895.4
   61.63   48.61
Abutment Skew #Up #Dn= , 2 , 2
  5065.4 5122.79
    50.3   61.78
  5065.4 5122.79
   50.22    61.7
BR Coef= 1 , 1 , 0 ,1.25, 0 ,,,.8,0,2,0,
WSPro=,,,, 1 ,,,, 0 ,,,, 0 ,,,,-1 ,-1 ,-1 , 0 , 0 , 0 , 0 , 0
BR U #Sta/Elev= 108
    3700    69.5    3770    68.9    3830    64.4  3893.5    62.2  3965.6    59.7
  3995.6    58.5  4043.5   58.21  4045.6    58.2  4055.6    58.6  4095.6    57.5
  4105.6    57.7  4115.6    57.3  4135.6    58.3  4145.6    59.5  4177.1    60.6
  4197.1    60.3  4207.1    59.3  4217.1    59.4  4237.1    61.3  4243.5   61.25
  4317.1    60.7  4337.1    59.5  4347.1    57.1  4357.1    56.4  4367.1    57.1
  4370.7    57.6  4390.7    61.1  4410.7    62.5  4459.4    62.8  4463.8   62.83
  4539.4    63.4  4549.2   63.06  4579.6      62  4609.2   60.52  4611.3   60.42
  4619.6      60  4629.6    59.1 4630.79   58.86  4630.9   58.83 4631.01   58.81
  4633.3   58.34  4648.3   55.25  4648.6   56.39  4671.6   53.31  4672.2   53.23
  4704.6   49.94  4748.4   49.43  4775.3   49.14  4791.6   48.96  4845.1    40.5
    4863   45.45 4863.21   45.51  4863.3   45.53  4882.9   50.95  4895.4   48.69
  4905.4   46.88  4908.4   44.71  4924.3   42.33    4938   36.79  4953.1    35.5
    4957   39.71  4970.6   33.49  4985.3   28.96  4989.8   25.43    4990   25.27
  4998.4   25.78  5011.2   27.13  5014.7   28.78  5025.8   36.35  5033.2    41.1
  5043.1   48.08  5065.3   50.29  5065.4    50.3  5078.2   51.79  5108.4   57.54
  5122.5   59.41 5122.59   59.42  5122.7   59.43  5131.8   60.64  5164.1   61.82
  5192.8      62  5198.7   62.04 5206.19   62.08  5206.3   62.08 5206.41   62.09
  5229.4   62.23  5263.1   62.95  5263.3   62.96    5271    63.3  5277.1   63.36
  5313.2   63.72  5417.9   64.75    5474    65.3    5534    65.6    5554    64.8
    5734    66.3    5784    64.7    5834    65.5    5854    65.1    5874    65.6
  5916.8    65.4  6076.8      66  6096.8    65.4  6216.8    67.1  6236.8    68.4
  6426.8    67.7  6466.8    67.3  6492.8    67.9
BR U #Mann= 3
    3700      .2    4957     .06  5043.1      .2
BR U Banks=4957,5043.1
BR D #Sta/Elev= 108
    3700   69.42    3770   68.82    3830   64.32  3893.5   62.12  3965.6   59.62
  3995.6   58.42  4043.5   58.13  4045.6   58.12  4055.6   58.52  4095.6   57.42
  4105.6   57.62  4115.6   57.22  4135.6   58.22  4145.6   59.42  4177.1   60.52
  4197.1   60.22  4207.1   59.22  4217.1   59.32  4237.1   61.22  4243.5   61.17
  4317.1   60.62  4337.1   59.42  4347.1   57.02  4357.1   56.32  4367.1   57.02
  4370.7   57.52  4390.7   61.02  4410.7   62.42  4459.4   62.72  4463.8   62.75
  4539.4   63.32  4549.2   62.98  4579.6   61.92  4609.2   60.44  4611.3   60.34
  4619.6   59.92  4629.6   59.02 4630.79   58.78  4630.9   58.75 4631.01   58.73
  4633.3   58.26  4648.3   55.17  4648.6   56.31  4671.6   53.23  4672.2   53.15
  4704.6   49.86  4748.4   49.35  4775.3   49.06  4791.6   48.88  4845.1   40.42
    4863   45.37 4863.21   45.43  4863.3   45.45  4882.9   50.87  4895.4   48.61
  4905.4    46.8  4908.4   44.63  4924.3   42.25    4938   36.71  4953.1   35.42
    4957   39.63  4970.6   33.41  4985.3   28.88  4989.8   25.35    4990   25.19
  4998.4    25.7  5011.2   27.05  5014.7    28.7  5025.8   36.27  5033.2   41.02
  5043.1      48  5065.3   50.21  5065.4   50.22  5078.2   51.71  5108.4   57.46
  5122.5   59.33 5122.59   59.34  5122.7   59.35  5131.8   60.56  5164.1   61.74
  5192.8   61.92  5198.7   61.96 5206.19      62  5206.3      62 5206.41   62.01
  5229.4   62.15  5263.1   62.87  5263.3   62.88    5271   63.22  5277.1   63.28
  5313.2   63.64  5417.9   64.67    5474   65.22    5534   65.52    5554   64.72
    5734   66.22    5784   64.62    5834   65.42    5854   65.02    5874   65.52
  5916.8   65.32  6076.8   65.92  6096.8   65.32  6216.8   67.02  6236.8   68.32
  6426.8   67.62  6466.8   67.22  6492.8   67.82
BR D #Mann= 3
    3700      .2    4957     .06  5043.1      .2
BR D Banks=4957,5043.1
BC Design=,, 0 ,, 0 ,,,,,,
BC HTab HWMax=69.53

Type RM Length L Ch R = 1 ,196115.7,548.3,548.3,548.3
BEGIN DESCRIPTION:
Downstream Section of Bridge/Culvert/Weir
END DESCRIPTION:
XS GIS Cut Line= 6
      3071386.79     13836708.63      3071512.81     13836352.99
      3071400.58     13835844.85       3071703.9     13835212.58
      3071660.06     13834587.53      3071369.66     13834116.91
#Sta/Elev= 30
    3700   69.39    3770   68.79    3830   64.29  3995.6   58.39  4115.6   57.19
  4237.1   61.19  4317.1   60.59  4357.1   56.29  4410.7   62.39  4539.4   63.29
  4619.6   59.89  4704.6   49.83  4791.6   48.85  4845.1   40.39  4882.9   50.84
  4924.3   42.22    4938   36.68  4953.1   35.39    4957    39.6  4985.3   28.85
    4990   25.16  5011.2   27.02  5043.1   47.97  5131.8   60.53    5271   63.19
    5734   66.19    5784   64.59  6096.8   65.29  6236.8   68.29  6492.8   67.79
#Mann= 3 ,-1 , 0
    3700      .2       0    4957     .06       0  5043.1      .2       0
#XS Ineff= 2 , 0
            4850    61.2    5130              65
Permanent Ineff=
       F       F
Bank Sta=4957,5043.1
XS Rating Curve= 0
Exp/Cntr=.5,.3

Type RM Length L Ch R = 1 ,195567.4,993.8,953.3,655.4
BEGIN DESCRIPTION:
Cross Section 195567.4
END DESCRIPTION:
XS GIS Cut Line= 6
      3071302.22     13836874.23      3071634.31     13836329.44
      3071842.16     13835689.82        3071904.     13834924.56
       3071784.4     13834519.68      3071296.67     13833966.49
#Sta/Elev= 30
  3981.9    69.5  4221.9    68.1  4301.9    61.7  4801.9    58.1  4823.2    56.3
  4850.9   50.05  4878.2   51.92  4882.5   50.58  4900.3   44.31  4914.3    43.8
  4938.5   35.34  4954.3   33.28  4968.4   26.88  5015.3   23.51  5031.6   25.22
  5037.9   34.06  5042.8   38.03  5048.7   41.83  5050.7   41.92    5097   42.74
  5133.2    34.9  5163.2    34.7  5233.2    44.3  5462.3    41.1  5592.3    65.9
  5722.3    63.6  5952.3      67  6440.1    64.4  6860.1    68.6  7219.9    66.9
#Mann= 5 ,-1 , 0
  3981.9      .2       0  4882.5     .15       0  4954.3     .06       0
  5042.8     .15       0  5050.7      .2       0
Bank Sta=4878.2,5048.7
XS Rating Curve= 0
Exp/Cntr=.3,.1

Type RM Length L Ch R = 1 ,194614.1,927.3,938.5,629.7
BEGIN DESCRIPTION:
Cross Section 194614.1
END DESCRIPTION:
XS GIS Cut Line= 6
      3073086.68     13836703.21      3072703.27      13836208.5
      3072567.23     13835522.08      3072443.55     13835392.22
      3071845.02     13834482.16      3071364.85     13833995.76
#Sta/Elev= 30
  3720.8    67.3  4260.8      62  4696.7    61.4  4826.7    54.3  4857.5   48.36
  4874.7   40.48  4950.6   42.22  4951.7   42.26  4965.4   38.67  4979.2    26.6
  5004.3   26.15  5027.3   29.56  5037.2   33.79  5046.6   40.92    5054   42.73
    5055   42.73    5089   45.32  5101.3   40.93  5225.8    41.2  5255.8    38.9
  5275.8    41.2  5355.8    58.2  5415.8    62.7  5515.8    65.3  5615.8    61.1
  5665.8    64.8  5887.9      67  6017.9    64.9  6467.9    65.2  6998.5    67.8
#Mann= 5 ,-1 , 0
  3720.8      .2       0  4950.6     .15       0  4965.4     .06       0
  5046.6     .15       0    5055      .2       0
Bank Sta=4951.7,5054
XS Rating Curve= 0
Exp/Cntr=.3,.1

Type RM Length L Ch R = 1 ,193675.6,586.7,855.3,972.3
BEGIN DESCRIPTION:
Cross Section 193675.6
END DESCRIPTION:
XS GIS Cut Line= 5
      3073723.62     13835856.01      3073445.35     13835181.97
      3072833.14     13834885.14      3072251.85     13834637.78
      3071408.48     13833984.94
#Sta/Elev= 30
  3406.5    67.4  3407.2   67.39  3986.5    61.6  4036.5    58.9  4076.5    62.4
  4155.7    63.6  4205.7    58.1  4285.7    38.9  4315.7    34.6  4549.5   33.87
  4755.7    34.7  4912.2   41.66    4940   41.11  4947.7   35.86  4959.2   36.02
  4979.1   26.81  5004.8   23.35  5020.9   26.73  5038.9   39.76  5081.3   36.67
  5128.4   37.32  5170.9      53  5216.1    62.7  5276.1    65.1  5366.1    61.2
  5406.1      66  5747.8    65.4  5817.8    62.5  6197.8    67.9  6514.4    68.1
#Mann= 5 ,-1 , 0
  3406.5     .99       0  3407.2      .2       0  4549.5     .04       0
  4959.2     .06       0  5038.9      .2       0
Bank Sta=4959.2,5038.9
XS Rating Curve= 0
Exp/Cntr=.3,.1

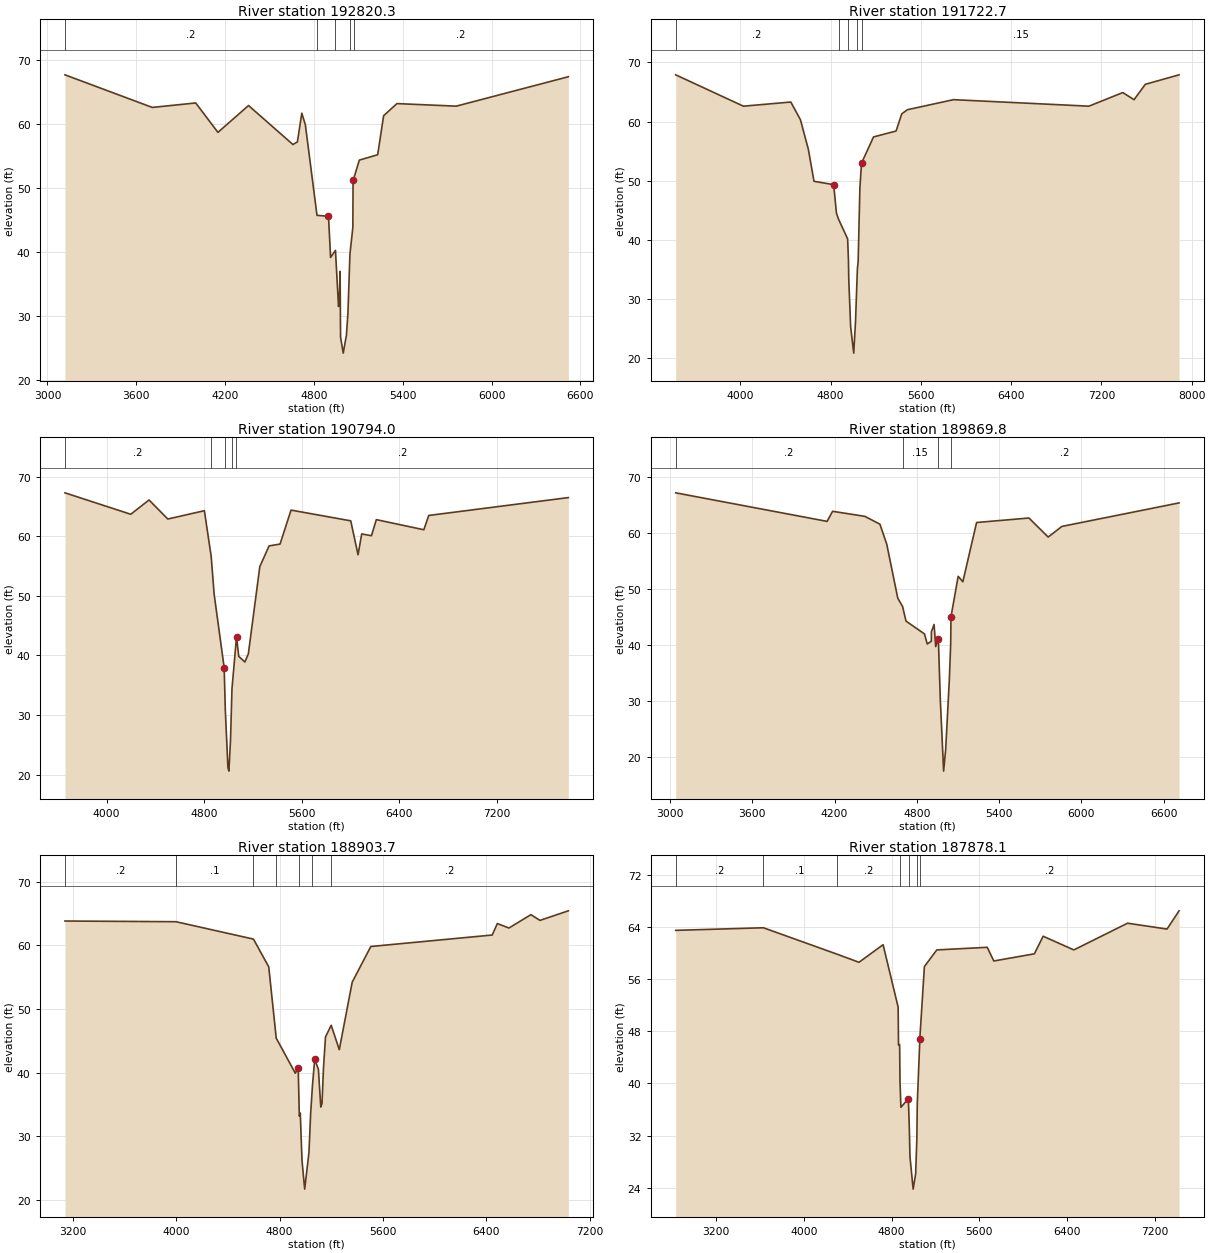
Type RM Length L Ch R = 1 ,192820.3,666.8,1097.6,818.7
BEGIN DESCRIPTION:
Cross Section 192820.3
END DESCRIPTION:
XS GIS Cut Line= 6
      3073766.91     13835818.91       3073618.5     13835008.82
      3073426.79     13834650.15      3073136.15     13834384.24
       3073072.2     13833592.09      3072670.69     13832701.36
#Sta/Elev= 30
    3118    67.7    3708    62.6  4001.6    63.3  4151.6    58.7  4358.3    62.9
  4658.3    56.8  4688.3    57.2  4718.3    61.7  4742.2    59.9  4820.9   45.72
  4898.6   45.58  4912.7   39.14  4945.7   40.25  4966.3   31.46  4971.8   32.24
    4977   36.96  4980.1   26.66  4998.1   24.17  5019.8   26.99    5030   30.47
  5043.4   39.62  5063.1   43.84  5064.6   51.27  5068.1   51.39  5106.8   54.36
    5231    55.2    5271    61.3    5361    63.2  5761.8    62.8    6519    67.4
#Mann= 5 ,-1 , 0
    3118      .2       0  4820.9     .15       0  4945.7     .06       0
  5043.4     .15       0  5068.1      .2       0
Bank Sta=4898.6,5064.6
XS Rating Curve= 0
Exp/Cntr=.3,.1

Type RM Length L Ch R = 1 ,191722.7,805.1,928.7,891.2
BEGIN DESCRIPTION:
Cross Section 191722.7
END DESCRIPTION:
XS GIS Cut Line= 5
      3073791.65     13835849.83      3073705.07     13834807.84
      3073742.17     13834412.07      3073927.69     13833410.27
      3073624.68     13831434.51
#Sta/Elev= 30
    3428    67.9    4028    62.6    4448    63.3  4533.6    60.3  4603.6    55.3
  4653.6    49.9  4827.9   49.33  4852.6   44.51  4871.2   43.48  4951.5   40.18
  4958.7   36.62  4961.7   33.29  4978.2   25.34  5005.6   20.85  5021.7   26.27
    5038    35.1  5044.7   36.23  5060.3    48.8  5074.5   52.92  5078.8   53.14
  5181.1    57.4  5381.1    58.4  5431.1    61.3  5481.1      62  5889.9    63.7
  7089.9    62.6  7389.9    64.9  7489.9    63.7  7589.9    66.3  7888.8    67.9
#Mann= 5 ,-1 , 0
    3428      .2       0  4871.2     .15       0  4951.5     .06       0
    5038      .1       0  5078.8     .15       0
Bank Sta=4827.9,5074.5
XS Rating Curve= 0
Exp/Cntr=.3,.1

Type RM Length L Ch R = 1 ,190794.0,521.9,924.2,1039.1
BEGIN DESCRIPTION:
Cross Section 190794.0
END DESCRIPTION:
XS GIS Cut Line= 5
      3073859.67      13836016.8      3074391.49      13835361.3
      3074440.96     13834792.38      3074490.43     13833147.45
      3074694.59     13832097.13
#Sta/Elev= 30
  3658.6    67.3  4198.6    63.7  4348.6    66.1  4502.7    62.9  4802.7    64.3
  4858.9   56.57  4882.7    50.3  4965.1   37.95  4974.4    30.9    4996   21.19
  5003.9   20.58  5017.2   25.77  5029.3   34.44  5065.6   42.92  5066.4   43.11
  5084.9   39.84  5135.3    38.9  5163.6   40.28  5257.5    54.9  5333.6   58.39
  5423.8    58.7  5513.8    64.4  6003.8    62.6  6063.8    56.9  6093.8    60.4
  6173.8    60.1  6213.8    62.8  6603.8    61.1  6643.8    63.5  7789.4    66.5
#Mann= 5 ,-1 , 0
  3658.6      .2       0  4858.9      .1       0  4974.4     .06       0
  5029.3      .1       0  5065.6      .2       0
Bank Sta=4965.1,5066.4
XS Rating Curve= 0
Exp/Cntr=.3,.1

Type RM Length L Ch R = 1 ,189869.8,985.4,966.1,612.4
BEGIN DESCRIPTION:
Cross Section 189869.8
END DESCRIPTION:
XS GIS Cut Line= 6
      3073872.04     13836060.08      3074323.46     13835658.13
      3074966.59      13834668.7      3075380.91     13834483.18
      3075622.09     13834291.48      3075906.55     13833203.11
#Sta/Elev= 30
  3040.9    67.2  4145.3    62.1  4185.3    63.9  4420.6      63  4530.6    61.6
  4580.6      58  4660.6    48.4  4696.1   46.89  4720.6    44.3  4855.7      42
  4875.7    40.2  4905.7    40.7  4906.1   42.39  4925.6   43.68  4937.5   39.74
  4953.8   41.06  4958.1   40.15  4971.4   30.06  4995.2    17.5  5010.3   21.41
  5036.6   33.68  5046.8   40.22  5048.8   45.03  5101.3   52.29  5135.5   51.32
  5235.7    61.9  5617.8    62.7  5757.8    59.3  5857.8    61.2  6712.7    65.4
#Mann= 4 ,-1 , 0
  3040.9      .2       0  4696.1     .15       0  4953.8     .06       0
  5048.8      .2       0
Bank Sta=4953.8,5048.8
XS Rating Curve= 0
Exp/Cntr=.3,.1

Type RM Length L Ch R = 1 ,188903.7,911.4,1025.6,1048.7
BEGIN DESCRIPTION:
Cross Section 188903.7
END DESCRIPTION:
XS GIS Cut Line= 6
      3074706.87     13836752.68      3075288.16     13836239.42
      3075411.83     13836035.35      3075510.78     13835571.55
      3075566.43      13834977.9       3075962.2     13833209.29
#Sta/Elev= 30
  3137.3    63.8  3997.3   63.69  4597.3   60.96  4715.7    56.6  4773.5   45.42
  4921.2   39.91  4943.8   40.67  4952.5   33.17  4959.8   33.65    4973   26.26
  4993.9   21.71  5027.1   27.47  5040.2   33.61  5054.1   37.95  5071.5   42.08
  5100.2   40.53  5118.6   34.59  5128.3   35.15  5139.4   40.67    5155    45.6
  5199.4   47.43  5261.9    43.6  5361.9    54.2  5506.1    59.8  6446.1    61.6
  6486.1    63.4  6576.1    62.7  6746.1    64.8  6816.1    63.9  7035.8    65.4
#Mann= 7 ,-1 , 0
  3137.3      .2       0  3997.3      .1       0  4597.3      .2       0
  4773.5     .15       0  4952.5     .06       0  5054.1     .15       0
  5199.4      .2       0
Bank Sta=4943.8,5071.5
XS Rating Curve= 0
Exp/Cntr=.3,.1

Type RM Length L Ch R = 1 ,187878.1,1030.8,1342,887.4
BEGIN DESCRIPTION:
Cross Section 187878.1
END DESCRIPTION:
XS GIS Cut Line= 6
      3074805.81     13836721.76      3075492.23     13836230.14
      3076153.91      13835784.9      3076413.63     13835512.81
      3076605.33     13835203.61      3077679.86     13833272.45
#Sta/Elev= 30
  2831.4    63.5  3631.4    63.9  4299.4   59.87  4503.2    58.6  4723.2    61.3
  4860.5   51.72  4863.9   45.91    4874   45.97  4877.4   40.35  4880.3   39.02
  4885.5   36.34  4953.5   37.64  4962.1   33.48  4968.3   28.77  4997.4   23.78
  5020.4   26.16    5031   31.43    5035   36.87  5058.7   46.87  5059.9   47.33
  5100.2   57.95  5213.2    60.5  5673.2    60.9  5733.2    58.8  6103.2    59.9
  6183.2    62.6  6463.2    60.5  6953.2    64.6  7313.2    63.7  7423.2    66.5
#Mann= 7 ,-1 , 0
  2831.4      .2       0  3631.4      .1       0  4299.4      .2       0
  4880.3     .15       0  4962.1     .06       0    5035     .15       0
  5059.9      .2       0
Bank Sta=4953.5,5058.7
XS Rating Curve= 0
Exp/Cntr=.3,.1