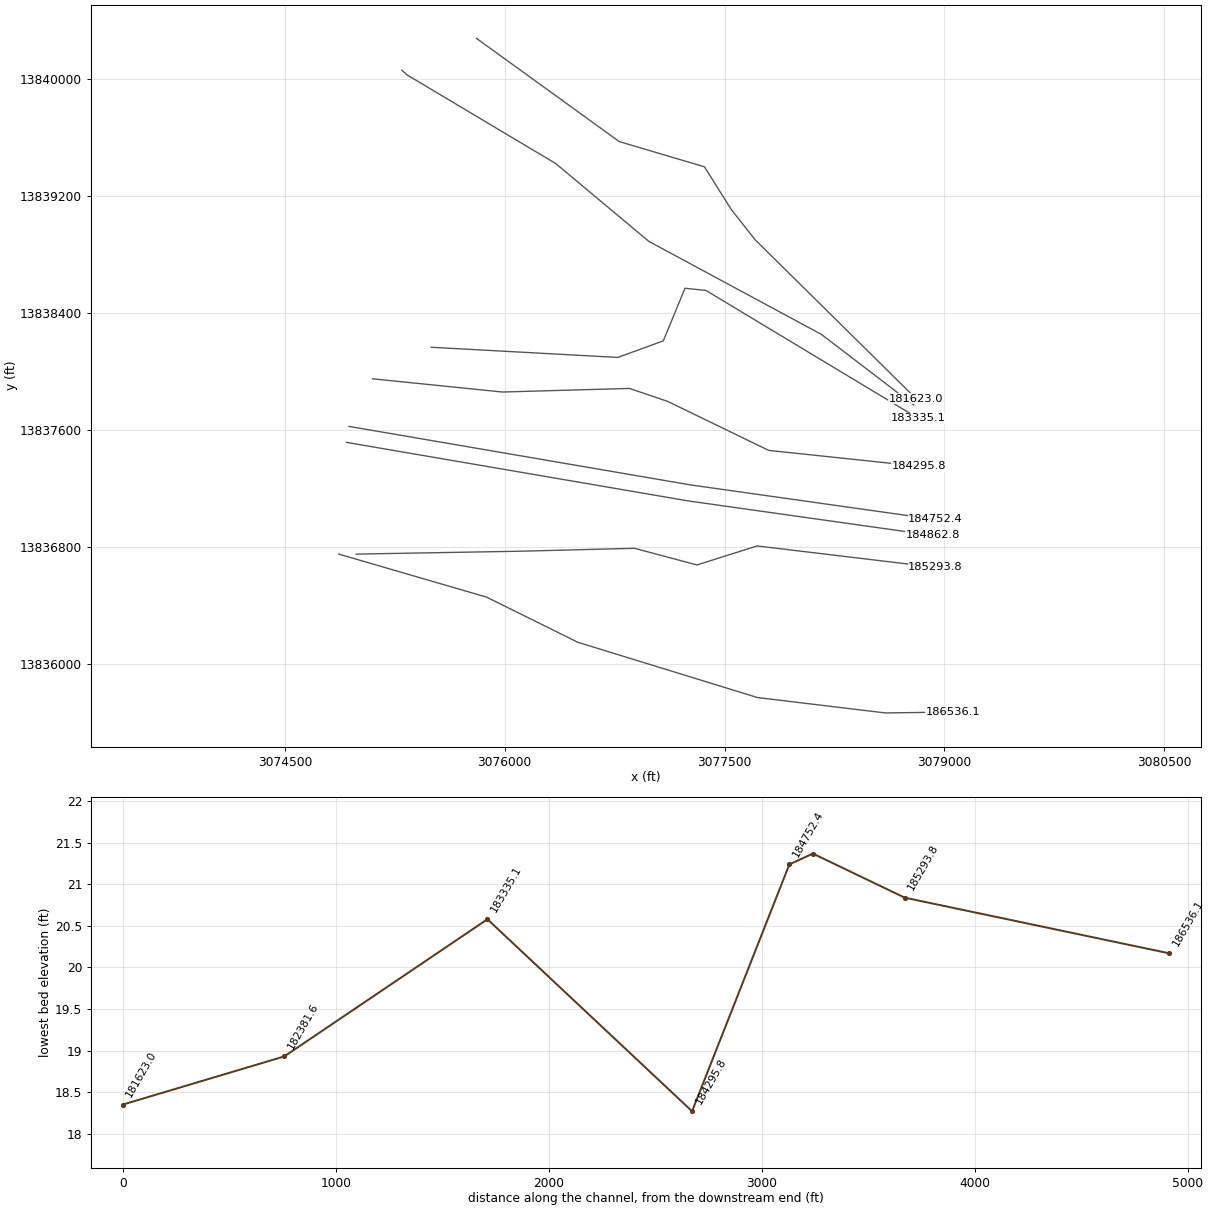
HEC-RAS study W100-00-00.prj: W100-00-00

--- W100-00-00.g01 (geometry) --- (continued)

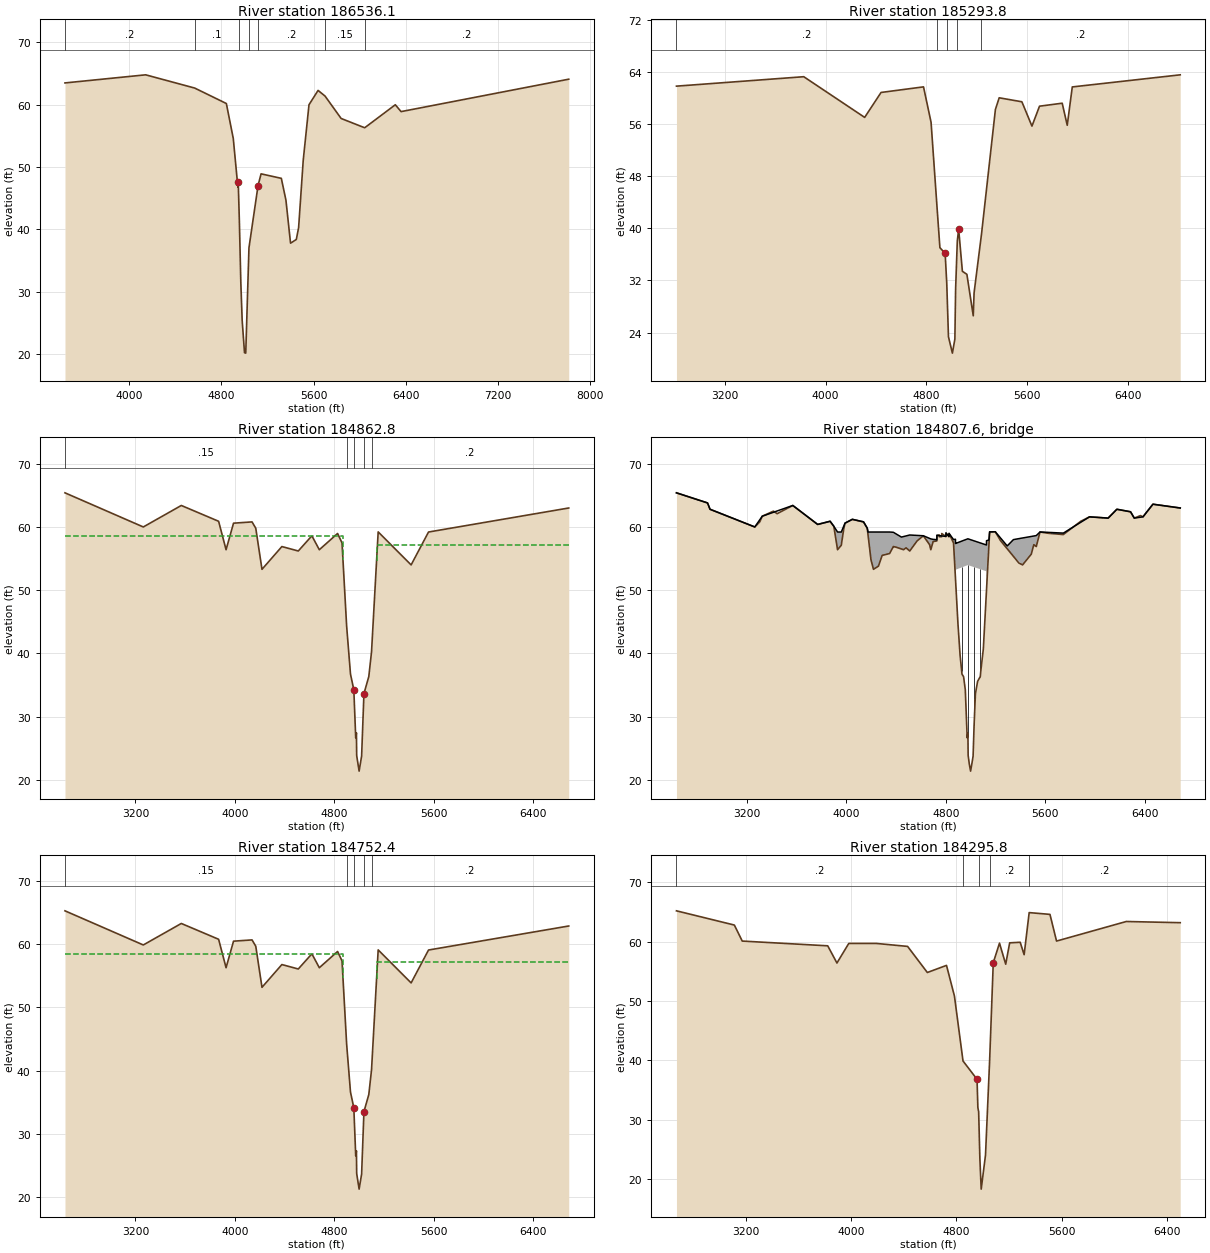
Type RM Length L Ch R = 1 ,186536.1,1064.5,1242.3,806.1
BEGIN DESCRIPTION:
Cross Section 186536.1
END DESCRIPTION:
XS GIS Cut Line= 6
      3074867.65     13836752.68      3075875.63     13836458.95
      3076500.21     13836149.75      3077724.62     13835772.53
      3078596.56      13835667.4      3079060.35     13835673.59
#Sta/Elev= 30
  3443.7    63.5  4143.7    64.8  4568.7   62.68  4843.6    60.2  4903.6    54.6
  4943.6    46.8  4946.6   47.67  4956.4   41.39  4969.1   31.53  4980.8   25.42
  5001.1   20.24  5011.9   20.17  5039.7   37.05  5118.6   47.04  5119.7   47.12
  5144.8   48.92  5320.5    48.2  5360.5    44.7  5400.5    37.8  5450.5    38.4
  5470.5    40.3  5510.5    51.1  5560.5      60  5639.3    62.3  5699.9   61.39
  5839.3    57.8  6043.7   56.31  6309.3      60  6359.3    58.9  7813.8    64.1
#Mann= 7 ,-1 , 0
  3443.7      .2       0  4568.7      .1       0  4956.4     .06       0
  5039.7      .1       0  5119.7      .2       0  5699.9     .15       0
  6043.7      .2       0
Bank Sta=4946.6,5118.6
XS Rating Curve= 0
Exp/Cntr=.3,.1

Type RM Length L Ch R = 1 ,185293.8,398.5,431,406.1
BEGIN DESCRIPTION:
Cross Section 185293.8
END DESCRIPTION:
XS GIS Cut Line= 6
      3074986.38     13836752.68      3076109.38     13836772.47
      3076886.08     13836792.26      3077311.54     13836678.48
      3077722.21     13836808.38      3078939.01     13836662.36
#Sta/Elev= 30
  2816.5   61.86  3826.5   63.31  4309.7   57.06  4439.7   60.89  4776.6   61.75
  4836.6    56.3  4884.8      43  4906.6   37.05  4948.3   36.15    4961   31.58
  4974.6   23.35  5005.7   20.84  5025.4      23  5031.3   30.69  5044.6   38.04
  5055.4   39.91    5085   33.41  5120.7   32.95  5171.3   26.57  5177.8    30.1
  5236.6   39.12    5347   58.28    5377   60.07    5557   59.46  5636.9   55.72
  5696.9   58.78  5876.9   59.24  5916.9   55.85  5956.9   61.74  6813.3    63.6
#Mann= 5 ,-1 , 0
  2816.5      .2       0  4884.8     .15       0    4961     .06       0
  5044.6     .15       0  5236.6      .2       0
Bank Sta=4948.3,5055.4
XS Rating Curve= 0
Exp/Cntr=.5,.3

Type RM Length L Ch R = 1 ,184862.8,110.4,110.4,110.4
BEGIN DESCRIPTION:
Upstream Section of Bridge/Culvert/Weir
END DESCRIPTION:
XS GIS Cut Line= 4
      3074920.16      13837516.2      3077095.34     13837142.98
      3077252.28     13837116.06      3078921.71     13836880.22
#Sta/Elev= 30
  2633.8   65.39  3263.8   59.99  3569.6   63.39  3869.6   60.89  3929.6   56.39
  3989.6   60.59  4138.5   60.79  4168.5   59.79  4218.5   53.29  4378.5   56.89
  4510.5   56.19  4619.8   58.59  4679.8   56.39  4826.6   58.96  4862.4   57.47
  4899.4   44.32  4930.4   36.72  4957.2   34.24  4972.5   26.63  4978.2   27.43
  4980.1   23.86  4999.8   21.37  5019.9   23.76  5038.6   33.62  5077.7   36.33
  5099.7   40.25  5153.1   59.21  5418.1   53.99  5558.1   59.19    6686   62.99
#Mann= 5 ,-1 , 0
  2633.8     .15       0  4899.4      .1       0  4957.2     .06       0
  5038.6      .1       0  5099.7      .2       0
#XS Ineff= 2 , 0
            4870    58.5    5140            57.2
Permanent Ineff=
       F       F
Bank Sta=4957.2,5038.6
XS Rating Curve= 0
Exp/Cntr=.5,.3

Type RM Length L Ch R = 3 ,184807.6,,,
BEGIN DESCRIPTION:
SAN FELIPE ROAD
Structure ID: W00-64
END DESCRIPTION:
Bridge Culvert--1,0,-1,-1, 0
Deck Dist Width WeirC Skew NumUp NumDn MinLoCord MaxHiCord MaxSubmerge Is_Ogee
10,90.4,2.6,0, 60, 60, , , .95, 0, 1,1,,
  2633.8  2883.8  2903.8  3263.8  3323.8  3569.6  3769.6  3869.6  3899.6  3929.6
  3959.6  3989.6  4048.5  4138.5  4168.5  4175.2  4198.5  4218.5  4258.5  4288.5
  4348.5  4378.5  4443.2  4510.5  4619.8  4679.8  4698.6  4728.4  4728.7  4801.5
  4801.7  4826.1  4826.6  4862.4  4878.2 4878.41  4878.5  4977.9 5127.29  5127.4
  5127.8  5146.9  5153.1  5198.6  5294.3  5344.3  5418.1  5488.1  5508.1  5528.1
  5558.1  5745.9  5956.1  6106.1  6176.4  6286.4  6316.4  6386.4  6466.4    6686
    65.4    63.8    62.8      60    61.7    63.4    60.4    60.9   60.11    59.2
    59.2   60.61   61.21   60.81   59.81    59.2    59.2    59.2    59.2    59.2
    59.2   59.16    58.4   58.73   58.61   58.11   58.04   57.99   58.68    58.5
   59.05   58.48   58.98   58.01   58.06   57.39   57.39   58.13   57.15   57.15
   57.83   57.94   59.23   59.24      57      58   58.26    58.5   58.57   58.64
   59.21   59.03    61.6    61.4    62.8    62.4    61.4    61.6    63.6      63
    65.4    63.8    62.8      60    61.7    63.4    60.4    60.9    60.1    56.4
    57.1    60.6    61.2    60.8    59.8   58.68    54.8    53.3    53.8    55.5
    55.8    56.9   56.52    56.2    58.6    56.4   57.69   57.79   58.67   58.49
   59.04   58.47   58.97   57.48   51.84   51.76   53.23   53.97   52.99   49.87
   50.02   56.96   59.22   59.23   56.55   55.35      54    55.7    57.2    56.9
    59.2    58.8    61.6    61.4    62.8    62.4    61.4    61.6    63.6      63
  2633.8  2883.8  2903.8  3263.8  3323.8  3569.6  3769.6  3869.6  3899.6  3929.6
  3959.6  3989.6  4048.5  4138.5  4168.5  4175.2  4198.5  4218.5  4258.5  4288.5
  4348.5  4378.5  4443.2  4510.5  4619.8  4679.8  4698.6  4728.4  4728.7  4801.5
  4801.7  4826.1  4826.6  4862.4  4878.2 4878.41  4878.5  4977.9 5127.29  5127.4
  5127.8  5146.9  5153.1  5198.6  5294.3  5344.3  5418.1  5488.1  5508.1  5528.1
  5558.1  5745.9  5956.1  6106.1  6176.4  6286.4  6316.4  6386.4  6466.4    6686
    65.4    63.8    62.8      60    61.7    63.4    60.4    60.9   60.11    59.2
    59.2   60.61   61.21   60.81   59.81    59.2    59.2    59.2    59.2    59.2
    59.2   59.16    58.4   58.73   58.61   58.11   58.04   57.99   58.68    58.5
   59.05   58.48   58.98   58.01   58.06   57.39   57.39   58.13   57.15   57.15
   57.83   57.94   59.23   59.24      57      58   58.26    58.5   58.57   58.64
   59.21   59.03    61.6    61.4    62.8    62.4    61.4    61.6    63.6      63
   65.33   63.73   62.73   59.93   61.63   63.33   60.33   60.83   60.03   56.33
   57.03   60.53   61.13   60.73   59.73   58.61   54.73   53.23   53.73   55.43
   55.73   56.83   56.45   56.13   58.53   56.33   57.62   57.72    58.6   58.42
   58.97    58.4    58.9   57.41   51.77   51.69   53.16    53.9   52.92    49.8
   49.95   56.89   59.15   59.16   56.48   55.28   53.93   55.63   57.13   56.83
   59.13   58.73   61.53   61.33   62.73   62.33   61.33   61.53   63.53   62.93
Pier Skew, UpSta & Num, DnSta & Num=  ,4928.1, 2 ,4928.1, 2 , 0 , 0 , 0 ,,
       2       2
      36   54.61
       2       2
   35.93   54.54
Pier Skew, UpSta & Num, DnSta & Num=  ,4978.2, 2 ,4978.2, 2 , 0 , 0 , 0 ,,
       2       2
   24.56   54.96
       2       2
   24.49   54.89
Pier Skew, UpSta & Num, DnSta & Num=  ,5028, 2 ,5028, 2 , 0 , 0 , 0 ,,
       2       2
   27.06   54.65
       2       2
   26.99   54.58
Pier Skew, UpSta & Num, DnSta & Num=  ,5077.7, 2 ,5077.7, 2 , 0 , 0 , 0 ,,
       2       2
    35.3   54.33
       2       2
   35.23   54.26
Abutment Skew #Up #Dn= , 2 , 2
  4878.3  4930.4
   53.23   36.73
  4878.3  4930.4
   53.16   36.66
Abutment Skew #Up #Dn= , 2 , 2
    5083 5127.49
   37.43   52.99
    5083 5127.49
   37.36   52.92
BR Coef= 1 , 1 , 0 ,1.25, 0 ,,,.8,0,2,0,
WSPro=,,,, 1 ,,,, 0 ,,,, 0 ,,,,-1 ,-1 ,-1 , 0 , 0 , 0 , 0 , 0
BR U #Sta/Elev= 124
  2633.8    65.4  2883.8    63.8  2903.8    62.8  3263.8      60  3303.8    60.8
  3323.8    61.7  3413.8    62.5  3443.8    62.1  3569.6    63.4  3769.6    60.4
  3869.6    60.9  3875.2   60.75  3899.6    60.1  3929.6    56.4  3959.6    57.1
  3979.6    59.7  3989.6    60.6  4048.5    61.2  4138.5    60.8  4168.5    59.8
  4175.2   58.68  4198.5    54.8  4218.5    53.3  4258.5    53.8  4288.5    55.5
  4348.5    55.8  4375.2   56.78  4378.5    56.9  4400.5    56.8  4443.2   56.52
  4460.5    56.4  4463.2   56.44  4480.5    56.7  4510.5    56.2  4569.8    57.8
  4619.8    58.6  4669.8    57.2  4679.8    56.4  4698.6   57.69  4710.9   57.73
  4728.4   57.79  4728.7   58.67  4747.5   58.73  4747.8   58.45  4767.1   58.46
  4767.8   58.96  4794.4   58.59  4801.5   58.49  4801.7   59.04  4826.1   58.47
  4826.6   58.97  4841.3   58.36  4862.4   57.48 4863.89   56.95    4864   56.91
 4864.11   56.87  4878.2   51.84  4878.3    51.8 4878.41   51.76  4878.5   51.73
  4898.4   44.62  4899.4   44.33  4915.1   39.74  4928.1    37.2  4930.3   36.75
  4930.4   36.73  4943.4   36.32  4957.2   34.25  4972.5   26.64  4977.9    27.4
  4978.2   27.44  4980.1   23.87  4989.4    22.5  4999.8   21.38  5012.4   22.82
  5019.9   23.77    5028   28.66  5038.6   33.63  5056.1   35.58  5077.7   36.34
  5082.9   37.41    5083   37.43  5099.7   40.26  5102.1   40.67 5127.29   49.83
  5127.4   49.87  5127.5   49.91  5127.8   50.02 5141.99   55.18  5142.1   55.22
 5142.21   55.26  5146.9   56.96  5153.1   59.22  5183.9   59.23  5198.6   59.23
  5235.6   58.01    5237   57.95  5238.1    57.9  5294.3   56.55  5344.3   55.35
  5388.1    54.3  5418.1      54  5488.1    55.7  5508.1    57.2  5528.1    56.9
  5544.3   58.14  5558.1    59.2  5625.9      59  5738.7   58.81  5745.9    58.8
  5788.7   59.44  5858.7   60.49  5886.1    60.9  5888.7   60.93  5903.4   61.07
  5956.1    61.6  6106.1    61.4  6176.4    62.8  6286.4    62.4  6316.4    61.4
  6366.4    61.8  6386.4    61.6  6466.4    63.6    6686      63
BR U #Mann= 5
  2633.8     .15  4899.4      .1  4957.2     .06  5038.6      .1  5099.7      .2
BR U Banks=4957.2,5038.6
BR D #Sta/Elev= 124
  2633.8   65.33  2883.8   63.73  2903.8   62.73  3263.8   59.93  3303.8   60.73
  3323.8   61.63  3413.8   62.43  3443.8   62.03  3569.6   63.33  3769.6   60.33
  3869.6   60.83  3875.2   60.68  3899.6   60.03  3929.6   56.33  3959.6   57.03
  3979.6   59.63  3989.6   60.53  4048.5   61.13  4138.5   60.73  4168.5   59.73
  4175.2   58.61  4198.5   54.73  4218.5   53.23  4258.5   53.73  4288.5   55.43
  4348.5   55.73  4375.2   56.71  4378.5   56.83  4400.5   56.73  4443.2   56.45
  4460.5   56.33  4463.2   56.37  4480.5   56.63  4510.5   56.13  4569.8   57.73
  4619.8   58.53  4669.8   57.13  4679.8   56.33  4698.6   57.62  4710.9   57.66
  4728.4   57.72  4728.7    58.6  4747.5   58.66  4747.8   58.38  4767.1   58.39
  4767.8   58.89  4794.4   58.52  4801.5   58.42  4801.7   58.97  4826.1    58.4
  4826.6    58.9  4841.3   58.29  4862.4   57.41 4863.89   56.88    4864   56.84
 4864.11    56.8  4878.2   51.77  4878.3   51.73 4878.41   51.69  4878.5   51.66
  4898.4   44.55  4899.4   44.26  4915.1   39.67  4928.1   37.13  4930.3   36.68
  4930.4   36.66  4943.4   36.25  4957.2   34.18  4972.5   26.57  4977.9   27.33
  4978.2   27.37  4980.1    23.8  4989.4   22.43  4999.8   21.31  5012.4   22.75
  5019.9    23.7    5028   28.59  5038.6   33.56  5056.1   35.51  5077.7   36.27
  5082.9   37.34    5083   37.36  5099.7   40.19  5102.1    40.6 5127.29   49.76
  5127.4    49.8  5127.5   49.84  5127.8   49.95 5141.99   55.11  5142.1   55.15
 5142.21   55.19  5146.9   56.89  5153.1   59.15  5183.9   59.16  5198.6   59.16
  5235.6   57.94    5237   57.88  5238.1   57.83  5294.3   56.48  5344.3   55.28
  5388.1   54.23  5418.1   53.93  5488.1   55.63  5508.1   57.13  5528.1   56.83
  5544.3   58.07  5558.1   59.13  5625.9   58.93  5738.7   58.74  5745.9   58.73
  5788.7   59.37  5858.7   60.42  5886.1   60.83  5888.7   60.86  5903.4      61
  5956.1   61.53  6106.1   61.33  6176.4   62.73  6286.4   62.33  6316.4   61.33
  6366.4   61.73  6386.4   61.53  6466.4   63.53    6686   62.93
BR D #Mann= 5
  2633.8     .15  4899.4      .1  4957.2     .06  5038.6      .1  5099.7      .2
BR D Banks=4957.2,5038.6
BC Design=,, 0 ,, 0 ,,,,,,
BC HTab HWMax=65.39

Type RM Length L Ch R = 1 ,184752.4,456.6,456.6,456.6
BEGIN DESCRIPTION:
Downstream Section of Bridge/Culvert/Weir
END DESCRIPTION:
XS GIS Cut Line= 4
      3074937.48     13837625.23      3077112.66     13837252.02
       3077269.6      13837225.1      3078939.02     13836989.26
#Sta/Elev= 30
  2633.8   65.26  3263.8   59.86  3569.6   63.26  3869.6   60.76  3929.6   56.26
  3989.6   60.46  4138.5   60.66  4168.5   59.66  4218.5   53.16  4378.5   56.76
  4510.5   56.06  4619.8   58.46  4679.8   56.26  4826.6   58.83  4862.4   57.34
  4899.4   44.19  4930.4   36.59  4957.2   34.11  4972.5    26.5  4978.2    27.3
  4980.1   23.73  4999.8   21.24  5019.9   23.63  5038.6   33.49  5077.7    36.2
  5099.7   40.12  5153.1   59.08  5418.1   53.86  5558.1   59.06    6686   62.86
#Mann= 5 ,-1 , 0
  2633.8     .15       0  4899.4      .1       0  4957.2     .06       0
  5038.6      .1       0  5099.7      .2       0
#XS Ineff= 2 , 0
            4870    58.5    5140            57.2
Permanent Ineff=
       F       F
Bank Sta=4957.2,5038.6
XS Rating Curve= 0
Exp/Cntr=.5,.3

Type RM Length L Ch R = 1 ,184295.8,684.7,960.7,1104.7
BEGIN DESCRIPTION:
Cross Section 184295.8
END DESCRIPTION:
XS GIS Cut Line= 6
      3075098.94     13837950.36      3075983.97     13837860.14
      3076850.59     13837884.76      3077111.56     13837796.13
      3077800.91      13837461.3       3078825.1     13837352.97
#Sta/Elev= 30
  2672.7    65.2  3112.7    62.8  3172.7    60.1  3822.3    59.3  3892.3    56.4
  3982.3    59.7  4192.3    59.7  4429.3    59.2  4579.3    54.8  4724.9      56
  4785.2   50.83  4850.4   39.88    4957   36.79  4963.3      32  4969.3   31.32
  4978.5   23.42  4988.6   18.27  5021.4   24.03    5053   40.12  5080.3   56.45
  5127.6   59.75  5174.9    56.2  5204.9    59.8  5284.9    59.9  5314.9    57.8
  5353.2    64.9  5511.2    64.6  5561.2    60.1  6091.2    63.4  6501.1    63.2
#Mann= 5 ,-1 , 0
  2672.7      .2       0  4850.4     .15       0  4969.3     .06       0
    5053      .2       0  5353.2      .2       0
Bank Sta=4957,5080.3
XS Rating Curve= 0
Exp/Cntr=.3,.1

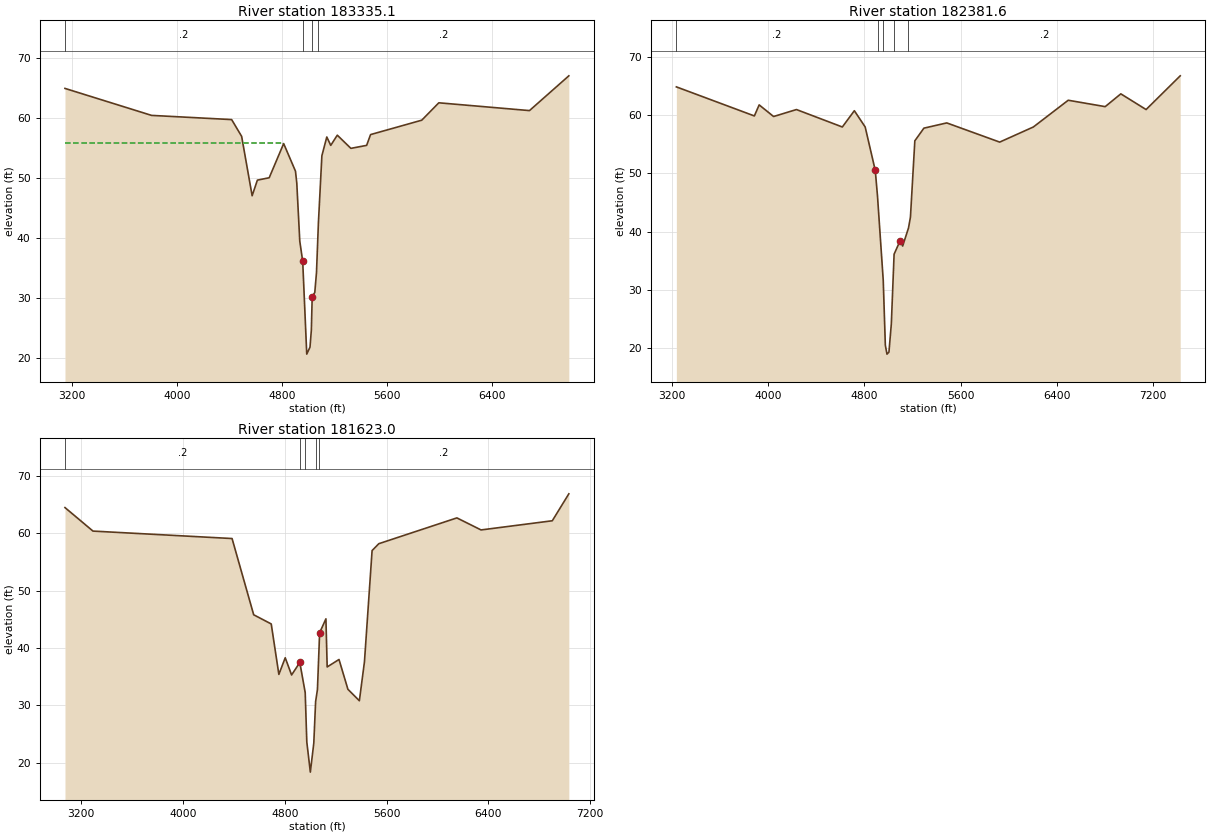
Type RM Length L Ch R = 1 ,183335.1,1181.2,953.5,663.8
BEGIN DESCRIPTION:
Cross Section 183335.1
END DESCRIPTION:
XS GIS Cut Line= 6
       3075497.6     13838165.99      3076771.81     13838096.49
      3077082.02     13838209.74      3077229.74     13838569.19
      3077372.53     13838554.42      3078822.66     13837679.72
#Sta/Elev= 30
  3145.2    64.9  3805.2    60.4  4415.2    59.7  4491.3    56.9  4571.3      47
  4611.3    49.6  4701.3      50  4811.5    55.7  4901.5    51.1  4911.5    49.1
  4934.3   39.42  4956.6   36.06  4987.4   20.58  5012.1   21.74  5022.4   24.59
  5028.9   30.18  5048.6   30.86  5061.6   34.18  5076.1   42.42  5102.7   53.67
  5140.2    56.8  5170.2    55.4  5220.2    57.1  5323.7    54.9  5443.7    55.4
  5473.7    57.2  5863.7    59.6  5993.7    62.5  6684.4    61.2  6984.4      67
#Mann= 4 ,-1 , 0
  3145.2      .2       0  4956.6     .06       0  5028.9      .1       0
  5076.1      .2       0
#XS Ineff= 2 , 0
            4810    55.8
Permanent Ineff=
       F       F
Bank Sta=4956.6,5028.9
XS Rating Curve= 0
Exp/Cntr=.3,.1

Type RM Length L Ch R = 1 ,182381.6,486.9,758.6,691.2
BEGIN DESCRIPTION:
Cross Section 182381.6
END DESCRIPTION:
XS GIS Cut Line= 6
       3075298.1     13840059.23      3075334.01     13840026.68
      3076348.35     13839421.04      3076983.54     13838889.25
      3078160.36     13838254.06      3078790.63     13837771.51
#Sta/Elev= 30
  3237.5    64.9    3886    59.9    3926    61.8    4046    59.8    4236      61
  4617.4      58  4717.4    60.8  4807.4      58  4891.3   50.53  4909.9   46.11
  4957.6   31.62  4975.1   20.46  4988.7   18.93    5005   19.27  5024.9   24.15
  5047.9   36.12  5098.4   38.46  5119.2   37.52  5167.6   40.63  5183.8   42.49
  5220.3   55.62  5295.8    57.8  5485.8    58.7  5925.8    55.4  6205.8      58
  6495.8    62.6  6803.1    61.5  6933.1    63.7  7143.1      61  7426.9    66.8
#Mann= 5 ,-1 , 0
  3237.5      .2       0  4909.9     .12       0  4957.6     .06       0
  5047.9     .15       0  5167.6      .2       0
Bank Sta=4891.3,5098.4
XS Rating Curve= 0
Exp/Cntr=.3,.1

Type RM Length L Ch R = 1 ,181623.0,747.9,891.8,349.8
BEGIN DESCRIPTION:
Cross Section 181623.0
END DESCRIPTION:
XS GIS Cut Line= 6
      3075806.88     13840276.94      3076781.65     13839571.22
      3077362.68     13839398.88      3077544.87     13839108.37
      3077707.36     13838901.56       3078805.4     13837815.83
#Sta/Elev= 30
  3071.6    64.5  3291.6    60.4    4385    59.1    4555    45.8  4692.9    44.2
  4752.9    35.4  4802.9    38.3  4852.9    35.3  4918.9   37.52    4920   37.18
  4959.9   32.23  4972.5   23.63  5000.3   18.35  5027.5   23.42  5041.8   30.67
  5056.1   32.74  5070.2   40.87  5073.3   42.66  5122.8   45.09  5132.6    36.7
  5225.7      38  5295.7    32.8  5385.7    30.8  5425.7    37.6  5485.7      57
  5538.7    58.2  6152.3    62.7  6342.3    60.6  6902.3    62.2  7032.3    66.9
#Mann= 5 ,-1 , 0
  3071.6      .2       0    4920      .1       0  4959.9     .06       0
  5041.8      .1       0  5070.2      .2       0
Bank Sta=4918.9,5073.3
XS Rating Curve= 0
Exp/Cntr=.3,.1