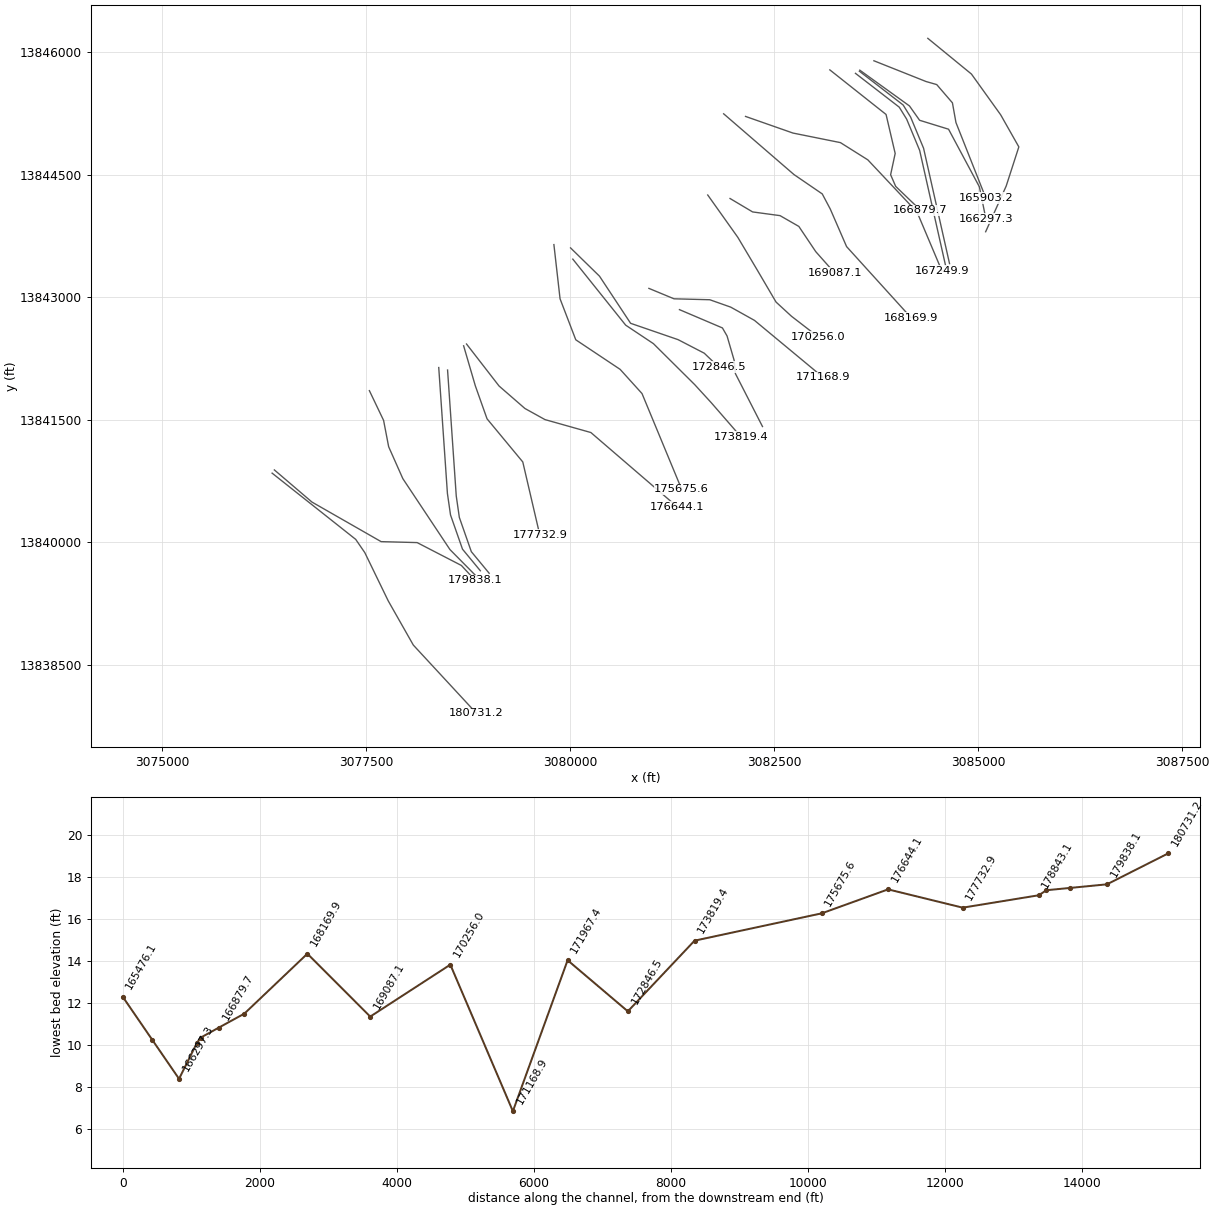
HEC-RAS study W100-00-00.prj: W100-00-00

--- W100-00-00.g01 (geometry) --- (continued)

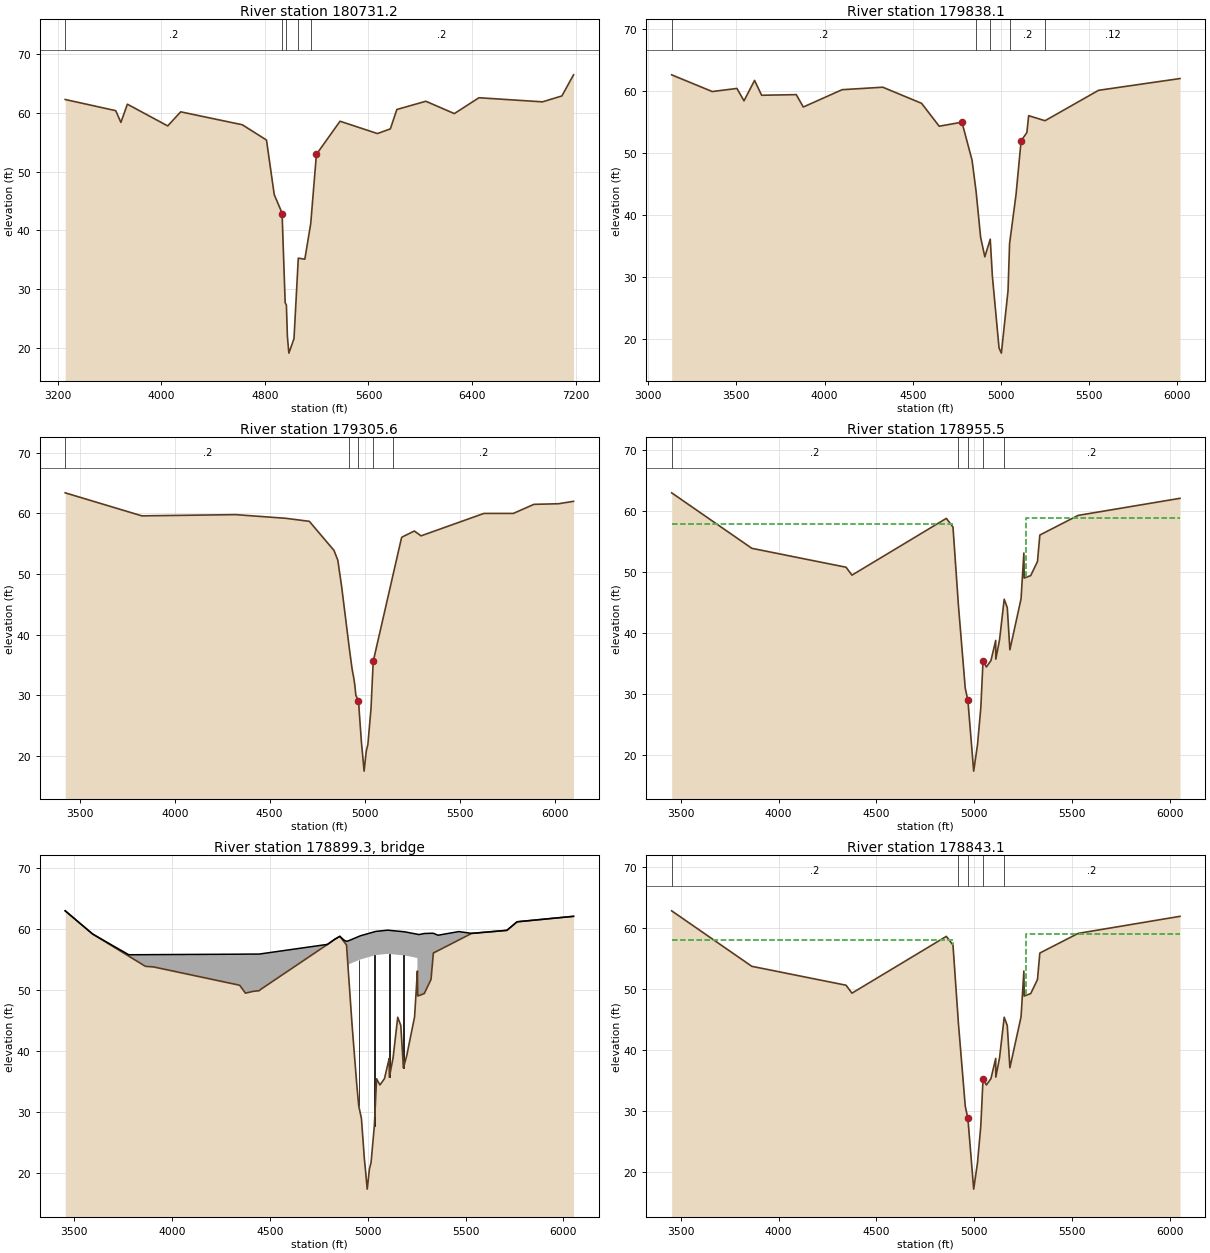
Type RM Length L Ch R = 1 ,180731.2,446.1,893.1,937.5
BEGIN DESCRIPTION:
Cross Section 180731.2
END DESCRIPTION:
XS GIS Cut Line= 6
      3076350.32     13840845.05       3077374.5     13840033.58
      3077485.78     13839871.58      3077772.36      13839281.2
      3078080.35      13838738.7       3078854.6     13837901.97
#Sta/Elev= 30
  3259.4    62.3  3649.4    60.4  3689.4    58.4  3739.4    61.5  4050.7    57.8
  4150.7    60.2  4626.5      58    4813    55.4    4873    46.1  4930.3   43.13
  4933.5   42.86  4957.3    27.7  4966.7   27.31  4974.6   21.91  4985.9   19.12
  5025.4   21.59  5058.6   35.29    5109   35.11  5154.5   41.17  5198.5   52.96
  5380.7    58.6  5669.3    56.5  5769.3    57.3  5819.3    60.6  6043.1      62
  6263.1    59.9  6453.1    62.6  6943.1    61.9  7093.1    62.9  7183.1    66.5
#Mann= 5 ,-1 , 0
  3259.4      .2       0  4930.3     .13       0  4966.7     .06       0
  5058.6     .13       0  5154.5      .2       0
Bank Sta=4933.5,5198.5
XS Rating Curve= 0
Exp/Cntr=.3,.1

Type RM Length L Ch R = 1 ,179838.1,651.3,532.5,381.5
BEGIN DESCRIPTION:
Cross Section 179838.1
END DESCRIPTION:
XS GIS Cut Line= 6
      3076377.89     13840884.44      3076838.77     13840490.52
      3077685.69       13840006.      3078126.88     13839994.19
      3078669.08     13839714.15      3078837.64     13839532.61
#Sta/Elev= 30
  3133.4    62.6  3363.4    59.9  3503.4    60.4  3543.4    58.4  3603.4    61.7
  3643.4    59.3  3839.7    59.4  3879.7    57.4  4099.7    60.2  4330.1    60.6
  4550.1      58  4650.1    54.3  4779.1   54.95  4836.6   48.79  4859.6   43.68
  4884.8   36.39  4908.8   33.21  4939.5   36.06  4951.6    30.1  4989.4   18.48
  5002.6   17.65  5040.4   27.76  5049.1   35.33  5085.6   43.24  5114.5   51.94
  5147.1   53.27  5157.3      56  5250.2   55.19  5553.7    60.1  6015.3      62
#Mann= 5 ,-1 , 0
  3133.4      .2       0  4859.6     .15       0  4939.5     .06       0
  5049.1      .2       0  5250.2     .12       0
Bank Sta=4779.1,5114.5
XS Rating Curve= 0
Exp/Cntr=.3,.1

Type RM Length L Ch R = 1 ,179305.6,425.6,350.1,318.2
BEGIN DESCRIPTION:
Cross Section 179305.6 - Interpolated
END DESCRIPTION:
XS GIS Cut Line= 6
      3077541.98     13841855.62      3077716.11     13841491.17
      3077778.16     13841168.49      3077951.91     13840777.55
        3078529.     13839908.81      3078860.69     13839573.51
#Sta/Elev= 30
  3423.5    63.4  3827.4    59.6    4321    59.8  4583.8    59.2  4708.8    58.7
  4838.8    53.9  4858.8    52.3  4878.8      48  4919.5   37.74  4933.8    34.4
  4943.8    32.7  4948.8    31.6  4953.8      30  4967.8   29.07    4983   22.37
  4997.4   17.48  5008.7   20.79    5017   21.83  5033.8   27.84  5045.2   35.57
    5150   49.91  5193.8    55.9    5197    56.1    5262    57.1    5297    56.3
    5628      60    5783      60  5891.5    61.5  6021.5    61.6  6100.1      62
#Mann= 5 ,-1 , 0
  3423.5      .2       0  4919.5     .12       0  4967.8     .06       0
  5045.2     .12       0    5150      .2       0
Bank Sta=4967.8,5045.2
XS Rating Curve= 0
Exp/Cntr=.5,.3

Type RM Length L Ch R = 1 ,178955.5,112.4,112.4,112.4
BEGIN DESCRIPTION:
Upstream Section of Bridge/Culvert/Weir
END DESCRIPTION:
XS GIS Cut Line= 5
      3078391.71     13842138.76      3078498.06     13840595.93
      3078535.89     13840333.35      3078682.68     13839913.66
       3078901.2     13839649.27
#Sta/Elev= 30
    3453      63    3863    53.9  4344.9    50.8  4374.9    49.5  4857.4   58.81
  4891.5    57.4  4919.5   44.49  4954.3   30.96  4967.8   28.96  4997.4   17.37
    5017   21.72  5033.8   27.73  5045.2   35.46  5062.4   34.45  5085.6   35.49
    5110    38.8  5110.5   35.73  5129.7   38.91    5150    44.6  5153.4   45.55
  5169.2   44.18  5182.5   37.27  5239.6   45.62    5254   53.13  5255.7   49.03
  5289.1   49.43  5323.6   51.74  5335.7   56.08  5531.6    59.3  6052.4    62.1
#Mann= 5 ,-1 , 0
    3453      .2       0  4919.5     .12       0  4967.8     .06       0
  5045.2     .12       0    5150      .2       0
#XS Ineff= 2 , 0
            4890    57.9    5265            58.9
Permanent Ineff=
       F       F
Bank Sta=4967.8,5045.2
XS Rating Curve= 0
Exp/Cntr=.5,.3

Type RM Length L Ch R = 3 ,178899.3,,,
BEGIN DESCRIPTION:
VOSS ROAD
Structure ID: WOO-62
END DESCRIPTION:
Bridge Culvert--1,0,-1,-1, 0
Deck Dist Width WeirC Skew NumUp NumDn MinLoCord MaxHiCord MaxSubmerge Is_Ogee
10,92.4,2.6,0, 33, 33, , , .95, 0, 1,1,,
    3453    3593    3778    3863  3904.9  4344.9  4374.9  4414.9  4444.9  4794.3
  4831.5  4857.4  4878.7  4891.5 4901.91    4902  4961.8  5041.6  5102.3  5188.5
 5254.09  5254.2  5255.7  5262.6  5289.1  5323.6  5335.7  5359.5  5466.1  5531.6
  5711.6  5763.6  6052.4
      63    59.2    55.8   55.81   55.82   55.89    55.9   55.91   55.91    57.5
   58.34   58.82    58.2      58   58.09   58.09    58.9   59.63   59.83   59.56
   59.16   59.16   59.15   59.11   59.28   59.32   59.32      59    59.6    59.3
    59.8    61.2    62.1
      63    59.2   55.57    53.9    53.8    50.8    49.5    49.8    49.9   57.49
   58.33   58.81   57.93    57.4    52.6   54.21   55.02   55.75   55.95   55.68
   55.28   52.65   49.03   49.11   49.43   51.74   56.08   56.47   58.22    59.3
    59.8    61.2    62.1
    3453    3593    3778    3863  3904.9  4344.9  4374.9  4414.9  4444.9  4794.3
  4831.5  4857.4  4878.7  4891.5 4901.91    4902  4961.8  5041.6  5102.3  5188.5
 5254.09  5254.2  5255.7  5262.6  5289.1  5323.6  5335.7  5359.5  5466.1  5531.6
  5711.6  5763.6  6052.4
      63    59.2    55.8   55.81   55.82   55.89    55.9   55.91   55.91    57.5
   58.34   58.82    58.2      58   58.09   58.09    58.9   59.63   59.83   59.56
   59.16   59.16   59.15   59.11   59.28   59.32   59.32      59    59.6    59.3
    59.8    61.2    62.1
   62.77   58.97   55.34   53.67   53.57   50.57   49.27   49.57   49.67   57.26
    58.1   58.58    57.7   57.17   52.37   53.98   54.79   55.52   55.72   55.45
   55.05   52.42    48.8   48.88    49.2   51.51   55.85   56.24   57.99   59.07
   59.57   60.97   61.87
Pier Skew, UpSta & Num, DnSta & Num=  ,4954.3, 2 ,4954.3, 2 , 0 , 0 , 0 ,,
     2.5     2.5
   29.77   55.94
     2.5     2.5
   29.54   55.71
Pier Skew, UpSta & Num, DnSta & Num=  ,5033.8, 2 ,5033.8, 2 , 0 , 0 , 0 ,,
     2.5     2.5
   26.28   56.69
     2.5     2.5
   26.05   56.46
Pier Skew, UpSta & Num, DnSta & Num=  ,5110.5, 2 ,5110.5, 2 , 0 , 0 , 0 ,,
     2.5     2.5
   34.94   56.93
     2.5     2.5
   34.71    56.7
Pier Skew, UpSta & Num, DnSta & Num=  ,5182.5, 2 ,5182.5, 2 , 0 , 0 , 0 ,,
     2.5     2.5
   36.41    56.7
     2.5     2.5
   36.18   56.47
Abutment Skew #Up #Dn= , 2 , 2
  4901.8  4944.1
   54.21   34.45
  4901.8  4944.1
   53.98   34.22
BR Coef= 1 , 1 , 0 ,1.25, 0 ,,,.8,0,2,0,
WSPro=,,,, 1 ,,,, 0 ,,,, 0 ,,,,-1 ,-1 ,-1 , 0 , 0 , 0 , 0 , 0
BR U #Sta/Elev= 69
    3453      63    3593    59.2    3778   55.57    3863    53.9  3904.9    53.8
  4344.9    50.8  4374.9    49.5  4414.9    49.8  4444.9    49.9    4452    50.1
  4794.3   57.49  4795.1   57.51  4795.5   57.52  4798.8   57.59  4831.5   58.33
  4841.5   58.52  4842.1   58.53  4851.4    58.7  4857.4   58.81  4878.7   57.93
  4891.5    57.4  4893.4   56.52 4901.91    52.6    4902   52.56  4919.5   44.49
  4919.7    44.4    4944   34.48  4944.1   34.45  4954.3   30.96  4961.8   29.85
  4967.8   28.96    4983   22.26    4986   21.36  4997.4   17.37  5008.7   20.68
    5017   21.72  5033.8   27.73  5041.6   33.02  5045.2   35.46  5062.4   34.45
  5085.6   35.49  5102.3   37.76    5110    38.8  5110.5   35.73  5129.7   38.91
    5150    44.6  5153.4   45.55  5169.2   44.18  5182.5   37.27  5188.5   37.96
    5199   39.18  5239.6   45.62  5253.9   53.08    5254   53.13 5254.09   52.91
  5254.2   52.65  5255.7   49.03  5262.6   49.11  5289.1   49.43  5296.8   49.95
  5323.6   51.74  5335.7   56.08  5336.2   56.09  5359.5   56.47  5466.1   58.22
  5531.6    59.3  5711.6    59.8  5763.6    61.2  6052.4    62.1
BR U #Mann= 5
    3453      .2  4919.5     .12  4967.8     .06  5045.2     .12    5150      .2
BR U Banks=4967.8,5045.2
BR D #Sta/Elev= 69
    3453   62.77    3593   58.97    3778   55.34    3863   53.67  3904.9   53.57
  4344.9   50.57  4374.9   49.27  4414.9   49.57  4444.9   49.67    4452   49.87
  4794.3   57.26  4795.1   57.28  4795.5   57.29  4798.8   57.36  4831.5    58.1
  4841.5   58.29  4842.1    58.3  4851.4   58.47  4857.4   58.58  4878.7    57.7
  4891.5   57.17  4893.4   56.29 4901.91   52.37    4902   52.33  4919.5   44.26
  4919.7   44.17    4944   34.25  4944.1   34.22  4954.3   30.73  4961.8   29.62
  4967.8   28.73    4983   22.03    4986   21.13  4997.4   17.14  5008.7   20.45
    5017   21.49  5033.8    27.5  5041.6   32.79  5045.2   35.23  5062.4   34.22
  5085.6   35.26  5102.3   37.53    5110   38.57  5110.5    35.5  5129.7   38.68
    5150   44.37  5153.4   45.32  5169.2   43.95  5182.5   37.04  5188.5   37.73
    5199   38.95  5239.6   45.39  5253.9   52.85    5254    52.9 5254.09   52.68
  5254.2   52.42  5255.7    48.8  5262.6   48.88  5289.1    49.2  5296.8   49.72
  5323.6   51.51  5335.7   55.85  5336.2   55.86  5359.5   56.24  5466.1   57.99
  5531.6   59.07  5711.6   59.57  5763.6   60.97  6052.4   61.87
BR D #Mann= 5
    3453      .2  4919.5     .12  4967.8     .06  5045.2     .12    5150      .2
BR D Banks=4967.8,5045.2
BC Design=,, 0 ,, 0 ,,,,,,
BC HTab HWMax=63

Type RM Length L Ch R = 1 ,178843.1,1110.2,1110.2,1110.2
BEGIN DESCRIPTION:
Downstream Section of Bridge/Culvert/Weir
END DESCRIPTION:
XS GIS Cut Line= 5
      3078499.86     13842108.13       3078606.2     13840565.31
      3078644.03     13840302.73      3078790.82     13839883.04
      3079009.34     13839618.65
#Sta/Elev= 30
    3453   62.76    3863   53.66  4344.9   50.56  4374.9   49.26  4857.4   58.57
  4891.5   57.16  4919.5   44.25  4954.3   30.72  4967.8   28.72  4997.4   17.13
    5017   21.48  5033.8   27.49  5045.2   35.22  5062.4   34.21  5085.6   35.25
    5110   38.56  5110.5   35.49  5129.7   38.67    5150   44.36  5153.4   45.31
  5169.2   43.94  5182.5   37.03  5239.6   45.38    5254   52.89  5255.7   48.79
  5289.1   49.19  5323.6    51.5  5335.7   55.84  5531.6   59.06  6052.4   61.86
#Mann= 5 ,-1 , 0
    3453      .2       0  4919.5     .12       0  4967.8     .06       0
  5045.2     .12       0    5150      .2       0
#XS Ineff= 2 , 0
            4890    57.9    5265            58.9
Permanent Ineff=
       F       F
Bank Sta=4967.8,5045.2
XS Rating Curve= 0
Exp/Cntr=.5,.3

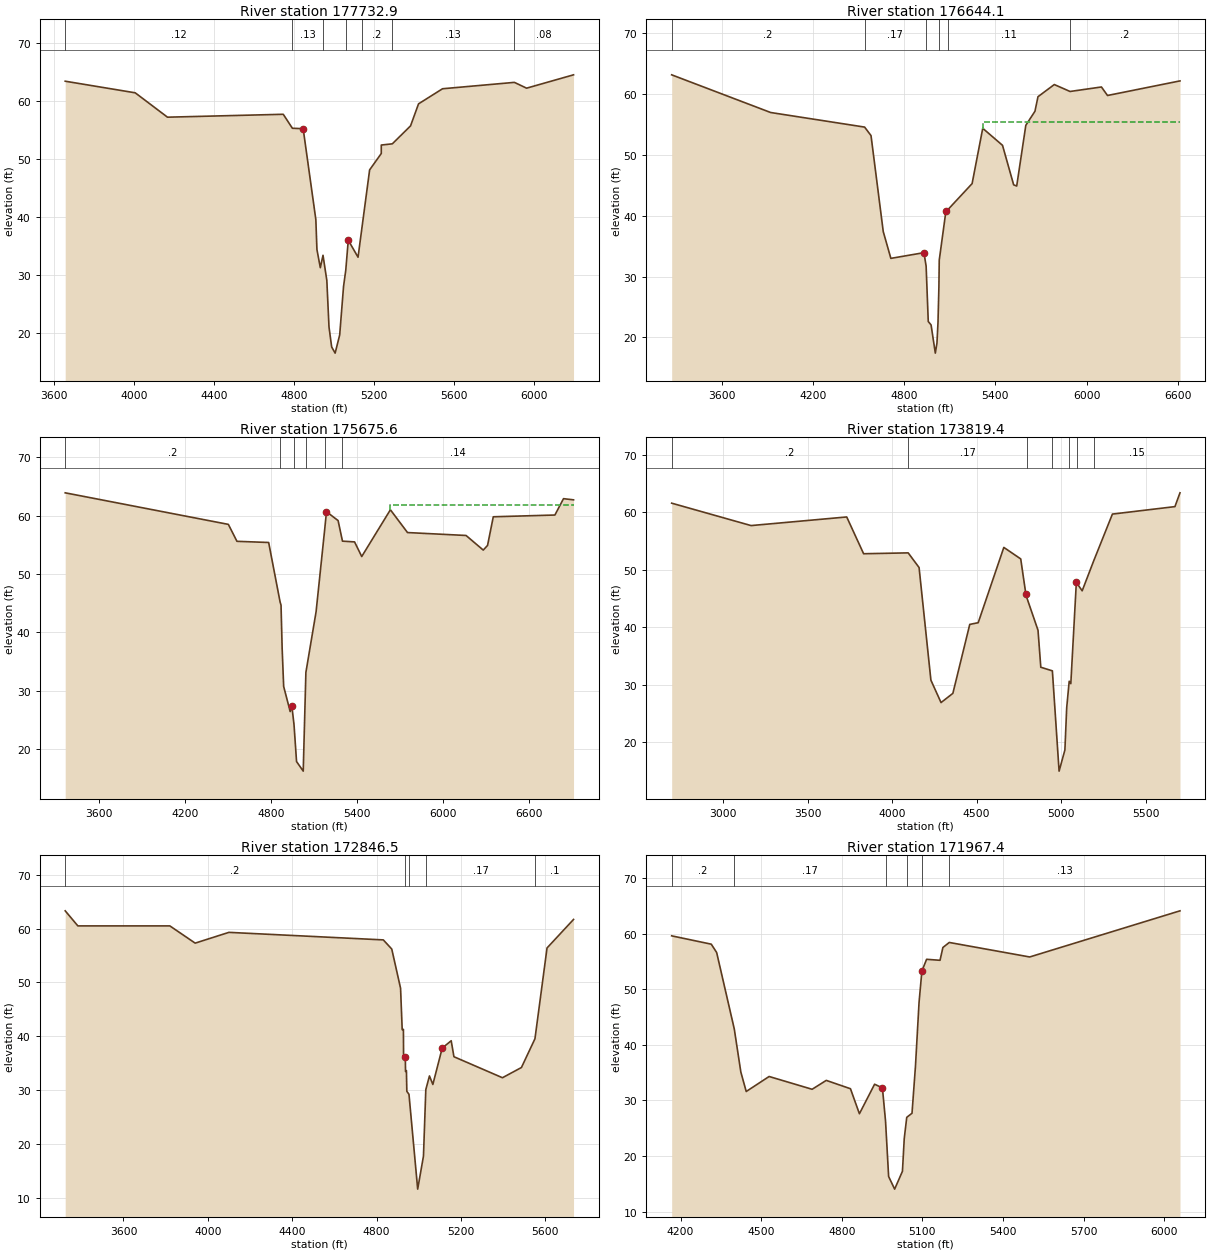
Type RM Length L Ch R = 1 ,177732.9,662.2,1088.8,1035.3
BEGIN DESCRIPTION:
Cross Section 177732.9
END DESCRIPTION:
XS GIS Cut Line= 5
      3078696.62     13842405.07      3078840.05      13841914.4
      3078983.47     13841510.54       3079421.3     13840982.13
       3079628.9     13840091.37
#Sta/Elev= 30
  3654.8    63.4  4004.8    61.4    4166    57.2  4744.6    57.7  4790.3   55.29
  4844.1   55.22  4907.5   39.55  4912.9    34.4  4929.9   31.26  4943.3    33.4
  4962.4   29.07  4973.2   21.06  4986.5   17.61  5003.9   16.54  5026.7   19.68
  5045.9   28.01  5057.2   30.88  5069.5      36  5118.4   33.07  5135.9   37.63
  5176.3   48.12  5234.5   50.94  5234.6    52.4  5289.8   52.61  5380.8    55.7
  5420.8    59.5  5540.8    62.1  5899.8    63.2  5960.8    62.2  6195.4    64.5
#Mann= 7 ,-1 , 0
  3654.8     .12       0  4790.3     .13       0  4943.3     .06       0
  5057.2     .13       0  5135.9      .2       0  5289.8     .13       0
  5899.8     .08       0
Bank Sta=4844.1,5069.5
XS Rating Curve= 0
Exp/Cntr=.3,.1

Type RM Length L Ch R = 1 ,176644.1,942,968.5,874.4
BEGIN DESCRIPTION:
Cross Section 176644.1
END DESCRIPTION:
XS GIS Cut Line= 6
      3078731.96     13842427.09      3079130.67     13841912.51
      3079447.72     13841636.98      3079693.06     13841501.11
      3080255.45     13841342.58      3081316.19     13840430.21
#Sta/Elev= 30
  3271.5    63.2  3922.5      57  4540.4    54.6  4582.5    53.2    4663    37.4
    4713      33  4930.6   33.94  4944.9   31.72    4959   22.61  4977.5   22.05
  5005.4   17.41  5016.1   19.05  5022.8   22.34  5028.9   28.26  5031.2   32.71
  5075.5   40.85  5091.8   41.12  5247.3    45.3  5317.3    54.4  5447.3    51.6
  5520.6    45.1  5540.6    44.9  5600.6    54.9  5660.6    57.2  5680.6    59.6
  5787.8    61.6  5891.5   60.46  6097.8    61.2  6137.8    59.8  6614.5    62.2
#Mann= 6 ,-1 , 0
  3271.5      .2       0  4540.4     .17       0  4944.9     .06       0
  5031.2     .13       0  5091.8     .11       0  5891.5      .2       0
#XS Ineff= 2 , 0
                            5316            55.5
Permanent Ineff=
       F       F
Bank Sta=4930.6,5075.5
XS Rating Curve= 0
Exp/Cntr=.3,.1

Type RM Length L Ch R = 1 ,175675.6,1856.2,1856.2,1856.2
BEGIN DESCRIPTION:
Cross Section 175675.6
END DESCRIPTION:
XS GIS Cut Line= 6
      3079802.52     13843644.96      3079878.01     13842980.67
       3080070.5     13842478.67      3080614.01     13842116.33
        3080882.     13841820.04      3081367.26     13840648.55
#Sta/Elev= 30
  3365.8    63.9  4504.4    58.5  4564.4    55.6  4785.7    55.4  4865.8   45.18
    4872   44.68  4879.8   37.27  4890.4   30.76    4936   26.46  4947.3   27.48
  4962.7   24.21  4980.3   17.91  5026.9   16.27  5045.5   33.16  5116.7   43.56
  5176.2    57.5  5189.1   60.67  5270.3   59.15  5300.8   55.63  5385.2    55.5
  5435.2      53  5635.2      61  5754.7    57.1  6163.3    56.6  6283.3    54.1
  6313.3    54.9  6353.3    59.8  6783.3    60.1  6843.3    62.9  6913.3    62.7
#Mann= 6 ,-1 , 0
  3365.8      .2       0  4865.8     .08       0  4962.7     .06       0
  5045.5     .12       0  5176.2     .08       0  5300.8     .14       0
#XS Ineff= 2 , 0
                            5634            61.8
Permanent Ineff=
       F       F
Bank Sta=4947.3,5189.1
XS Rating Curve= 0
Exp/Cntr=.3,.1

Type RM Length L Ch R = 1 ,173819.4,208.8,972.9,655.1
BEGIN DESCRIPTION:
Cross Section 173819.4
END DESCRIPTION:
XS GIS Cut Line= 6
      3080034.24     13843466.84      3080681.95     13842657.96
      3081021.65     13842431.49      3081527.42      13841929.5
      3081731.24     13841706.81      3082092.21     13841291.84
#Sta/Elev= 30
  2695.1    61.6  3165.1    57.7  3731.3    59.2  3831.3    52.8  4095.1   52.95
  4159.6    50.4  4229.6    30.8  4289.6    26.9  4359.6    28.5  4459.6    40.5
  4509.6    40.8  4661.3    53.9  4761.3    51.9  4791.4   45.83    4796   45.27
  4863.7   39.48  4880.1   33.05  4948.7   32.42  4988.4   14.97  5022.8   18.65
  5033.4   25.99  5048.2   30.61  5057.8   30.19  5090.5   47.81  5095.4    47.6
  5125.1   46.35  5195.1    51.7  5304.1    59.7  5674.1      61  5704.1    63.4
#Mann= 7 ,-1 , 0
  2695.1      .2       0  4095.1     .17       0    4796     .15       0
  4948.7     .06       0  5048.2     .15       0  5095.4     .09       0
  5195.1     .15       0
Bank Sta=4791.4,5090.5
XS Rating Curve= 0
Exp/Cntr=.3,.1

Type RM Length L Ch R = 1 ,172846.5,512.1,879.1,428.6
BEGIN DESCRIPTION:
Cross Section 172846.5
END DESCRIPTION:
XS GIS Cut Line= 6
      3080006.39     13843604.65      3080361.13     13843258.09
      3080742.34      13842680.6       3081323.6     13842480.56
      3081644.42     13842314.49      3081821.84     13842144.61
#Sta/Elev= 30
  3323.8    63.3  3383.8    60.5  3819.8    60.5  3939.8    57.3  4099.8    59.3
  4831.7    57.9  4871.7    56.2  4913.4   48.93  4921.2   41.22    4927   41.28
  4927.7   35.78  4934.7   36.04    4936   36.09  4936.9   33.46  4941.2   33.62
  4943.1   29.78  4953.3   29.22  4994.6   11.61    5022   17.75  5033.1   30.09
  5050.4   32.63  5066.5   31.05  5110.8    37.8  5153.4   39.17  5166.4    36.2
  5396.4    32.3  5486.4    34.2  5550.5   39.54  5607.7    56.4  5733.3    61.7
#Mann= 5 ,-1 , 0
  3323.8      .2       0  4934.7     .09       0  4953.3     .06       0
  5033.1     .17       0  5550.5      .1       0
Bank Sta=4936,5110.8
XS Rating Curve= 0
Exp/Cntr=.3,.1

Type RM Length L Ch R = 1 ,171967.4,221.5,798.5,606.2
BEGIN DESCRIPTION:
Cross Section 171967.4
END DESCRIPTION:
XS GIS Cut Line= 6
      3081340.67     13842848.14      3081867.11     13842623.99
      3081923.73     13842525.85      3082010.54     13842227.68
      3082025.64     13842065.38      3082357.79     13841416.18
#Sta/Elev= 30
    4167    59.6  4314.4    58.1  4334.4    56.6  4399.9   42.87  4424.4    35.1
  4444.4    31.6  4529.6    34.3  4689.6      32  4742.3    33.6  4832.3    32.1
  4865.6    27.6  4922.1   32.91  4951.2   32.25  4962.8   26.28  4974.3   16.31
  4996.7   14.04  5025.7   17.25  5032.4   23.12  5041.7   26.95  5061.3   27.69
  5074.1    36.1  5087.5   47.62  5098.1   53.27  5100.1   53.51  5115.6   55.38
  5165.6    55.2  5176.2    57.5  5199.9   58.41  5499.2    55.8  6058.5    64.1
#Mann= 6 ,-1 , 0
    4167      .2       0  4399.9     .17       0  4962.8     .06       0
  5041.7      .1       0  5100.1     .13       0  5199.9     .13       0
Bank Sta=4951.2,5098.1
XS Rating Curve= 0
Exp/Cntr=.3,.1

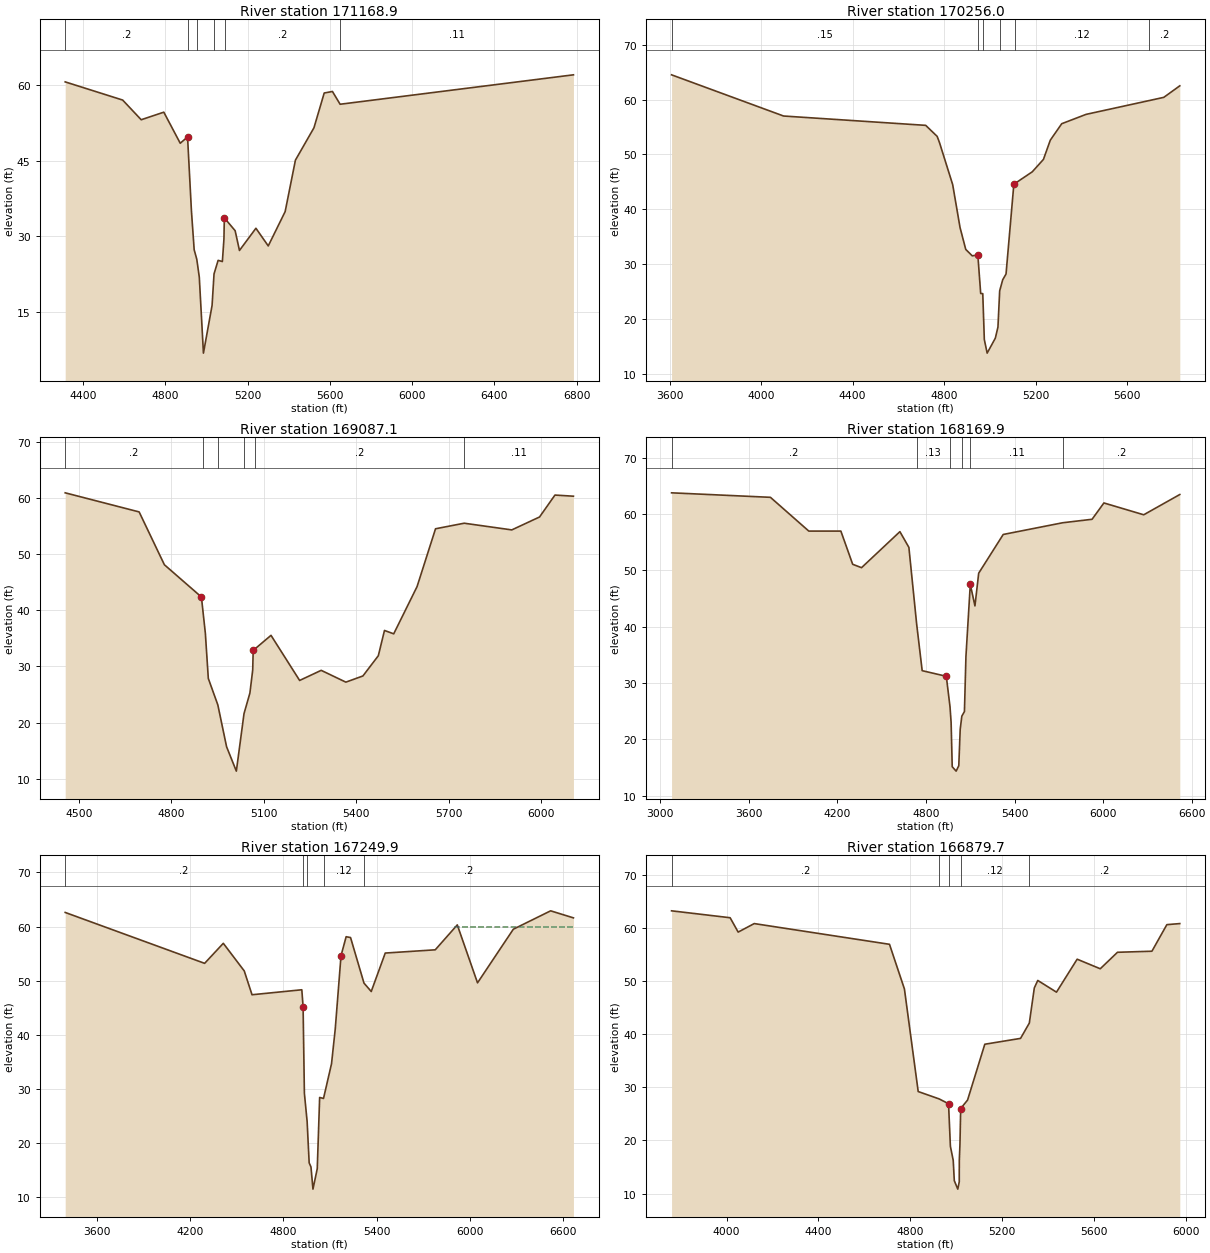
Type RM Length L Ch R = 1 ,171168.9,968.6,912.9,540.8
BEGIN DESCRIPTION:
Cross Section 171168.9
END DESCRIPTION:
XS GIS Cut Line= 6
      3080966.32     13843108.54      3081274.53     13842980.67
      3081712.36     13842969.35      3081969.02     13842878.76
      3082259.65     13842716.46      3083097.34      13842021.2
#Sta/Elev= 30
  4312.8    60.6  4592.3      57  4682.4    53.1  4792.4    54.6  4872.3   48.44
  4907.8    49.7  4908.6    49.1  4926.7   35.05    4940   27.35  4952.7   25.46
  4964.9   21.93  4985.1    6.86  5027.1   16.31  5036.6   22.55  5056.5   25.24
  5077.2   25.01  5084.8   29.47  5086.6   33.55  5089.8   33.52  5139.3   31.11
  5160.3    27.2  5240.3    31.6  5300.3    28.1  5382.5    34.9  5432.5    45.1
  5522.5    51.5  5572.5    58.4  5612.5    58.7  5649.8   56.17  6784.5      62
#Mann= 6 ,-1 , 0
  4312.8      .2       0  4908.6     .09       0  4952.7     .06       0
  5036.6     .09       0  5089.8      .2       0  5649.8     .11       0
Bank Sta=4907.8,5086.6
XS Rating Curve= 0
Exp/Cntr=.3,.1

Type RM Length L Ch R = 1 ,170256.0,998.9,1168.9,977.5
BEGIN DESCRIPTION:
Cross Section 170256.0
END DESCRIPTION:
XS GIS Cut Line= 6
      3081687.24      13844252.3      3082055.83     13843733.66
      3082293.62     13843333.58      3082523.86     13842941.04
      3082712.58     13842767.42      3083037.26     13842517.06
#Sta/Elev= 30
  3607.8    64.5  4097.8      57  4719.5    55.3  4769.5    53.3  4779.5    52.2
  4837.5   44.51  4869.7   36.69  4894.7   32.71  4923.1   31.54  4947.3   31.71
  4947.5   31.71    4960   24.69  4969.1   24.66  4975.9    16.3  4988.3   13.83
  5024.1   16.56  5035.5   18.58  5043.1   25.18  5056.4   27.19  5070.9   28.24
  5105.1    44.6  5108.1   44.67  5185.6   46.84  5234.5    49.1  5264.5    52.6
  5314.5    55.6    5421    57.3  5697.8   59.82    5761    60.4    5831    62.5
#Mann= 6 ,-1 , 0
  3607.8     .15       0  4947.3     .09       0  4969.1     .06       0
  5043.1     .09       0  5108.1     .12       0  5697.8      .2       0
Bank Sta=4947.5,5105.1
XS Rating Curve= 0
Exp/Cntr=.3,.1

Type RM Length L Ch R = 1 ,169087.1,942.5,917.2,478.6
BEGIN DESCRIPTION:
Cross Section 169087.1
END DESCRIPTION:
XS GIS Cut Line= 6
      3081960.36     13844209.59      3082237.01     13844045.05
      3082572.93     13843999.76      3082803.17     13843867.65
      3083010.76     13843558.15      3083243.28     13843296.57
#Sta/Elev= 30
    4455    60.9    4695    57.5  4776.9    48.1  4897.1   42.36  4900.7   40.54
  4909.9    35.9  4919.5   27.86  4950.4   23.15  4978.8    15.7  5010.5   11.36
  5035.4    21.6  5054.5   25.26  5063.6   29.36  5065.2   32.95  5070.5    33.1
    5123   35.53  5215.9    27.5  5285.9    29.3  5365.9    27.2  5421.3    28.3
  5471.3    31.9  5491.3    36.4  5521.3    35.8    5597    44.2    5657    54.5
    5750   55.49  5904.6    54.3  5994.6    56.6  6044.6    60.5  6104.6    60.3
#Mann= 6 ,-1 , 0
    4455      .2       0  4900.7     .15       0  4950.4     .06       0
  5035.4     .11       0  5070.5      .2       0    5750     .11       0
Bank Sta=4897.1,5065.2
XS Rating Curve= 0
Exp/Cntr=.3,.1

Type RM Length L Ch R = 1 ,168169.9,726.8,920,926.6
BEGIN DESCRIPTION:
Cross Section 168169.9
END DESCRIPTION:
XS GIS Cut Line= 6
      3081882.21      13845247.2      3082742.77     13844503.64
      3083090.02     13844265.85      3083188.15     13844080.91
       3083388.2     13843620.43      3084177.05     13842750.43
#Sta/Elev= 30
  3075.9    63.8  3745.9      63  4005.9      57  4223.2      57  4303.2    51.1
  4363.2    50.5  4623.2    56.9  4684.1    54.1  4736.8   40.46  4774.1    32.2
  4937.6    31.2  4962.8   25.77  4970.2      23  4977.7   15.13  5004.3   14.35
  5022.2   15.32  5031.8   21.77  5042.7   24.11  5060.5   24.94  5070.7   34.73
  5100.2   47.53    5101   47.43  5131.7   43.71  5157.1   49.52  5323.4    56.4
  5725.9   58.48  5925.5    59.1  6005.5      62  6275.5    59.9  6519.9    63.5
#Mann= 6 ,-1 , 0
  3075.9      .2       0  4736.8     .13       0  4962.8     .06       0
  5042.7     .13       0    5101     .11       0  5725.9      .2       0
Bank Sta=4937.6,5100.2
XS Rating Curve= 0
Exp/Cntr=.3,.1

Type RM Length L Ch R = 1 ,167249.9,527.6,370.2,304.6
BEGIN DESCRIPTION:
Cross Section 167249.9
END DESCRIPTION:
XS GIS Cut Line= 6
      3082150.19     13845215.11      3082731.45      13845011.3
      3083312.71     13844894.29      3083648.63     13844682.92
      3084252.53     13844041.28      3084554.49     13843326.03
#Sta/Elev= 30
    3398    62.6    4294    53.2    4414    56.9  4548.6    51.8  4598.6    47.4
  4918.6   48.32  4924.9    45.9  4926.8   45.17  4935.1   29.21  4952.7   23.99
  4965.8   16.35  4977.5   15.58  4990.2    11.5  5017.8   15.28  5033.2   28.43
    5058   28.25  5109.5   34.66  5133.5    41.1  5170.5   54.61  5203.5   58.12
  5231.8   57.96  5318.1   49.55  5364.7      48  5454.7    55.1  5776.1    55.7
  5917.7    60.3  6047.7    49.6  6277.7    59.5  6517.7    62.9  6664.1    61.6
#Mann= 5 ,-1 , 0
    3398      .2       0  4924.9     .12       0  4952.7     .06       0
    5058     .12       0  5318.1      .2       0
#XS Ineff= 2 , 0
                            5900              60
Permanent Ineff=
       F       F
Bank Sta=4926.8,5170.5
XS Rating Curve= 0
Exp/Cntr=.3,.1

Type RM Length L Ch R = 1 ,166879.7,235.8,266.7,341.9
BEGIN DESCRIPTION:
Cross Section 166879.7 - Interpolated
END DESCRIPTION:
XS GIS Cut Line= 6
      3083182.99     13845785.24      3083871.78     13845239.18
      3083983.47     13844761.37      3083927.63     13844500.74
      3083989.68     13844358.02      3084293.74     13844066.37
#Sta/Elev= 30
  3760.2    63.2  4015.2    61.9  4050.2    59.2  4120.2    60.8  4709.2    56.9
  4774.2    48.5  4834.2    29.2  4924.9   27.82  4966.3   26.91  4974.4   18.89
  4986.7   16.26  4991.4   12.43  5006.6   10.84    5013   12.22  5013.2   16.21
  5016.1   19.36  5019.2      26  5049.2    27.6  5124.2    38.1  5279.9    39.2
  5318.1   42.08  5339.9    48.7  5354.9    50.1  5436.4    47.9  5526.4    54.1
    5627    52.3    5702    55.4    5852    55.6    5917    60.6  5973.4    60.8
#Mann= 5 ,-1 , 0
  3760.2      .2       0  4924.9     .12       0  4966.3     .06       0
  5019.2     .12       0  5318.1      .2       0
Bank Sta=4966.3,5019.2
XS Rating Curve= 0
Exp/Cntr=.5,.3

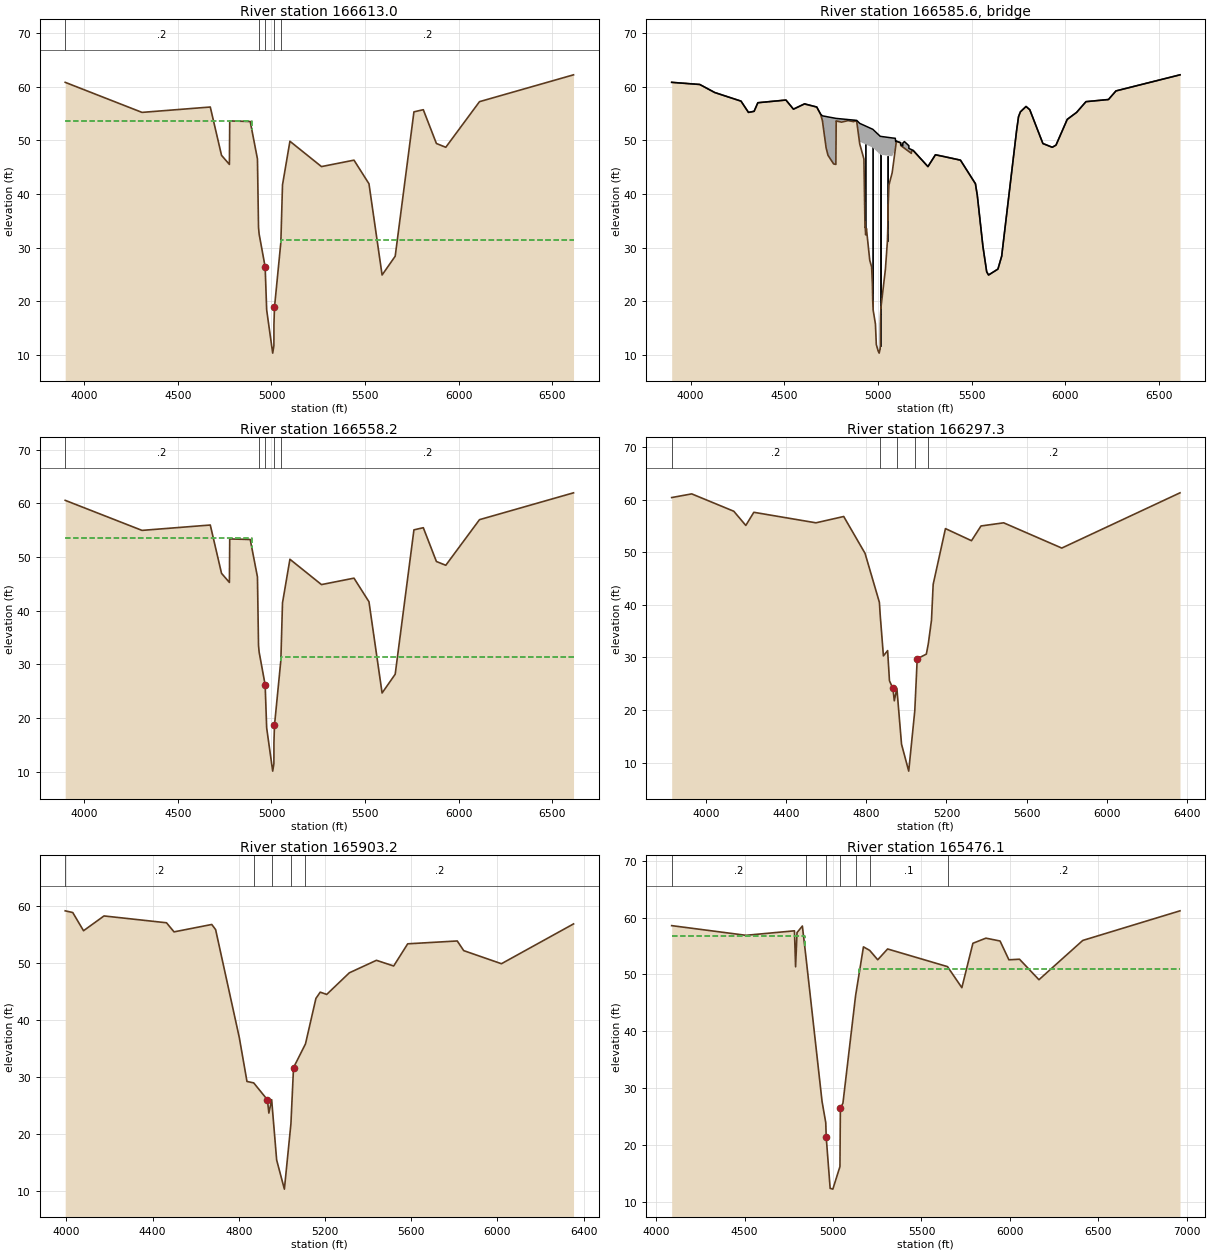
Type RM Length L Ch R = 1 ,166613.0,54.8,54.8,54.8
BEGIN DESCRIPTION:
Upstream Section of Bridge/Culvert/Weir
END DESCRIPTION:
XS GIS Cut Line= 5
      3083496.96     13845742.77      3084033.28     13845328.67
      3084124.21     13845181.57      3084283.27     13844799.21
       3084601.2     13843385.77
#Sta/Elev= 30
    3899   60.82    4309   55.22  4673.4   56.22  4733.4   47.22  4775.5   45.52
  4777.2   53.63  4886.7   53.52  4925.2   46.54  4930.9    33.8  4934.2   32.54
  4966.3   26.43  4974.4   18.41  5006.6   10.36    5013   11.74  5013.2   15.73
  5016.1   18.88  5050.1      31  5058.9   41.71  5098.5   49.84  5266.9   45.12
  5440.5   46.32  5520.5   41.92  5590.5   24.92  5660.5   28.42  5760.5   55.32
  5810.5   55.72  5880.5   49.42  5930.5   48.72  6110.5   57.22  6612.4   62.22
#Mann= 5 ,-1 , 0
    3899      .2       0  4934.2      .1       0  4966.3     .06       0
  5016.1      .1       0  5050.1      .2       0
#XS Ineff= 2 , 0
            4895    53.6    5050            31.4
Permanent Ineff=
       F       F
Bank Sta=4966.3,5016.1
XS Rating Curve= 0
Exp/Cntr=.5,.3

Type RM Length L Ch R = 3 ,166585.6,,,
BEGIN DESCRIPTION:
FARTHER POINT
Structure ID: WOO-60
END DESCRIPTION:
Bridge Culvert--1,0,-1,-1, 0
Deck Dist Width WeirC Skew NumUp NumDn MinLoCord MaxHiCord MaxSubmerge Is_Ogee
10,34.8,2.6,0, 60, 60, , , .95, 0, 1,1,,
    3899    4049    4129    4269    4309    4339    4359    4509    4549    4609
  4673.4  4693.4  4703.4  4723.4  4733.4  4763.4  4775.5  4777.2  4886.7    4903
  4972.7  5012.4  5076.1 5092.59  5094.9  5098.5    5121  5121.9  5132.3  5132.9
  5141.4  5165.1  5165.4  5178.4  5179.5  5188.3  5266.9  5306.9  5440.5  5520.5
  5530.5  5560.5  5580.5  5590.5  5640.5  5660.5  5740.5  5750.5  5760.5  5790.5
  5810.5  5880.5  5930.5  5950.5  6010.5  6060.5  6110.5  6230.5  6270.5  6612.4
    60.8    60.4    58.9    57.3    55.2    55.4      57    57.5    55.8    56.8
    56.2    54.9   54.56   54.43   54.36   54.17   54.09   54.08   53.71   53.15
   52.05   50.74   50.44   50.38   49.73   49.83   49.55   49.19   48.98   49.49
   49.76      49   48.48   48.28   48.26   48.12    45.1    47.3    46.3    41.9
    39.7    30.2    25.5    24.9      26    28.4    51.9    54.4    55.3    56.3
    55.7    49.4    48.7    49.1    53.9    55.2    57.2    57.6    59.2    62.2
    60.8    60.4    58.9    57.3    55.2    55.4      57    57.5    55.8    56.8
    56.2    54.9    53.7    48.6    47.2    45.6    45.5   53.61    53.5   49.73
   48.63   47.32   47.02   48.28   48.88   49.82   49.54   49.02   48.75   48.74
   48.52   47.91    47.9   47.57   48.02   48.08    45.1    47.3    46.3    41.9
    39.7    30.2    25.5    24.9      26    28.4    51.9    54.4    55.3    56.3
    55.7    49.4    48.7    49.1    53.9    55.2    57.2    57.6    59.2    62.2
    3899    4049    4129    4269    4309    4339    4359    4509    4549    4609
  4673.4  4693.4  4703.4  4723.4  4733.4  4763.4  4775.5  4777.2  4886.7    4903
  4972.7  5012.4  5076.1 5092.59  5094.9  5098.5    5121  5121.9  5132.3  5132.9
  5141.4  5165.1  5165.4  5178.4  5179.5  5188.3  5266.9  5306.9  5440.5  5520.5
  5530.5  5560.5  5580.5  5590.5  5640.5  5660.5  5740.5  5750.5  5760.5  5790.5
  5810.5  5880.5  5930.5  5950.5  6010.5  6060.5  6110.5  6230.5  6270.5  6612.4
    60.8    60.4    58.9    57.3    55.2    55.4      57    57.5    55.8    56.8
    56.2    54.9   54.56   54.43   54.36   54.17   54.09   54.08   53.71   53.15
   52.05   50.74   50.44   50.38   49.73   49.83   49.55   49.19   48.98   49.49
   49.76      49   48.48   48.28   48.26   48.12    45.1    47.3    46.3    41.9
    39.7    30.2    25.5    24.9      26    28.4    51.9    54.4    55.3    56.3
    55.7    49.4    48.7    49.1    53.9    55.2    57.2    57.6    59.2    62.2
   60.64   60.24   58.74   57.14   55.04   55.24   56.84   57.34   55.64   56.64
   56.04   54.74   53.54   48.44   47.04   45.44   45.34   53.45   53.34   49.57
   48.47   47.16   46.86   48.12   48.72   49.66   49.38   48.86   48.59   48.58
   48.36   47.75   47.74   47.41   47.86   47.92   44.94   47.14   46.14   41.74
   39.54   30.04   25.34   24.74   25.84   28.24   51.74   54.24   55.14   56.14
   55.54   49.24   48.54   48.94   53.74   55.04   57.04   57.44   59.04   62.04
Pier Skew, UpSta & Num, DnSta & Num=  ,4930.9, 2 ,4930.9, 2 , 0 , 0 , 0 ,,
       1       1
   32.79   50.25
       1       1
   32.63   50.09
Pier Skew, UpSta & Num, DnSta & Num=  ,4932.4, 2 ,4932.4, 2 , 0 , 0 , 0 ,,
     1.4     1.4
    32.3   50.22
     1.4     1.4
   32.14   50.06
Pier Skew, UpSta & Num, DnSta & Num=  ,4934.4, 2 ,4934.4, 2 , 0 , 0 , 0 ,,
       1       1
   31.53   50.19
       1       1
   31.37   50.02
Pier Skew, UpSta & Num, DnSta & Num=  ,4970.4, 2 ,4970.4, 2 , 0 , 0 , 0 ,,
       1       1
   21.39   49.67
       1       1
   21.23   49.51
Pier Skew, UpSta & Num, DnSta & Num=  ,4972.2, 2 ,4972.2, 2 , 0 , 0 , 0 ,,
     1.4     1.4
   18.61   49.65
     1.4     1.4
   18.45   49.49
Pier Skew, UpSta & Num, DnSta & Num=  ,4974.4, 2 ,4974.4, 2 , 0 , 0 , 0 ,,
       1       1
   17.28   49.59
       1       1
   17.12   49.43
Pier Skew, UpSta & Num, DnSta & Num=  ,5011.2, 2 ,5011.2, 2 , 0 , 0 , 0 ,,
       1       1
   10.01   48.38
       1       1
    9.85   48.22
Pier Skew, UpSta & Num, DnSta & Num=  ,5013, 2 ,5013, 2 , 0 , 0 , 0 ,,
     1.4     1.4
   10.48   48.32
     1.4     1.4
   10.32   48.16
Pier Skew, UpSta & Num, DnSta & Num=  ,5014.4, 2 ,5014.4, 2 , 0 , 0 , 0 ,,
       1       1
   15.74   48.31
       1       1
   15.58   48.15
Pier Skew, UpSta & Num, DnSta & Num=  ,5050.6, 2 ,5050.6, 2 , 0 , 0 , 0 ,,
       1       1
   29.98    48.1
       1       1
   29.82   47.94
Pier Skew, UpSta & Num, DnSta & Num=  ,5052.6, 2 ,5052.6, 2 , 0 , 0 , 0 ,,
     1.4     1.4
   31.75    48.1
     1.4     1.4
   31.59   47.94
Pier Skew, UpSta & Num, DnSta & Num=  ,5054.4, 2 ,5054.4, 2 , 0 , 0 , 0 ,,
       1       1
    35.6   48.09
       1       1
   35.44   47.93
Abutment Skew #Up #Dn= , 2 , 2
  4891.7  4925.2
   52.16   46.52
  4891.7  4925.2
      52   46.36
Abutment Skew #Up #Dn= , 2 , 2
  5076.1 5092.79
   43.97   48.28
  5076.1 5092.79
   43.81   48.12
BR Coef= 1 , 1 , 0 ,1.25, 0 ,,,.8,0,2,0,
WSPro=,,,, 1 ,,,, 0 ,,,, 0 ,,,,-1 ,-1 ,-1 , 0 , 0 , 0 , 0 , 0
BR U #Sta/Elev= 116
    3899    60.8    4049    60.4    4129    58.9    4269    57.3    4309    55.2
    4339    55.4    4359      57    4509    57.5    4549    55.8    4609    56.8
  4613.4    56.7  4673.4    56.2  4693.4    54.9  4696.8   54.49  4703.4    53.7
  4723.4    48.6  4733.4    47.2  4763.4    45.6  4775.5    45.5  4777.2   53.61
  4777.4    53.6  4778.1   53.59  4803.8    53.4  4805.8   53.38  4837.6   53.64
  4841.2   53.67  4865.3   53.51  4871.3   53.47  4871.7   53.67 4884.89   53.52
    4885   53.52 4885.11   53.52  4886.7    53.5 4891.81   52.19  4891.9   52.16
    4903   49.31  4905.3   49.02  4925.1   46.53  4925.2   46.52  4930.9   33.78
  4932.4    33.8  4934.2   32.52  4934.4   32.38  4938.5   33.59  4943.7   31.85
  4956.3   27.65  4966.3   26.41  4970.4   23.24  4972.2   20.17  4972.7   19.77
  4974.4   18.39  4986.7   15.76  4991.4   11.93  5001.1   10.75  5006.6   10.34
  5011.2   11.09  5012.4   11.51    5013   11.72  5013.2   15.71  5014.4   17.48
  5016.1   18.86  5039.8   25.93  5048.4   30.14  5050.1   30.98  5050.6   31.22
  5052.6   33.57  5054.4   37.77  5058.9   41.69    5076   43.94  5076.1   43.97
 5092.59   48.28  5092.7    48.3  5092.8   48.33  5094.9   48.88  5098.5   49.82
 5099.29   49.81  5099.4   49.81 5099.51   49.81    5121   49.54  5121.9   49.02
  5132.3   48.75  5132.9   48.74  5141.4   48.52  5165.1   47.91  5165.4    47.9
  5178.4   47.57  5179.5   48.02  5188.3   48.08  5188.5   48.07  5206.8   47.38
  5207.8   47.34  5266.9    45.1  5306.9    47.3  5350.5      47  5440.5    46.3
  5520.5    41.9  5530.5    39.7  5560.5    30.2  5580.5    25.5  5590.5    24.9
  5640.5      26  5660.5    28.4  5740.5    51.9  5750.5    54.4  5760.5    55.3
  5790.5    56.3  5810.5    55.7  5880.5    49.4  5930.5    48.7  5950.5    49.1
  6010.5    53.9  6060.5    55.2  6110.5    57.2  6230.5    57.6  6270.5    59.2
  6612.4    62.2
BR U #Mann= 5
    3899      .2  4934.2      .1  4966.3     .06  5016.1      .1  5050.1      .2
BR U Banks=4966.3,5016.1
BR D #Sta/Elev= 116
    3899   60.64    4049   60.24    4129   58.74    4269   57.14    4309   55.04
    4339   55.24    4359   56.84    4509   57.34    4549   55.64    4609   56.64
  4613.4   56.54  4673.4   56.04  4693.4   54.74  4696.8   54.33  4703.4   53.54
  4723.4   48.44  4733.4   47.04  4763.4   45.44  4775.5   45.34  4777.2   53.45
  4777.4   53.44  4778.1   53.43  4803.8   53.24  4805.8   53.22  4837.6   53.48
  4841.2   53.51  4865.3   53.35  4871.3   53.31  4871.7   53.51 4884.89   53.36
    4885   53.36 4885.11   53.36  4886.7   53.34 4891.81   52.03  4891.9      52
    4903   49.15  4905.3   48.86  4925.1   46.37  4925.2   46.36  4930.9   33.62
  4932.4   33.64  4934.2   32.36  4934.4   32.22  4938.5   33.43  4943.7   31.69
  4956.3   27.49  4966.3   26.25  4970.4   23.08  4972.2   20.01  4972.7   19.61
  4974.4   18.23  4986.7    15.6  4991.4   11.77  5001.1   10.59  5006.6   10.18
  5011.2   10.93  5012.4   11.35    5013   11.56  5013.2   15.55  5014.4   17.32
  5016.1    18.7  5039.8   25.77  5048.4   29.98  5050.1   30.82  5050.6   31.06
  5052.6   33.41  5054.4   37.61  5058.9   41.53    5076   43.78  5076.1   43.81
 5092.59   48.12  5092.7   48.14  5092.8   48.17  5094.9   48.72  5098.5   49.66
 5099.29   49.65  5099.4   49.65 5099.51   49.65    5121   49.38  5121.9   48.86
  5132.3   48.59  5132.9   48.58  5141.4   48.36  5165.1   47.75  5165.4   47.74
  5178.4   47.41  5179.5   47.86  5188.3   47.92  5188.5   47.91  5206.8   47.22
  5207.8   47.18  5266.9   44.94  5306.9   47.14  5350.5   46.84  5440.5   46.14
  5520.5   41.74  5530.5   39.54  5560.5   30.04  5580.5   25.34  5590.5   24.74
  5640.5   25.84  5660.5   28.24  5740.5   51.74  5750.5   54.24  5760.5   55.14
  5790.5   56.14  5810.5   55.54  5880.5   49.24  5930.5   48.54  5950.5   48.94
  6010.5   53.74  6060.5   55.04  6110.5   57.04  6230.5   57.44  6270.5   59.04
  6612.4   62.04
BR D #Mann= 5
    3899      .2  4934.2      .1  4966.3     .06  5016.1      .1  5050.1      .2
BR D Banks=4966.3,5016.1
BC Design=,, 0 ,, 0 ,,,,,,
BC HTab HWMax=62.22

Type RM Length L Ch R = 1 ,166558.2,260.9,260.9,260.9
BEGIN DESCRIPTION:
Downstream Section of Bridge/Culvert/Weir
END DESCRIPTION:
XS GIS Cut Line= 5
      3083545.01     13845769.12      3084081.32     13845355.01
      3084172.25     13845207.91      3084331.31     13844825.55
      3084649.25     13843412.12
#Sta/Elev= 30
    3899   60.57    4309   54.97  4673.4   55.97  4733.4   46.97  4775.5   45.27
  4777.2   53.38  4886.7   53.27  4925.2   46.29  4930.9   33.55  4934.2   32.29
  4966.3   26.18  4974.4   18.16  5006.6   10.11    5013   11.49  5013.2   15.48
  5016.1   18.63  5050.1   30.75  5058.9   41.46  5098.5   49.59  5266.9   44.87
  5440.5   46.07  5520.5   41.67  5590.5   24.67  5660.5   28.17  5760.5   55.07
  5810.5   55.47  5880.5   49.17  5930.5   48.47  6110.5   56.97  6612.4   61.97
#Mann= 5 ,-1 , 0
    3899      .2       0  4934.2      .1       0  4966.3     .06       0
  5016.1      .1       0  5050.1      .2       0
#XS Ineff= 2 , 0
            4895    53.5    5050            31.4
Permanent Ineff=
       F       F
Bank Sta=4966.3,5016.1
XS Rating Curve= 0
Exp/Cntr=.5,.3

Type RM Length L Ch R = 1 ,166297.3,481,394.1,287.3
BEGIN DESCRIPTION:
Cross Section 166297.3
END DESCRIPTION:
XS GIS Cut Line= 6
       3083550.1     13845781.79      3084158.56     13845343.49
      3084282.73     13845167.93      3084637.52     13845058.48
      3085014.96     13844352.66      3085094.23      13843963.9
#Sta/Elev= 30
  3828.9    60.4  3928.9    61.1  4138.9    57.8  4198.9    55.1  4238.9    57.6
  4548.9    55.6  4687.5    56.8  4793.9    49.8  4865.5   40.49  4869.5   38.12
  4885.6    30.3  4906.6   31.31  4915.8   25.57    4933   24.12  4939.9   21.77
  4952.8   24.13    4976   13.52  5011.9     8.4  5042.2   19.89  5054.3   29.76
  5099.8   30.64  5109.8   32.64  5125.5    37.1  5133.9    43.9  5195.2    54.5
  5325.2    52.2  5372.6      55  5485.7    55.6  5775.7    50.8  6365.7    61.3
#Mann= 5 ,-1 , 0
  3828.9      .2       0  4869.5     .15       0  4952.8     .06       0
  5042.2     .15       0  5109.8      .2       0
Bank Sta=4933,5054.3
XS Rating Curve= 0
Exp/Cntr=.3,.1

Type RM Length L Ch R = 1 ,165903.2,423.1,427.1,433.3
BEGIN DESCRIPTION:
Cross Section 165903.2 - Interpolated
END DESCRIPTION:
XS GIS Cut Line= 6
      3083722.85     13845896.94        3084362.     13845642.52
      3084492.31     13845605.29      3084684.67      13845381.9
      3084728.11     13845139.89      3085094.22      13844215.3
#Sta/Elev= 30
  3994.9    59.2  4029.9    58.9  4079.9    55.7  4174.9    58.3  4464.9    57.1
  4499.9    55.5  4674.9    56.8  4692.8    55.9  4802.8    36.9  4838.3    29.2
  4869.5   28.95    4933   25.99  4939.9   23.64  4952.8      26    4976   15.39
  5011.9   10.27  5042.2   21.76  5054.3   31.63  5109.8   35.81  5158.2    43.8
  5178.2    44.9  5208.2    44.5  5313.2    48.3    5439    50.5    5519    49.5
    5584    53.4    5814    53.9    5844    52.2    6019    49.9  6353.5    56.9
#Mann= 5 ,-1 , 0
  3994.9      .2       0  4869.5     .15       0  4952.8     .06       0
  5042.2     .15       0  5109.8      .2       0
Bank Sta=4933,5054.3
XS Rating Curve= 0
Exp/Cntr=.5,.3

Type RM Length L Ch R = 1 ,165476.1,96,96,96
BEGIN DESCRIPTION:
Upstream Section of Bridge/Culvert/Weir
END DESCRIPTION:
XS GIS Cut Line= 6
      3084383.32     13846171.81      3084917.94     13845734.05
      3085275.73     13845235.07      3085498.42     13844841.85
      3085343.77     13844363.14       3085091.9     13843802.39
#Sta/Elev= 30
  4087.4   58.58  4507.4   56.88  4781.8   57.67  4788.2   51.35  4796.4   57.36
  4826.6   58.51  4847.7   52.83  4937.9    27.7  4958.9   23.97  4961.5   21.42
  4983.7   12.44  4998.9    12.3  5039.1   16.26  5041.5   26.48    5056    27.4
  5127.5   46.27    5172   54.85  5207.4   54.23  5252.8   52.58  5308.6   54.48
  5647.4   51.38  5728.6   47.68    5791   55.48  5864.6   56.38  5944.6   55.88
  5994.6   52.58  6054.6   52.68  6164.6   49.08  6412.4   55.98  6962.3   61.18
#Mann= 7 ,-1 , 0
  4087.4      .2       0  4847.7     .11       0  4961.5     .06       0
  5041.5     .11       0  5127.5      .2       0  5207.4      .1       0
  5647.4      .2       0
#XS Ineff= 2 , 0
            4840    56.8  5148.5            50.9
Permanent Ineff=
       F       F
Bank Sta=4961.5,5041.5
XS Rating Curve= 0
Exp/Cntr=.5,.3