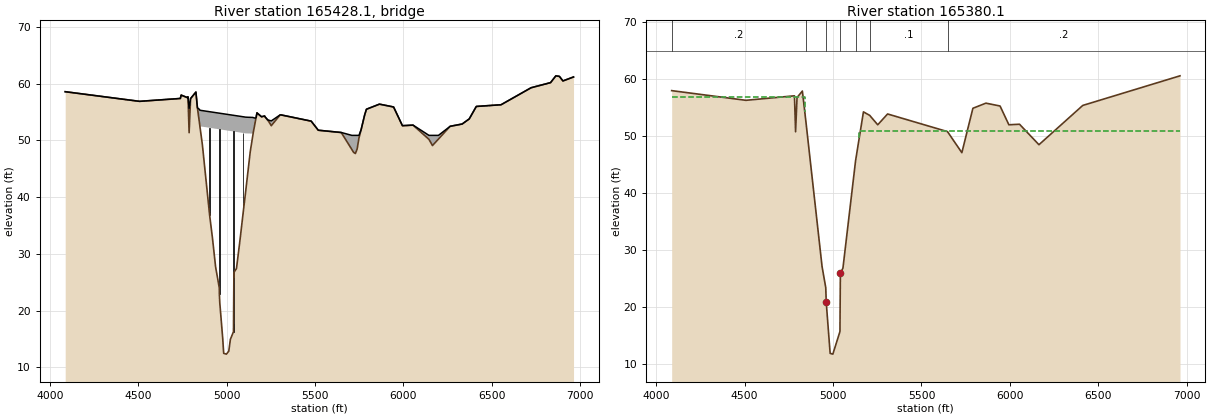
HEC-RAS study W100-00-00.prj: W100-00-00

--- W100-00-00.g01 (geometry) --- (continued)

Type RM Length L Ch R = 3 ,165428.1,,,
BEGIN DESCRIPTION:
CHIMNEY ROCK
Structure ID: WOO-59
END DESCRIPTION:
Bridge Culvert--1,0,-1,-1, 0
Deck Dist Width WeirC Skew NumUp NumDn MinLoCord MaxHiCord MaxSubmerge Is_Ogee
10,76,2.6,0, 56, 56, , , .95, 0, 1,1,,
  4087.4  4507.4  4738.6  4743.4  4780.2  4781.8  4788.2  4796.4  4826.6  4835.2
  4846.9  4849.2  5108.8 5148.59  5148.7  5151.5 5163.09  5166.9    5172  5197.8
  5215.1  5218.8  5233.8  5235.1  5252.8  5302.8  5308.6  5478.6  5518.6  5648.6
  5708.5  5718.6  5728.6  5738.6  5748.6    5761    5781    5791  5864.6  5944.6
  5994.6  6054.6  6144.6  6164.6  6198.5  6264.6  6332.4  6372.4  6412.4  6552.4
  6722.4  6832.4  6862.4  6882.4  6902.4  6962.3
    58.6    56.9   57.41   58.01   57.54    57.7   55.67   57.39   58.54   55.76
   55.47   55.33   54.11   54.06   54.06   54.03   53.93   54.04   54.88   54.18
   54.32   54.12   53.62   53.61   53.45   54.51   54.51   53.41   51.81   51.41
    50.9    50.9    50.9    50.9    50.9   51.91   54.51   55.51   56.41   55.91
   52.61   52.71    50.9    50.9    50.9    52.5    52.9    53.8      56    56.3
    59.3    60.2    61.4    61.3    60.5    61.2
    58.6    56.9    57.4      58   57.53   57.69   51.37   57.38   58.53   55.75
   53.04    52.5   51.25    51.2   50.93   51.48    53.4   54.03   54.87   54.17
   54.31   54.11   53.52   53.52    52.6    54.5    54.5    53.4    51.8    51.4
   48.41    47.9    47.7    48.5    50.4    51.9    54.5    55.5    56.4    55.9
    52.6    52.7    50.2    49.1   50.25    52.5    52.9    53.8      56    56.3
    59.3    60.2    61.4    61.3    60.5    61.2
  4087.4  4507.4  4738.6  4743.4  4780.2  4781.8  4788.2  4796.4  4826.6  4835.2
  4846.9  4849.2  5108.8 5148.59  5148.7  5151.5 5163.09  5166.9    5172  5197.8
  5215.1  5218.8  5233.8  5235.1  5252.8  5302.8  5308.6  5478.6  5518.6  5648.6
  5708.5  5718.6  5728.6  5738.6  5748.6    5761    5781    5791  5864.6  5944.6
  5994.6  6054.6  6144.6  6164.6  6198.5  6264.6  6332.4  6372.4  6412.4  6552.4
  6722.4  6832.4  6862.4  6882.4  6902.4  6962.3
    58.6    56.9   57.41   58.01   57.54    57.7   55.67   57.39   58.54   55.76
   55.47   55.33   54.11   54.06   54.06   54.03   53.93   54.04   54.88   54.18
   54.32   54.12   53.62   53.61   53.45   54.51   54.51   53.41   51.81   51.41
    50.9    50.9    50.9    50.9    50.9   51.91   54.51   55.51   56.41   55.91
   52.61   52.71    50.9    50.9    50.9    52.5    52.9    53.8      56    56.3
    59.3    60.2    61.4    61.3    60.5    61.2
   58.01   56.31   56.81   57.41   56.94    57.1   50.78   56.79   57.94   55.16
   52.45   51.91   50.66   50.61   50.34   50.89   52.81   53.44   54.28   53.58
   53.72   53.52   52.93   52.93   52.01   53.91   53.91   52.81   51.21   50.81
   47.82   47.31   47.11   47.91   49.81   51.31   53.91   54.91   55.81   55.31
   52.01   52.11   49.61   48.51   49.66   51.91   52.31   53.21   55.41   55.71
   58.71   59.61   60.81   60.71   59.91   60.61
Pier Skew, UpSta & Num, DnSta & Num=  ,4904.1, 2 ,4904.1, 2 , 0 , 0 , 0 ,,
     2.5     2.5
   35.55   53.24
     2.5     2.5
   34.96   52.65
Pier Skew, UpSta & Num, DnSta & Num=  ,4959.3, 2 ,4959.3, 2 , 0 , 0 , 0 ,,
     2.5     2.5
    21.1   52.99
     2.5     2.5
   20.52    52.4
Pier Skew, UpSta & Num, DnSta & Num=  ,5039.1, 2 ,5039.1, 2 , 0 , 0 , 0 ,,
     2.5     2.5
   15.18   52.61
     2.5     2.5
   14.59   52.02
Pier Skew, UpSta & Num, DnSta & Num=  ,5093.7, 2 ,5093.7, 2 , 0 , 0 , 0 ,,
     2.5     2.5
   35.88   52.34
     2.5     2.5
   35.29   51.75
Abutment Skew #Up #Dn= , 2 , 2
    4849  4958.9
    52.5   23.99
    4849  4958.9
   51.91    23.4
Abutment Skew #Up #Dn= , 2 , 2
  5042.5 5148.79
   26.76    51.2
  5042.5 5148.79
   26.17   50.61
BR Coef= 1 , 1 , 0 ,1.25, 0 ,,,.8,0,2,0,
WSPro=,,,, 1 ,,,, 0 ,,,, 0 ,,,,-1 ,-1 ,-1 , 0 , 0 , 0 , 0 , 0
BR U #Sta/Elev= 100
  4087.4    58.6  4507.4    56.9  4558.5   57.01  4737.4    57.4  4738.6    57.4
  4743.4      58  4743.6   57.98  4744.4   57.97  4780.2   57.53  4780.9    57.6
  4781.8   57.69  4788.2   51.37  4796.4   57.38 4817.69   58.19  4817.8   58.19
 4817.91    58.2  4826.6   58.53  4835.2   55.75  4846.9   53.04  4847.7   52.85
    4849   52.55 4849.11   52.52  4849.2    52.5  4863.1   49.28  4904.1   36.86
  4920.3   32.78  4937.9   27.72  4958.8   24.01  4958.9   23.99  4959.3   22.98
  4961.5   21.44  4976.6   15.71  4978.3   15.07  4983.7   12.46  4998.9   12.32
  5012.5   12.84  5021.6   14.93  5039.1   16.28  5041.5    26.5  5042.4   26.76
  5042.5   26.76    5056   27.42  5056.6   27.57  5075.9   32.42  5093.7   37.22
  5108.8   41.21  5111.4   41.92  5127.5   46.29  5133.7   47.97 5148.59   50.91
  5148.7   50.93  5148.8   50.95  5151.5   51.48 5163.09    53.4  5163.2   53.41
 5163.31   53.43  5166.9   54.03    5172   54.87  5173.1   54.81  5197.8   54.17
  5207.4   54.25  5215.1   54.31  5218.8   54.11  5233.8   53.52  5235.1   53.52
  5237.6   53.39  5252.8    52.6  5302.8    54.5  5308.6    54.5  5424.9   53.75
  5478.6    53.4  5518.6    51.8  5647.4    51.4  5648.6    51.4  5708.5   48.41
  5718.6    47.9  5728.6    47.7  5738.6    48.5  5748.6    50.4    5761    51.9
    5781    54.5    5791    55.5  5864.6    56.4  5944.6    55.9  5994.6    52.6
  6054.6    52.7  6144.6    50.2  6164.6    49.1  6198.5   50.25  6264.6    52.5
  6332.4    52.9  6372.4    53.8  6412.4      56  6552.4    56.3  6722.4    59.3
  6832.4    60.2  6862.4    61.4  6882.4    61.3  6902.4    60.5  6962.3    61.2
BR U #Mann= 7
  4087.4      .2  4847.7     .11  4961.5     .06  5041.5     .11  5127.5      .2
  5207.4      .1  5647.4      .2
BR U Banks=4961.5,5041.5
BR D #Sta/Elev= 100
  4087.4   58.01  4507.4   56.31  4558.5   56.42  4737.4   56.81  4738.6   56.81
  4743.4   57.41  4743.6   57.39  4744.4   57.38  4780.2   56.94  4780.9   57.01
  4781.8    57.1  4788.2   50.78  4796.4   56.79 4817.69    57.6  4817.8    57.6
 4817.91   57.61  4826.6   57.94  4835.2   55.16  4846.9   52.45  4847.7   52.26
    4849   51.96 4849.11   51.93  4849.2   51.91  4863.1   48.69  4904.1   36.27
  4920.3   32.19  4937.9   27.13  4958.8   23.42  4958.9    23.4  4959.3   22.39
  4961.5   20.85  4976.6   15.12  4978.3   14.48  4983.7   11.87  4998.9   11.73
  5012.5   12.25  5021.6   14.34  5039.1   15.69  5041.5   25.91  5042.4   26.17
  5042.5   26.17    5056   26.83  5056.6   26.98  5075.9   31.83  5093.7   36.63
  5108.8   40.62  5111.4   41.33  5127.5    45.7  5133.7   47.38 5148.59   50.32
  5148.7   50.34  5148.8   50.36  5151.5   50.89 5163.09   52.81  5163.2   52.82
 5163.31   52.84  5166.9   53.44    5172   54.28  5173.1   54.22  5197.8   53.58
  5207.4   53.66  5215.1   53.72  5218.8   53.52  5233.8   52.93  5235.1   52.93
  5237.6    52.8  5252.8   52.01  5302.8   53.91  5308.6   53.91  5424.9   53.16
  5478.6   52.81  5518.6   51.21  5647.4   50.81  5648.6   50.81  5708.5   47.82
  5718.6   47.31  5728.6   47.11  5738.6   47.91  5748.6   49.81    5761   51.31
    5781   53.91    5791   54.91  5864.6   55.81  5944.6   55.31  5994.6   52.01
  6054.6   52.11  6144.6   49.61  6164.6   48.51  6198.5   49.66  6264.6   51.91
  6332.4   52.31  6372.4   53.21  6412.4   55.41  6552.4   55.71  6722.4   58.71
  6832.4   59.61  6862.4   60.81  6882.4   60.71  6902.4   59.91  6962.3   60.61
BR D #Mann= 7
  4087.4      .2  4847.7     .11  4961.5     .06  5041.5     .11  5127.5      .2
  5207.4      .1  5647.4      .2
BR D Banks=4961.5,5041.5
BC Design=,, 0 ,, 0 ,,,,,,
BC HTab HWMax=61.38

Type RM Length L Ch R = 1 ,165380.1,824.9,824.9,824.9
BEGIN DESCRIPTION:
Downstream Section of Bridge/Culvert/Weir
END DESCRIPTION:
XS GIS Cut Line= 6
      3084479.25     13846168.12      3085013.86     13845730.37
      3085371.65     13845231.39      3085594.34     13844838.17
      3085439.69     13844359.46      3085187.83      13843798.7
#Sta/Elev= 30
  4087.4   57.97  4507.4   56.27  4781.8   57.06  4788.2   50.74  4796.4   56.75
  4826.6    57.9  4847.7   52.22  4937.9   27.09  4958.9   23.36  4961.5   20.81
  4983.7   11.83  4998.9   11.69  5039.1   15.65  5041.5   25.87    5056   26.79
  5127.5   45.66    5172   54.24  5207.4   53.62  5252.8   51.97  5308.6   53.87
  5647.4   50.77  5728.6   47.07    5791   54.87  5864.6   55.77  5944.6   55.27
  5994.6   51.97  6054.6   52.07  6164.6   48.47  6412.4   55.37  6962.3   60.57
#Mann= 7 ,-1 , 0
  4087.4      .2       0  4847.7     .11       0  4961.5     .06       0
  5041.5     .11       0  5127.5      .2       0  5207.4      .1       0
  5647.4      .2       0
#XS Ineff= 2 , 0
            4840    56.8  5148.5            50.9
Permanent Ineff=
       F       F
Bank Sta=4961.5,5041.5
XS Rating Curve= 0
Exp/Cntr=.5,.3