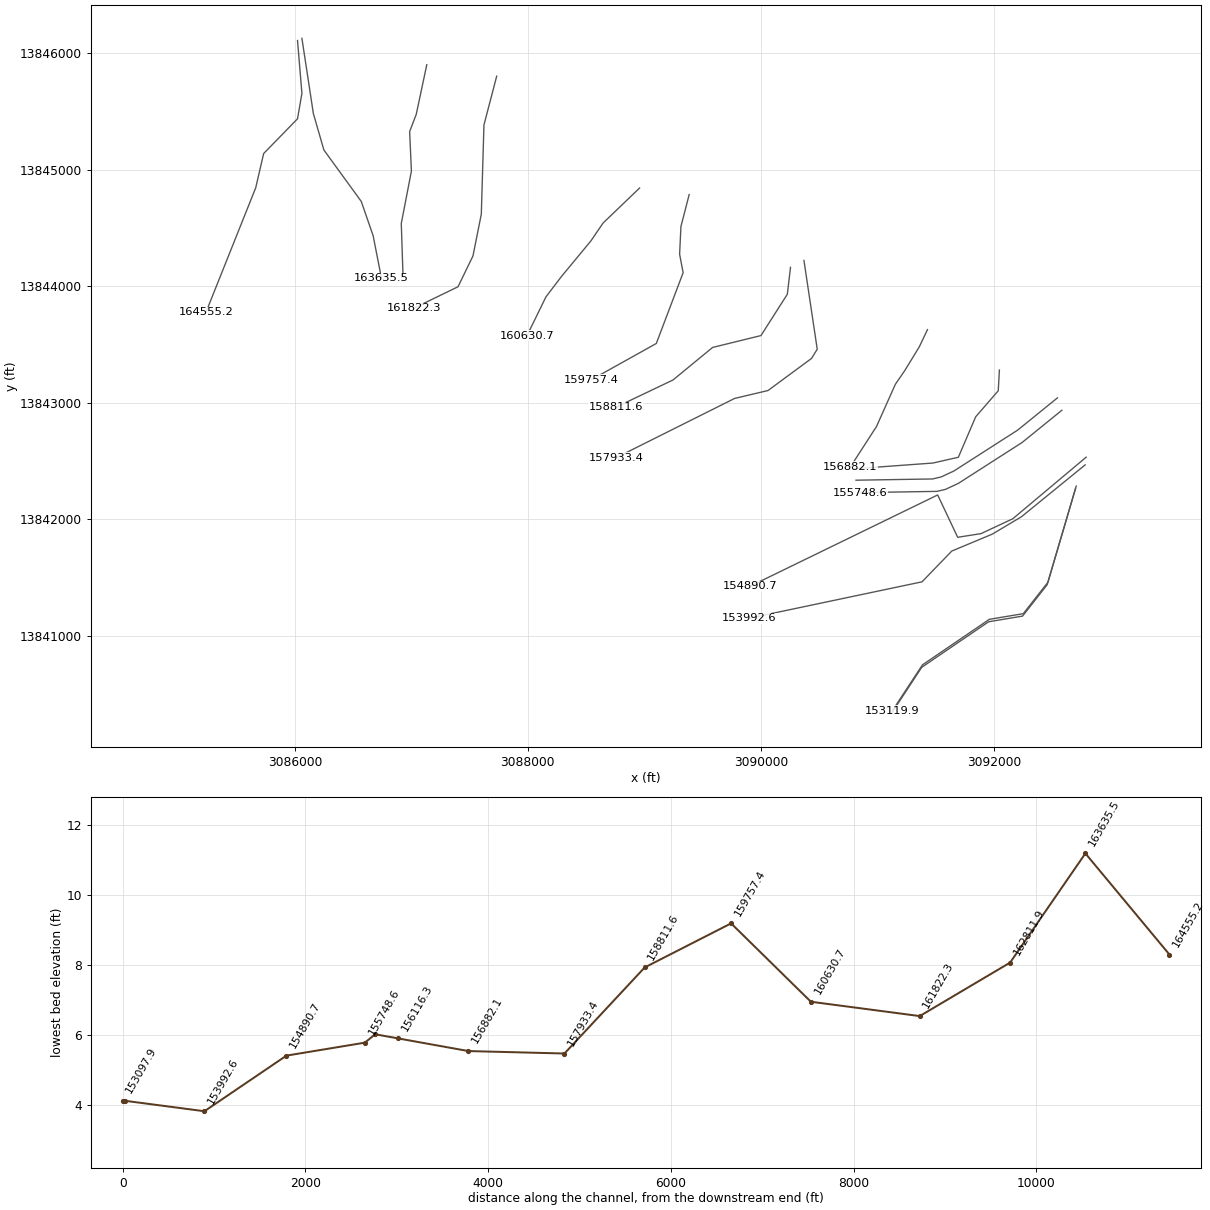
HEC-RAS study W100-00-00.prj: W100-00-00

--- W100-00-00.g01 (geometry) --- (continued)

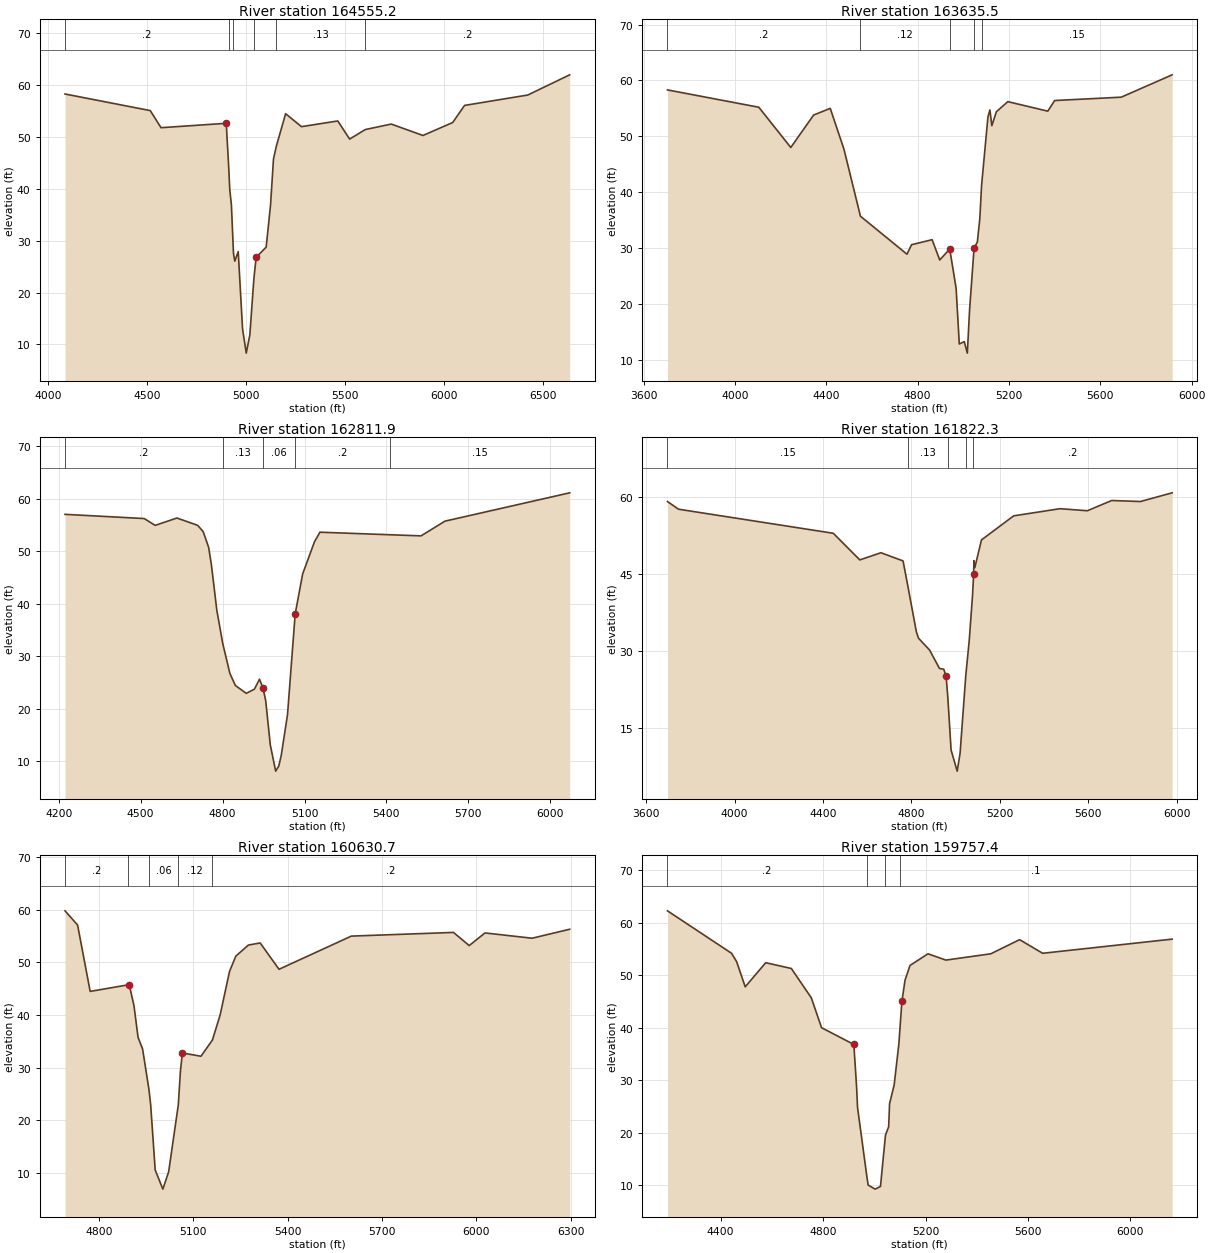
Type RM Length L Ch R = 1 ,164555.2,366.1,919.7,1153.6
BEGIN DESCRIPTION:
Cross Section 164555.2
END DESCRIPTION:
XS GIS Cut Line= 6
      3086022.73     13846109.65      3086060.47     13845656.72
      3086022.73      13845437.8       3085732.1     13845139.63
      3085663.66     13844844.93      3085236.67     13843776.73
#Sta/Elev= 30
  4085.9    58.3  4515.9    55.1  4570.4    51.8  4899.4   52.65  4911.5   44.44
  4917.1   39.88  4925.5   36.88  4935.9   27.58  4942.5   26.05  4959.9    27.9
  4981.6   13.03  5000.4    8.31  5018.4   11.81  5039.1   22.74  5050.4   26.79
    5101   28.77  5123.2   36.99  5137.7   45.73  5151.6   48.15    5199    54.5
    5279      52  5462.1    53.1  5522.1    49.6  5600.9   51.44  5732.1    52.5
  5892.1    50.3  6042.1    52.8  6102.1    56.1  6420.7    58.1  6632.5      62
#Mann= 6 ,-1 , 0
  4085.9      .2       0  4911.5      .1       0  4935.9     .06       0
  5039.1      .1       0  5151.6     .13       0  5600.9      .2       0
Bank Sta=4899.4,5050.4
XS Rating Curve= 0
Exp/Cntr=.3,.1

Type RM Length L Ch R = 1 ,163635.5,809.4,823.6,639.7
BEGIN DESCRIPTION:
Cross Section 163635.5
END DESCRIPTION:
XS GIS Cut Line= 6
      3086060.47     13846128.52      3086158.61      13845483.1
      3086249.19     13845169.82      3086570.02     13844728.22
      3086671.92     13844433.81      3086743.64      13844067.7
#Sta/Elev= 30
  3704.4    58.3  4104.4    55.2  4244.4      48  4344.4    53.8  4417.2      55
  4477.2    47.7  4549.5    35.7  4753.3    28.9  4773.3    30.6  4863.3    31.5
  4896.7   27.87  4940.5   29.83  4968.4   22.83  4982.4   12.83  5004.1   13.26
  5017.6    11.2  5027.6   19.06  5047.3   30.06  5061.4   31.06  5072.2   35.23
  5080.1   41.26  5107.8   53.45  5116.5   54.72  5124.9    51.9  5144.9    54.4
  5194.9    56.2    5370    54.5    5400    56.4  5691.6      57  5914.6      61
#Mann= 5 ,-1 , 0
  3704.4      .2       0  4549.5     .12       0  4940.5     .06       0
  5047.3     .13       0  5080.1     .15       0
Bank Sta=4940.5,5047.3
XS Rating Curve= 0
Exp/Cntr=.3,.1

Type RM Length L Ch R = 1 ,162811.9,897.9,989.6,930.8
BEGIN DESCRIPTION:
Cross Section 162811.9
END DESCRIPTION:
XS GIS Cut Line= 6
       3087132.4     13845902.05      3087041.82     13845475.55
       3086985.2     13845328.35       3087000.3     13844988.65
      3086913.49      13844539.5      3086928.58     13844082.79
#Sta/Elev= 30
    4223      57    4513    56.2    4553    54.9    4633    56.3    4709    54.9
    4729    53.7    4749    50.7    4759    47.4    4779    38.7  4800.6    32.4
  4826.7    26.7  4846.7    24.4  4886.7    22.9  4916.7    23.7  4935.2    25.6
    4948   23.91    4958   21.47  4974.7   13.09  4994.4    8.08  5005.8    9.04
    5015   11.13  5037.8   18.85  5065.9   38.03  5093.2   45.64  5136.7    51.8
  5156.7    53.6  5413.2   53.11  5526.8    52.9  5614.2    55.7  6071.2    61.1
#Mann= 5 ,-1 , 0
    4223      .2       0  4800.6     .13       0    4948     .06       0
  5065.9      .2       0  5413.2     .15       0
Bank Sta=4948,5065.9
XS Rating Curve= 0
Exp/Cntr=.3,.1

Type RM Length L Ch R = 1 ,161822.3,1323.4,1191.6,1096.8
BEGIN DESCRIPTION:
Cross Section 161822.3
END DESCRIPTION:
XS GIS Cut Line= 6
      3087732.53     13845803.92      3087623.07     13845384.96
      3087600.43     13844618.76      3087528.71     13844260.19
      3087400.38     13843995.98      3087019.17     13843811.04
#Sta/Elev= 30
    3696    59.2    3746    57.7  4446.5      53  4566.5    47.8  4662.3    49.2
  4762.3    47.6  4786.6   42.08  4822.3    33.8  4832.3    32.5  4882.3    30.2
  4927.1    26.6  4946.3   26.45    4957   25.14  4964.7   21.04  4979.7   10.66
  5007.3    6.55  5020.3   10.02  5046.1   25.18  5061.9   32.14  5076.8   40.95
  5081.8   45.05  5082.8   47.65  5087.1    46.3  5117.1    51.7  5262.7    56.4
  5472.7    57.8  5596.5    57.4  5706.5    59.4  5836.5    59.2  5980.2    60.9
#Mann= 5 ,-1 , 0
    3696     .15       0  4786.6     .13       0  4964.7     .06       0
  5046.1     .12       0  5076.8      .2       0
Bank Sta=4957,5081.8
XS Rating Curve= 0
Exp/Cntr=.3,.1

Type RM Length L Ch R = 1 ,160630.7,721.2,873.3,915.5
BEGIN DESCRIPTION:
Cross Section 160630.7
END DESCRIPTION:
XS GIS Cut Line= 6
      3088958.68      13844843.3      3088645.93     13844543.27
      3088540.25     13844388.52      3088287.37     13844082.79
      3088155.26     13843909.17      3087992.96     13843577.02
#Sta/Elev= 30
  4691.8    59.8  4731.8    57.1  4771.8    44.5  4892.7   45.75  4896.1   45.76
  4911.2   41.76  4924.1   35.78  4938.6   33.55  4958.6   25.94  4964.2   23.01
  4978.6   10.59    5003    6.96  5021.4   10.23  5052.1   22.94    5059   29.44
  5065.1   32.81  5124.2   32.19  5160.6   35.26  5185.1      40  5215.1    48.3
  5235.1    51.2  5275.1    53.3  5312.5    53.7  5372.5    48.7  5602.5      55
  5927.5    55.7  5977.5    53.2  6027.5    55.6  6177.5    54.6  6297.1    56.3
#Mann= 5 ,-1 , 0
  4691.8      .2       0  4892.7      .1       0  4958.6     .06       0
  5052.1     .12       0  5160.6      .2       0
Bank Sta=4896.1,5065.1
XS Rating Curve= 0
Exp/Cntr=.3,.1

Type RM Length L Ch R = 1 ,159757.4,1052.8,945.8,617
BEGIN DESCRIPTION:
Cross Section 159757.4
END DESCRIPTION:
XS GIS Cut Line= 6
      3089384.82     13844787.49        3089314.     13844513.08
      3089302.68     13844275.29      3089332.88     13844116.76
      3089102.64     13843509.09       3088547.8     13843199.58
#Sta/Elev= 30
  4192.8    62.3  4442.8    54.2  4462.8    52.6  4496.2    47.8  4576.2    52.4
  4676.2    51.3  4754.2    45.7  4794.2      40  4920.2    36.8    4931   28.64
  4934.6    24.8  4970.5   11.79  4975.9    9.98  5003.1     9.2  5024.1     9.7
  5043.7   19.52  5056.1   21.09  5059.6    25.5  5077.5   29.05    5096   36.93
  5100.4   39.96  5107.7      45  5120.1   49.08  5139.5   51.88  5209.5    54.1
  5279.5    52.9  5454.7    54.1  5567.2    56.8  5657.2    54.2  6162.6    56.9
#Mann= 4 ,-1 , 0
  4192.8      .2       0  4970.5     .06       0  5043.7      .1       0
  5100.4      .1       0
Bank Sta=4920.2,5107.7
XS Rating Curve= 0
Exp/Cntr=.3,.1

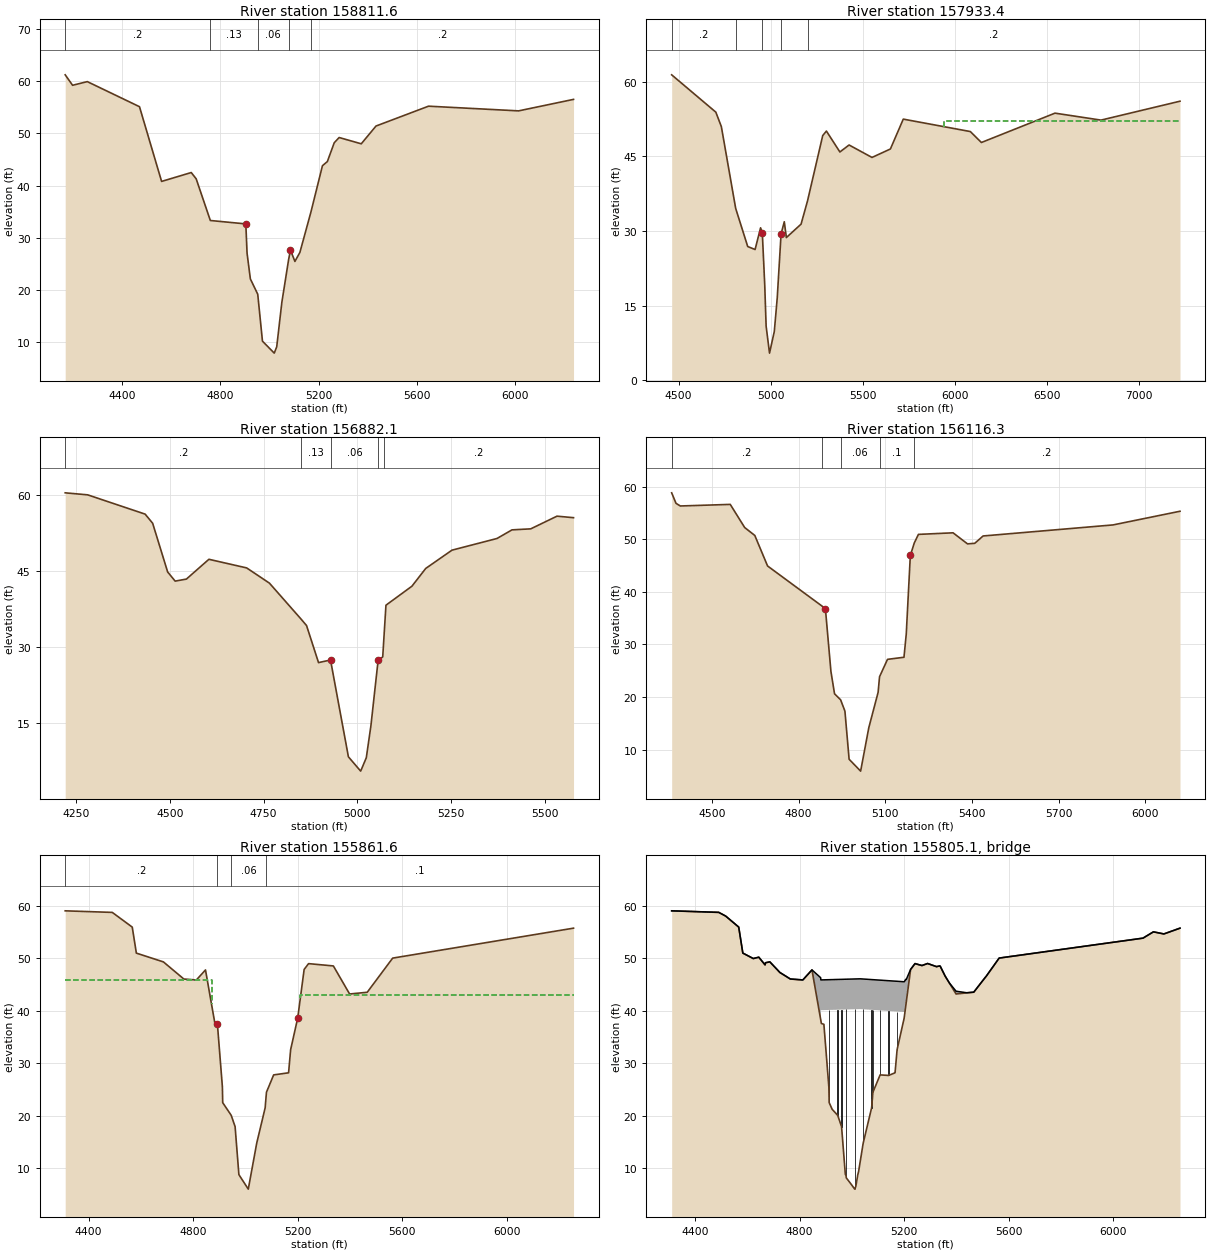
Type RM Length L Ch R = 1 ,158811.6,368.1,878.2,1014.8
BEGIN DESCRIPTION:
Cross Section 158811.6
END DESCRIPTION:
XS GIS Cut Line= 6
      3090254.54     13844162.44      3090227.41     13843931.82
      3090000.94     13843577.02      3089585.76     13843475.12
      3089246.06     13843195.81      3088755.39      13842961.8
#Sta/Elev= 30
  4168.2    61.2  4198.2    59.2  4258.2    59.9  4470.5    55.1  4560.5    40.8
  4681.2    42.5  4701.2    41.3  4758.9   33.32  4903.3   32.67  4908.3   27.07
  4921.8   22.14  4951.8   19.21    4971   10.23    5019    7.94    5029    9.14
    5050    17.7  5077.4   25.83  5084.9   27.65  5103.1   25.49  5123.3   27.21
  5168.3   34.95  5215.1    43.8  5235.1    44.6  5263.1    48.2  5283.1    49.2
  5373.1      48  5433.1    51.4  5646.9    55.2  6013.4    54.3    6237    56.5
#Mann= 5 ,-1 , 0
  4168.2      .2       0  4758.9     .13       0  4951.8     .06       0
  5077.4     .13       0  5168.3      .2       0
Bank Sta=4903.3,5084.9
XS Rating Curve= 0
Exp/Cntr=.3,.1

Type RM Length L Ch R = 1 ,157933.4,1024.1,1051.3,922.1
BEGIN DESCRIPTION:
Cross Section 157933.4
END DESCRIPTION:
XS GIS Cut Line= 6
      3090369.97     13844221.77      3090484.07     13843460.02
        3090435.     13843380.76      3090061.33     13843105.22
      3089774.48     13843037.29      3088755.39     13842527.74
#Sta/Elev= 30
    4462    61.4    4702    53.9    4732      51  4809.9   34.56  4875.3    26.9
  4915.3    26.3  4945.2   30.66  4954.5   29.71  4967.8    19.2  4975.3   10.92
  4993.8    5.48  5019.8    9.83  5035.8   16.62  5056.6   29.42  5074.1   31.88
  5085.3    28.7  5165.3    31.4  5200.3   36.06    5283    49.2    5303    50.1
  5376.2    45.9  5426.2    47.3  5550.8    44.8  5650.8    46.5  5720.8    52.5
  6085.3      50  6145.3    47.8  6545.3    53.7  6795.3    52.3  7224.7    56.1
#Mann= 5 ,-1 , 0
    4462      .2       0  4809.9     .13       0  4954.5     .06       0
  5056.6     .13       0  5200.3      .2       0
#XS Ineff= 2 , 0
                            5940            52.2
Permanent Ineff=
       F       F
Bank Sta=4954.5,5056.6
XS Rating Curve= 0
Exp/Cntr=.3,.1

Type RM Length L Ch R = 1 ,156882.1,769.3,765.8,758.4
BEGIN DESCRIPTION:
Cross Section 156882.1
END DESCRIPTION:
XS GIS Cut Line= 6
      3091430.23     13843627.83      3091360.18     13843480.48
      3091234.57     13843275.15      3091154.85      13843159.2
      3090993.01     13842796.86      3090768.35     13842449.01
#Sta/Elev= 30
  4220.9    60.4  4280.9      60  4434.1    56.2  4454.1    54.4  4494.1    44.8
  4514.1      43  4544.1    43.4  4604.1    47.3  4704.8    45.6  4765.5    42.6
  4850.5   35.46  4864.5   34.24  4896.4   26.94  4928.4   27.45  4976.1    8.37
  5008.8    5.55  5023.8    8.19    5036   14.44  5055.3   27.37  5067.6   28.06
  5071.6    32.8  5076.2   38.25  5145.5      42  5182.3    45.5  5252.3    49.1
  5372.3    51.4  5412.3    53.1  5462.3    53.3  5532.3    55.8  5576.4    55.5
#Mann= 5 ,-1 , 0
  4220.9      .2       0  4850.5     .13       0  4928.4     .06       0
  5055.3     .13       0  5071.6      .2       0
Bank Sta=4928.4,5055.3
XS Rating Curve= 0
Exp/Cntr=.3,.1

Type RM Length L Ch R = 1 ,156116.3,319.5,254.7,146.9
BEGIN DESCRIPTION:
Cross Section 156116.3 - Interpolated
END DESCRIPTION:
XS GIS Cut Line= 6
      3092047.71     13843280.96      3092037.97     13843103.31
      3091844.37     13842879.92      3091695.44     13842532.42
      3091477.01     13842482.77      3090796.91     13842433.13
#Sta/Elev= 30
  4360.2    58.8  4375.2    56.8  4390.2    56.3  4563.1    56.6  4613.1    52.2
  4648.1    50.7  4692.3    44.9  4880.8   37.28  4892.6   36.78  4911.7   24.87
  4924.2   20.61  4945.3   19.46  4960.2   17.31  4974.7    8.17  5014.6    5.91
  5042.8   14.14  5075.1   20.88  5080.1   23.85  5107.6   27.15  5164.7   27.55
  5172.6   31.96  5186.7    46.9  5200.4   49.27  5214.7    50.9  5334.7    51.2
  5384.7    49.1  5409.7    49.2  5438.7    50.6  5888.7    52.7  6120.6    55.3
#Mann= 5 ,-1 , 0
  4360.2      .2       0  4880.8      .1       0  4945.3     .06       0
  5080.1      .1       0  5200.4      .2       0
Bank Sta=4892.6,5186.7
XS Rating Curve= 0
Exp/Cntr=.5,.3

Type RM Length L Ch R = 1 ,155861.6,113,113,113
BEGIN DESCRIPTION:
Upstream Section of Bridge/Culvert/Weir
END DESCRIPTION:
XS GIS Cut Line= 6
      3092546.37      13843042.4      3092204.41     13842765.34
      3091657.13      13842414.4      3091547.36     13842363.38
      3091473.75     13842346.13      3090816.88      13842335.5
#Sta/Elev= 30
  4310.5      59  4490.5    58.7  4566.9    55.9  4582.6   50.95    4686   49.28
  4764.2   46.02  4812.1   45.84    4847   47.75    4883   37.56  4892.6    37.4
  4911.6   25.49  4912.8   22.49  4945.3   20.08  4960.2   17.93  4974.7    8.79
  5010.6    6.03  5042.8   14.76  5075.1    21.5  5080.1   24.47  5107.6   27.77
  5164.7   28.17  5172.6   32.58  5199.6   38.59  5224.2   47.84  5241.1   48.95
    5336   48.51  5398.1   43.17  5465.5    43.5  5562.8      50  6254.4    55.7
#Mann= 4 ,-1 , 0
  4310.5      .2       0  4892.6      .1       0  4945.3     .06       0
  5080.1      .1       0
#XS Ineff= 2 , 0
            4870    45.9    5210              43
Permanent Ineff=
       F       F
Bank Sta=4892.6,5199.6
XS Rating Curve= 0
Exp/Cntr=.5,.3

Type RM Length L Ch R = 3 ,155805.1,,,
BEGIN DESCRIPTION:
WOODWAY DRIVE
Structure ID: WOO-55&56
END DESCRIPTION:
Bridge Culvert--1,0,-1,-1, 0
Deck Dist Width WeirC Skew NumUp NumDn MinLoCord MaxHiCord MaxSubmerge Is_Ogee
10,93,2.6,0, 41, 41, , , .95, 0, 1,1,,
  4310.5  4490.5  4516.9  4566.9  4582.6  4622.6  4643.6  4667.6  4669.4    4686
  4724.3  4764.2  4812.1    4847  4880.3 4880.51  4880.6 4880.89  5031.6 5199.89
    5200  5205.2 5207.61  5224.2  5241.1  5267.7  5289.1  5323.7    5336    5338
  5356.4  5372.3  5398.1  5438.7  5465.5  5512.8  5562.8  6112.8  6152.8  6192.8
  6254.4
      59   58.71   58.01   55.91   50.96   49.92   50.18   48.72   49.12   49.29
   47.27   46.03   45.85   47.76   46.27   46.12   46.06   45.85   46.06    45.5
    45.5   45.94   45.93   47.85   48.96   48.59   48.98   48.37   48.52   48.41
   46.57   45.28    43.7   43.41   43.51   46.51   50.01    53.8      55    54.6
    55.7
      59    58.7      58    55.9   50.95   49.91   50.17   48.71   49.11   49.28
   47.26   46.02   45.84   47.75   38.32   38.26    40.3   40.09    40.3   39.74
   38.74    40.7    41.6   47.84   48.95   48.58   48.97   48.36   48.51    48.4
   46.56   45.27   43.17   43.38    43.5    46.5      50    53.8      55    54.6
    55.7
  4310.5  4490.5  4516.9  4566.9  4582.6  4622.6  4643.6  4667.6  4669.4    4686
  4724.3  4764.2  4812.1    4847  4880.3 4880.51  4880.6 4880.89  5031.6 5199.89
    5200  5205.2 5207.61  5224.2  5241.1  5267.7  5289.1  5323.7    5336    5338
  5356.4  5372.3  5398.1  5438.7  5465.5  5512.8  5562.8  6112.8  6152.8  6192.8
  6254.4
      59   58.71   58.01   55.91   50.96   49.92   50.18   48.72   49.12   49.29
   47.27   46.03   45.85   47.76   46.27   46.12   46.06   45.85   46.06    45.5
    45.5   45.94   45.93   47.85   48.96   48.59   48.98   48.37   48.52   48.41
   46.57   45.28    43.7   43.41   43.51   46.51   50.01    53.8      55    54.6
    55.7
   58.76   58.46   57.76   55.66   50.71   49.67   49.93   48.47   48.87   49.04
   47.02   45.78    45.6   47.51   38.08   38.02   40.06   39.85   40.06    39.5
    38.5   40.46   41.36    47.6   48.71   48.34   48.73   48.12   48.27   48.16
   46.32   45.03   42.93   43.14   43.26   46.26   49.76   53.56   54.76   54.36
   55.46
Pier Skew, UpSta & Num, DnSta & Num=  ,4912.8, 2 ,4912.8, 2 , 0 , 0 , 0 ,,
     1.4     1.4
   21.41   41.13
     1.4     1.4
   21.17   40.89
Pier Skew, UpSta & Num, DnSta & Num=  ,4945.3, 2 ,4945.3, 2 , 0 , 0 , 0 ,,
     1.4     1.4
   18.98   41.18
     1.4     1.4
   18.74   40.94
Pier Skew, UpSta & Num, DnSta & Num=  ,4960.2, 2 ,4960.2, 2 , 0 , 0 , 0 ,,
       3       3
   15.98    41.2
       3       3
   15.74   40.96
Pier Skew, UpSta & Num, DnSta & Num=  ,4978.2, 2 ,4978.2, 2 , 0 , 0 , 0 ,,
     1.4     1.4
    7.13   41.23
     1.4     1.4
    6.89   40.99
Pier Skew, UpSta & Num, DnSta & Num=  ,5010.6, 2 ,5010.6, 2 , 0 , 0 , 0 ,,
     1.4     1.4
    5.08   41.27
     1.4     1.4
    4.84   41.03
Pier Skew, UpSta & Num, DnSta & Num=  ,5042.8, 2 ,5042.8, 2 , 0 , 0 , 0 ,,
     1.4     1.4
   13.54   41.26
     1.4     1.4
    13.3   41.02
Pier Skew, UpSta & Num, DnSta & Num=  ,5075.1, 2 ,5075.1, 2 , 0 , 0 , 0 ,,
     1.4     1.4
   20.35   41.16
     1.4     1.4
   20.11   40.92
Pier Skew, UpSta & Num, DnSta & Num=  ,5080.1, 2 ,5080.1, 2 , 0 , 0 , 0 ,,
       3       3
   22.58   41.15
       3       3
   22.34   40.91
Pier Skew, UpSta & Num, DnSta & Num=  ,5107.6, 2 ,5107.6, 2 , 0 , 0 , 0 ,,
     1.4     1.4
   26.69   41.05
     1.4     1.4
   26.45   40.81
Pier Skew, UpSta & Num, DnSta & Num=  ,5140.3, 2 ,5140.3, 2 , 0 , 0 , 0 ,,
     1.4     1.4
   26.67   40.94
     1.4     1.4
   26.43    40.7
Pier Skew, UpSta & Num, DnSta & Num=  ,5172.6, 2 ,5172.6, 2 , 0 , 0 , 0 ,,
     1.4     1.4
   31.19   40.83
     1.4     1.4
   30.95   40.59
Abutment Skew #Up #Dn= , 2 , 2
  4880.4  4911.7
    40.3   25.24
  4880.4  4911.7
   40.06      25
Abutment Skew #Up #Dn= , 2 , 2
  5164.7 5200.09
   28.17   39.74
  5164.7 5200.09
   27.93    39.5
BR Coef= 1 , 1 , 0 ,1.25, 0 ,,,.8,-1,2,0,
WSPro=,,,, 1 ,,,, 0 ,,,, 0 ,,,,-1 ,-1 ,-1 , 0 , 0 , 0 , 0 , 0
BR U #Sta/Elev= 91
  4310.5      59    4478   58.72  4490.5    58.7  4516.9      58  4557.9   56.28
  4566.9    55.9  4582.6   50.95  4598.8   50.53  4622.6   49.91  4639.6   50.12
    4640   50.13  4643.6   50.17  4667.6   48.71  4669.4   49.11  4680.7   49.23
    4686   49.28  4717.9    47.6  4718.3   47.58  4724.3   47.26  4764.2   46.02
  4805.9   45.86  4812.1   45.84    4847   47.75  4880.3   38.32 4880.51   38.26
  4880.6   38.24  4880.8   38.18 4880.89   38.16    4881   38.13 4881.11   38.09
    4883   37.56  4892.6    37.4  4911.6   25.49  4911.7   25.24  4912.8   22.49
  4924.2   21.23  4945.3   20.08  4960.2   17.93  4974.7    8.79  4977.1     8.7
  4978.2    8.18  4999.5    6.79  5010.6    6.03  5014.6    6.53  5022.2    8.77
  5025.3    9.37  5031.6   11.31  5042.8   14.76  5075.1    21.5  5080.1   24.47
  5107.6   27.77  5140.3   27.67  5164.6   28.17  5164.7   28.17  5172.6   32.58
  5199.6   38.59 5199.89    38.7    5200   38.74  5200.1   38.78  5200.4   38.89
  5205.2    40.7 5207.39   41.52  5207.5   41.56 5207.61    41.6  5224.2   47.84
  5241.1   48.95  5258.9    48.7  5267.7   48.58  5289.1   48.97  5321.6    48.4
  5323.7   48.36  5324.9   48.41    5336   48.51    5338    48.4  5356.4   46.56
  5372.3   45.27  5398.1   43.17  5438.7   43.38    5464   43.51  5465.5    43.5
  5496.4   45.49  5496.8   45.52  5508.9    46.3  5512.8    46.5  5521.8   47.13
  5562.8      50  5623.4   50.42  6112.8    53.8  6152.8      55  6192.8    54.6
  6254.4    55.7
BR U #Mann= 4
  4310.5      .2  4892.6      .1  4945.3     .06  5080.1      .1
BR U Banks=4892.6,5199.6
BR D #Sta/Elev= 91
  4310.5   58.76    4478   58.48  4490.5   58.46  4516.9   57.76  4557.9   56.04
  4566.9   55.66  4582.6   50.71  4598.8   50.29  4622.6   49.67  4639.6   49.88
    4640   49.89  4643.6   49.93  4667.6   48.47  4669.4   48.87  4680.7   48.99
    4686   49.04  4717.9   47.36  4718.3   47.34  4724.3   47.02  4764.2   45.78
  4805.9   45.62  4812.1    45.6    4847   47.51  4880.3   38.08 4880.51   38.02
  4880.6      38  4880.8   37.94 4880.89   37.92    4881   37.89 4881.11   37.85
    4883   37.32  4892.6   37.16  4911.6   25.25  4911.7      25  4912.8   22.25
  4924.2   20.99  4945.3   19.84  4960.2   17.69  4974.7    8.55  4977.1    8.46
  4978.2    7.94  4999.5    6.55  5010.6    5.79  5014.6    6.29  5022.2    8.53
  5025.3    9.13  5031.6   11.07  5042.8   14.52  5075.1   21.26  5080.1   24.23
  5107.6   27.53  5140.3   27.43  5164.6   27.93  5164.7   27.93  5172.6   32.34
  5199.6   38.35 5199.89   38.46    5200    38.5  5200.1   38.54  5200.4   38.65
  5205.2   40.46 5207.39   41.28  5207.5   41.32 5207.61   41.36  5224.2    47.6
  5241.1   48.71  5258.9   48.46  5267.7   48.34  5289.1   48.73  5321.6   48.16
  5323.7   48.12  5324.9   48.17    5336   48.27    5338   48.16  5356.4   46.32
  5372.3   45.03  5398.1   42.93  5438.7   43.14    5464   43.27  5465.5   43.26
  5496.4   45.25  5496.8   45.28  5508.9   46.06  5512.8   46.26  5521.8   46.89
  5562.8   49.76  5623.4   50.18  6112.8   53.56  6152.8   54.76  6192.8   54.36
  6254.4   55.46
BR D #Mann= 4
  4310.5      .2  4892.6      .1  4945.3     .06  5080.1      .1
BR D Banks=4892.6,5199.6
BC Design=,, 0 ,, 0 ,,,,,,
BC HTab HWMax=59

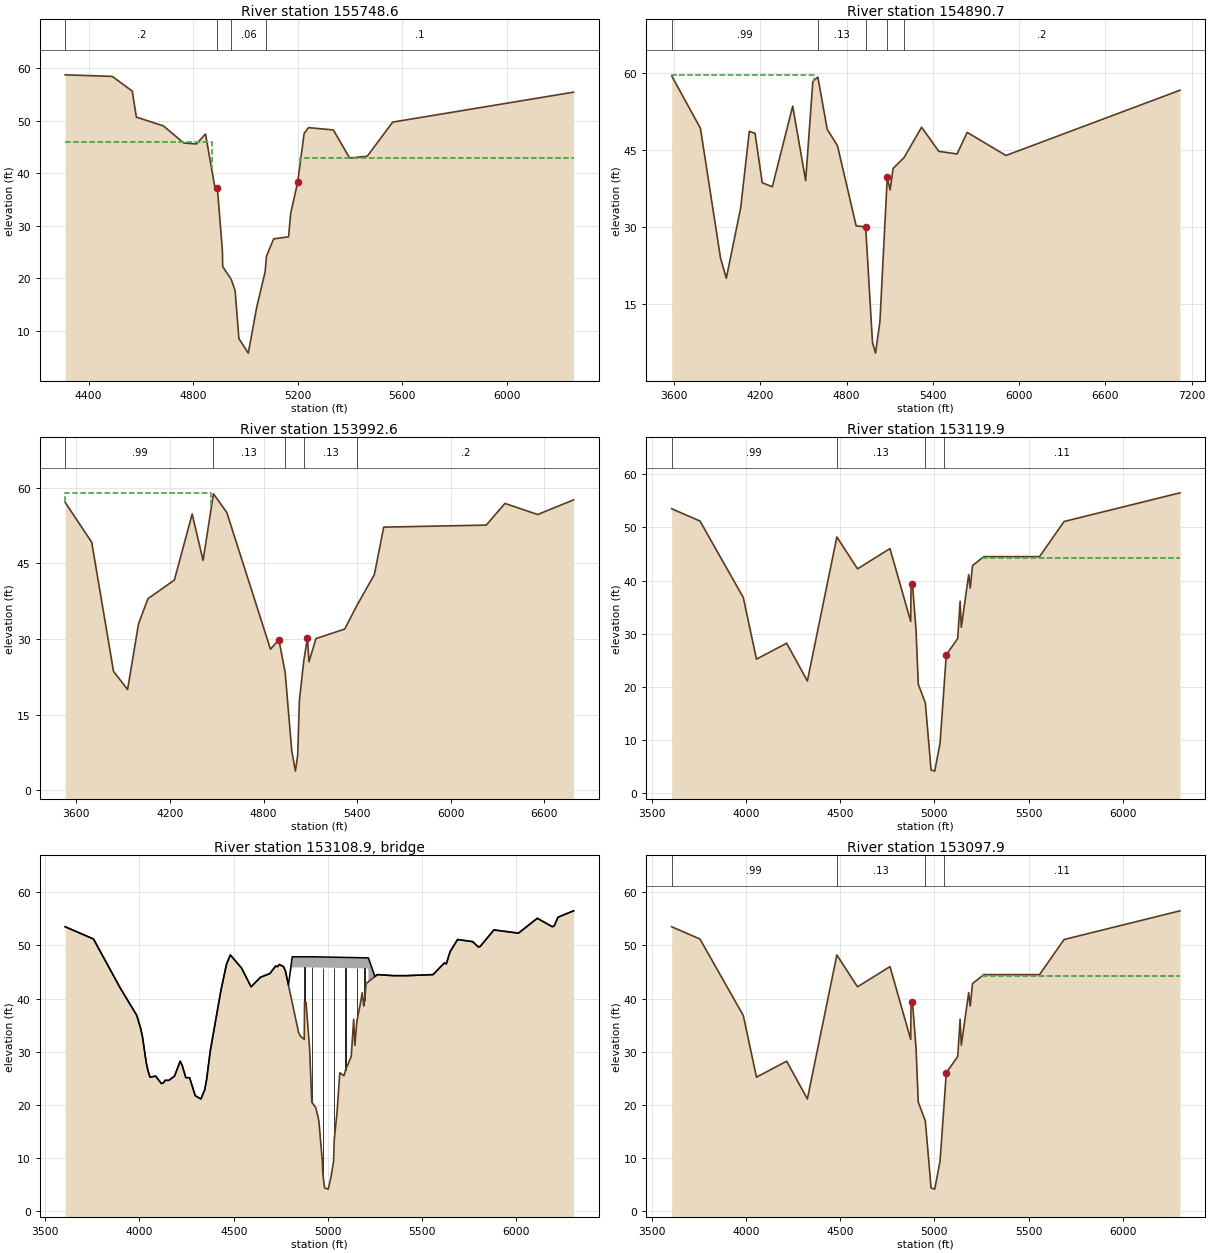
Type RM Length L Ch R = 1 ,155748.6,857.9,857.9,857.9
BEGIN DESCRIPTION:
Downstream Section of Bridge/Culvert/Weir
END DESCRIPTION:
XS GIS Cut Line= 6
      3092584.01     13842935.85      3092242.05      13842658.8
      3091694.77     13842307.86        3091585.     13842256.84
      3091511.39     13842239.59      3090854.52     13842228.95
#Sta/Elev= 30
  4310.5   58.76  4490.5   58.46  4566.9   55.66  4582.6   50.71    4686   49.04
  4764.2   45.78  4812.1    45.6    4847   47.51    4883   37.32  4892.6   37.16
  4911.6   25.25  4912.8   22.25  4945.3   19.84  4960.2   17.69  4974.7    8.55
  5010.6    5.79  5042.8   14.52  5075.1   21.26  5080.1   24.23  5107.6   27.53
  5164.7   27.93  5172.6   32.34  5199.6   38.35  5224.2    47.6  5241.1   48.71
    5336   48.27  5398.1   42.93  5465.5   43.26  5562.8   49.76  6254.4   55.46
#Mann= 4 ,-1 , 0
  4310.5      .2       0  4892.6      .1       0  4945.3     .06       0
  5080.1      .1       0
#XS Ineff= 2 , 0
            4870    45.9    5210            42.9
Permanent Ineff=
       F       F
Bank Sta=4892.6,5199.6
XS Rating Curve= 0
Exp/Cntr=.5,.3

Type RM Length L Ch R = 1 ,154890.7,100.3,898.1,1091.3
BEGIN DESCRIPTION:
Cross Section 154890.7
END DESCRIPTION:
XS GIS Cut Line= 6
      3092792.46     13842532.97      3092162.87     13842004.64
       3091889.9     13841876.96      3091689.69     13841845.37
      3091517.86     13842208.86      3089904.27     13841423.48
#Sta/Elev= 30
  3583.4    59.4  3783.4    49.2  3923.4    23.9  3963.4      20  4063.4    33.7
  4123.4    48.6  4163.4    48.2  4213.4    38.6  4283.4    37.8  4425.3    53.5
  4515.3      39  4565.3    58.3  4600.3   59.15  4665.3      49  4736.6    45.8
  4866.6    30.2  4932.7      30  4980.2     7.5  5001.2    5.42  5031.8   11.53
    5083   39.63  5102.9    37.2  5123.4   41.36  5199.8   43.49  5321.7    49.4
  5441.7    44.7  5568.7    44.2  5638.7    48.4  5908.7    43.9  7119.1    56.6
#Mann= 5 ,-1 , 0
  3583.4     .99       0  4600.3     .13       0  4932.7     .06       0
    5083     .13       0  5199.8      .2       0
#XS Ineff= 2 , 0
            4570    59.6
Permanent Ineff=
       F       F
Bank Sta=4932.7,5083
XS Rating Curve= 0
Exp/Cntr=.3,.1

Type RM Length L Ch R = 1 ,153992.6,839.7,872.7,767.7
BEGIN DESCRIPTION:
Cross Section 153992.6
END DESCRIPTION:
XS GIS Cut Line= 6
      3092783.65     13842466.93      3092237.72     13842022.25
      3091986.76     13841872.56      3091638.95     13841727.27
      3091383.59     13841463.11      3089899.87     13841150.51
#Sta/Elev= 30
  3528.3    57.1  3698.3    49.2  3838.3    23.6  3928.3      20  3998.3      33
  4058.3      38  4228.3    41.7  4342.4    54.8  4412.4    45.6    4479   58.81
  4564.6    55.1  4844.6      28  4898.6   29.86  4938.9   23.37  4980.9    7.89
  5004.4    3.83  5019.1    7.02  5030.1   17.89  5058.5   25.79  5081.9   30.23
  5091.6    25.5  5136.1    30.1  5320.8      32    5399   36.68  5510.8    42.8
  5570.8    52.2  6228.2    52.6  6348.2    56.9  6558.2    54.7  6787.9    57.6
#Mann= 5 ,-1 , 0
  3528.3     .99       0    4479     .13       0  4938.9     .06       0
  5058.5     .13       0    5399      .2       0
#XS Ineff= 2 , 0
            4466      59
Permanent Ineff=
       F       F
Bank Sta=4898.6,5081.9
XS Rating Curve= 0
Exp/Cntr=.5,.3

Type RM Length L Ch R = 1 ,153119.9,22,22,22
BEGIN DESCRIPTION:
Upstream Section of Bridge/Culvert/Weir
END DESCRIPTION:
XS GIS Cut Line= 6
      3092707.39     13842285.05      3092464.08     13841459.11
       3092253.1     13841189.95      3091961.81      13841141.4
      3091387.32     13840750.31      3091127.86     13840354.95
#Sta/Elev= 30
  3605.9    53.5  3755.9    51.2  3985.9    36.8  4055.9    25.2  4215.9    28.2
  4325.9    21.1  4482.3   48.19    4592    42.2  4764.2      46  4874.2    32.3
 4875.83   39.36 4883.43   39.36 4902.43   30.68 4914.33   20.49 4951.73   16.98
 4982.23    4.35 5001.63    4.13 5029.83     9.4 5048.73   18.81 5062.83   26.02
 5123.53   29.09 5136.33    36.1 5142.63    31.2 5181.73   41.11 5189.93   38.58
  5202.1    42.8  5262.1    44.5  5557.8    44.5  5687.8    51.1  6302.9    56.5
#Mann= 4 ,-1 , 0
  3605.9     .99       0  4482.3     .13       0 4951.73     .06       0
 5048.73     .11       0
#XS Ineff= 2 , 0
            4790    42.6    5250            44.3
Permanent Ineff=
       F       F
Bank Sta=4883.43,5062.83
XS Rating Curve= 0
Exp/Cntr=.5,.3

Type RM Length L Ch R = 3 ,153108.9,,,
BEGIN DESCRIPTION:
24" PIPELINE
END DESCRIPTION:
Bridge Culvert--1,0,-1,-1, 0
Deck Dist Width WeirC Skew NumUp NumDn MinLoCord MaxHiCord MaxSubmerge Is_Ogee
10,2,2.6,0, 60, 60, , , .95, 0, 1,1,,
  3605.9  3755.9  3895.9  3985.9  4005.9  4015.9  4035.9  4045.9  4055.9  4085.9
  4115.9  4125.9  4135.9  4155.9  4185.9  4215.9  4225.9  4245.9  4265.9  4295.9
  4325.9  4345.9  4355.9  4375.9    4432    4462    4482    4542    4592    4642
    4692    4722    4732    4742  4764.2  4774.2 4790.23 4810.23 4917.23 5214.42
 5214.53    5249  5262.1  5347.8  5417.8  5557.8  5617.8  5627.8  5647.8  5687.8
  5767.8  5797.8  5807.8  5880.7  6010.7  6110.7  6190.7  6200.7  6220.7  6302.9
    53.5    51.2    42.1    36.8    34.4    32.8    27.9    26.3    25.2    25.4
      24    24.1    24.6    24.6    25.4    28.2    27.5    25.1    25.1    21.7
    21.1    22.8    24.7    30.2    41.5    46.5    48.2    45.7    42.2      44
    44.7    46.1      46    46.4      46    45.2   42.54   47.85   47.85   47.65
   47.65   44.13    44.5    44.3    44.3    44.5    46.7    46.5    48.8    51.1
    50.7    49.7    49.8    52.9    52.3    55.1    53.5    53.7    55.3    56.5
    53.5    51.2    42.1    36.8    34.4    32.8    27.9    26.3    25.2    25.4
      24    24.1    24.6    24.6    25.4    28.2    27.5    25.1    25.1    21.7
    21.1    22.8    24.7    30.2    41.5    46.5    48.2    45.7    42.2      44
    44.7    46.1      46    46.4      46    45.2   42.54   45.85   45.85   45.65
   43.15   44.13    44.5    44.3    44.3    44.5    46.7    46.5    48.8    51.1
    50.7    49.7    49.8    52.9    52.3    55.1    53.5    53.7    55.3    56.5
  3605.9  3755.9  3895.9  3985.9  4005.9  4015.9  4035.9  4045.9  4055.9  4085.9
  4115.9  4125.9  4135.9  4155.9  4185.9  4215.9  4225.9  4245.9  4265.9  4295.9
  4325.9  4345.9  4355.9  4375.9    4432    4462    4482    4542    4592    4642
    4692    4722    4732    4742  4764.2  4774.2 4790.23 4810.23 4917.23 5214.42
 5214.53    5249  5262.1  5347.8  5417.8  5557.8  5617.8  5627.8  5647.8  5687.8
  5767.8  5797.8  5807.8  5880.7  6010.7  6110.7  6190.7  6200.7  6220.7  6302.9
    53.5    51.2    42.1    36.8    34.4    32.8    27.9    26.3    25.2    25.4
      24    24.1    24.6    24.6    25.4    28.2    27.5    25.1    25.1    21.7
    21.1    22.8    24.7    30.2    41.5    46.5    48.2    45.7    42.2      44
    44.7    46.1      46    46.4      46    45.2   42.54   47.85   47.85   47.65
   47.65   44.13    44.5    44.3    44.3    44.5    46.7    46.5    48.8    51.1
    50.7    49.7    49.8    52.9    52.3    55.1    53.5    53.7    55.3    56.5
    53.5    51.2    42.1    36.8    34.4    32.8    27.9    26.3    25.2    25.4
      24    24.1    24.6    24.6    25.4    28.2    27.5    25.1    25.1    21.7
    21.1    22.8    24.7    30.2    41.5    46.5    48.2    45.7    42.2      44
    44.7    46.1      46    46.4      46    45.2   42.54   45.85   45.85   45.65
   43.15   44.13    44.5    44.3    44.3    44.5    46.7    46.5    48.8    51.1
    50.7    49.7    49.8    52.9    52.3    55.1    53.5    53.7    55.3    56.5
Pier Skew, UpSta & Num, DnSta & Num=  ,4875.8, 2 ,4875.8, 2 , 0 , 0 , 0 ,,
       2       2
   34.03   46.85
       2       2
   34.03   46.85
Pier Skew, UpSta & Num, DnSta & Num=  ,4914.3, 2 ,4914.3, 2 , 0 , 0 , 0 ,,
       2       2
   19.44   46.85
       2       2
   19.44   46.85
Pier Skew, UpSta & Num, DnSta & Num=  ,4972.9, 2 ,4972.9, 2 , 0 , 0 , 0 ,,
       2       2
    5.72   46.81
       2       2
    5.72   46.81
Pier Skew, UpSta & Num, DnSta & Num=  ,5033.3, 2 ,5033.3, 2 , 0 , 0 , 0 ,,
       2       2
   11.29   46.77
       2       2
   11.29   46.77
Pier Skew, UpSta & Num, DnSta & Num=  ,5093.6, 2 ,5093.6, 2 , 0 , 0 , 0 ,,
       2       2
   25.44   46.73
       2       2
   25.44   46.73
Pier Skew, UpSta & Num, DnSta & Num=  ,5153.3, 2 ,5153.3, 2 , 0 , 0 , 0 ,,
       2       2
   34.29   46.69
       2       2
   34.29   46.69
Pier Skew, UpSta & Num, DnSta & Num=  ,5194.6, 2 ,5194.6, 2 , 0 , 0 , 0 ,,
       2       2
   38.42   46.66
       2       2
   38.42   46.66
BR Coef= 1 , 1 , 0 ,1.25, 0 ,,,.8,0,2,0,
WSPro=,,,, 1 ,,,, 0 ,,,, 0 ,,,,-1 ,-1 ,-1 , 0 , 0 , 0 , 0 , 0
BR U #Sta/Elev= 95
  3605.9    53.5  3755.9    51.2  3895.9    42.1  3985.9    36.8  4005.9    34.4
  4015.9    32.8  4035.9    27.9  4045.9    26.3  4055.9    25.2  4085.9    25.4
  4115.9      24  4125.9    24.1  4135.9    24.6  4155.9    24.6  4185.9    25.4
  4215.9    28.2  4225.9    27.5  4245.9    25.1  4265.9    25.1  4295.9    21.7
  4325.9    21.1  4345.9    22.8  4355.9    24.7  4375.9    30.2    4432    41.5
    4462    46.5    4480   48.03    4482    48.2  4482.3   48.19    4542    45.7
    4592    42.2    4642      44    4692    44.7    4722    46.1    4732      46
    4742    46.4  4764.2      46  4774.2    45.2 4790.14   42.56 4790.23   42.54
 4810.23   39.23  4844.2    33.6  4854.2    32.9  4874.2    32.3 4875.83   39.36
 4883.43   39.36 4902.43   30.68 4914.33   20.49 4917.23   20.35 4936.03   19.42
 4951.73   16.98 4970.23    9.36 4972.93       7 4982.23    4.35 5001.63    4.13
 5016.53    6.48 5029.83     9.4 5033.33   13.44 5048.73   18.81 5062.83   26.02
 5084.83   25.47 5093.63   26.56 5123.53   29.09 5136.33    36.1 5142.63    31.2
 5153.33   35.71 5173.83   39.41 5181.73   41.11 5189.93   38.58 5194.63   39.65
  5202.1    42.8 5214.42   43.15 5214.53   43.15 5214.63   43.16 5214.73   43.16
    5249   44.13  5262.1    44.5  5347.8    44.3  5417.8    44.3  5557.8    44.5
  5617.8    46.7  5627.8    46.5  5647.8    48.8  5687.8    51.1  5767.8    50.7
  5797.8    49.7  5807.8    49.8  5877.8    52.8  5880.7    52.9  6010.7    52.3
  6110.7    55.1  6190.7    53.5  6200.7    53.7  6220.7    55.3  6302.9    56.5
BR U #Mann= 4
  3605.9     .99  4482.3     .13 4951.73     .06 5048.73     .11
BR U Banks=4883.43,5062.83
BR D #Sta/Elev= 95
  3605.9    53.5  3755.9    51.2  3895.9    42.1  3985.9    36.8  4005.9    34.4
  4015.9    32.8  4035.9    27.9  4045.9    26.3  4055.9    25.2  4085.9    25.4
  4115.9      24  4125.9    24.1  4135.9    24.6  4155.9    24.6  4185.9    25.4
  4215.9    28.2  4225.9    27.5  4245.9    25.1  4265.9    25.1  4295.9    21.7
  4325.9    21.1  4345.9    22.8  4355.9    24.7  4375.9    30.2    4432    41.5
    4462    46.5    4480   48.03    4482    48.2  4482.3   48.19    4542    45.7
    4592    42.2    4642      44    4692    44.7    4722    46.1    4732      46
    4742    46.4  4764.2      46  4774.2    45.2 4790.14   42.56 4790.23   42.54
 4810.23   39.23  4844.2    33.6  4854.2    32.9  4874.2    32.3 4875.83   39.36
 4883.43   39.36 4902.43   30.68 4914.33   20.49 4917.23   20.35 4936.03   19.42
 4951.73   16.98 4970.23    9.36 4972.93       7 4982.23    4.35 5001.63    4.13
 5016.53    6.48 5029.83     9.4 5033.33   13.44 5048.73   18.81 5062.83   26.02
 5084.83   25.47 5093.63   26.56 5123.53   29.09 5136.33    36.1 5142.63    31.2
 5153.33   35.71 5173.83   39.41 5181.73   41.11 5189.93   38.58 5194.63   39.65
  5202.1    42.8 5214.42   43.15 5214.53   43.15 5214.63   43.16 5214.73   43.16
    5249   44.13  5262.1    44.5  5347.8    44.3  5417.8    44.3  5557.8    44.5
  5617.8    46.7  5627.8    46.5  5647.8    48.8  5687.8    51.1  5767.8    50.7
  5797.8    49.7  5807.8    49.8  5877.8    52.8  5880.7    52.9  6010.7    52.3
  6110.7    55.1  6190.7    53.5  6200.7    53.7  6220.7    55.3  6302.9    56.5
BR D #Mann= 4
  3605.9     .99  4482.3     .13 4951.73     .06 5048.73     .11
BR D Banks=4883.43,5062.83
BC Design=,, 0 ,, 0 ,,,,,,
BC HTab HWMax=56.5

Type RM Length L Ch R = 1 ,153097.9,721.6,721.6,721.6
BEGIN DESCRIPTION:
Downstream Section of Bridge/Culvert/Weir
END DESCRIPTION:
XS GIS Cut Line= 6
      3092700.98     13842264.01      3092457.68     13841438.07
       3092246.7     13841168.91      3091955.41     13841120.36
      3091380.92     13840729.27      3091121.45      13840333.9
#Sta/Elev= 30
  3605.9    53.5  3755.9    51.2  3985.9    36.8  4055.9    25.2  4215.9    28.2
  4325.9    21.1  4482.3   48.19    4592    42.2  4764.2      46  4874.2    32.3
 4875.83   39.36 4883.43   39.36 4902.43   30.68 4914.33   20.49 4951.73   16.98
 4982.23    4.35 5001.63    4.13 5029.83     9.4 5048.73   18.81 5062.83   26.02
 5123.53   29.09 5136.33    36.1 5142.63    31.2 5181.73   41.11 5189.93   38.58
  5202.1    42.8  5262.1    44.5  5557.8    44.5  5687.8    51.1  6302.9    56.5
#Mann= 4 ,-1 , 0
  3605.9     .99       0  4482.3     .13       0 4951.73     .06       0
 5048.73     .11       0
#XS Ineff= 2 , 0
            4790    42.6    5250            44.3
Permanent Ineff=
       F       F
Bank Sta=4883.43,5062.83
XS Rating Curve= 0
Exp/Cntr=.5,.3