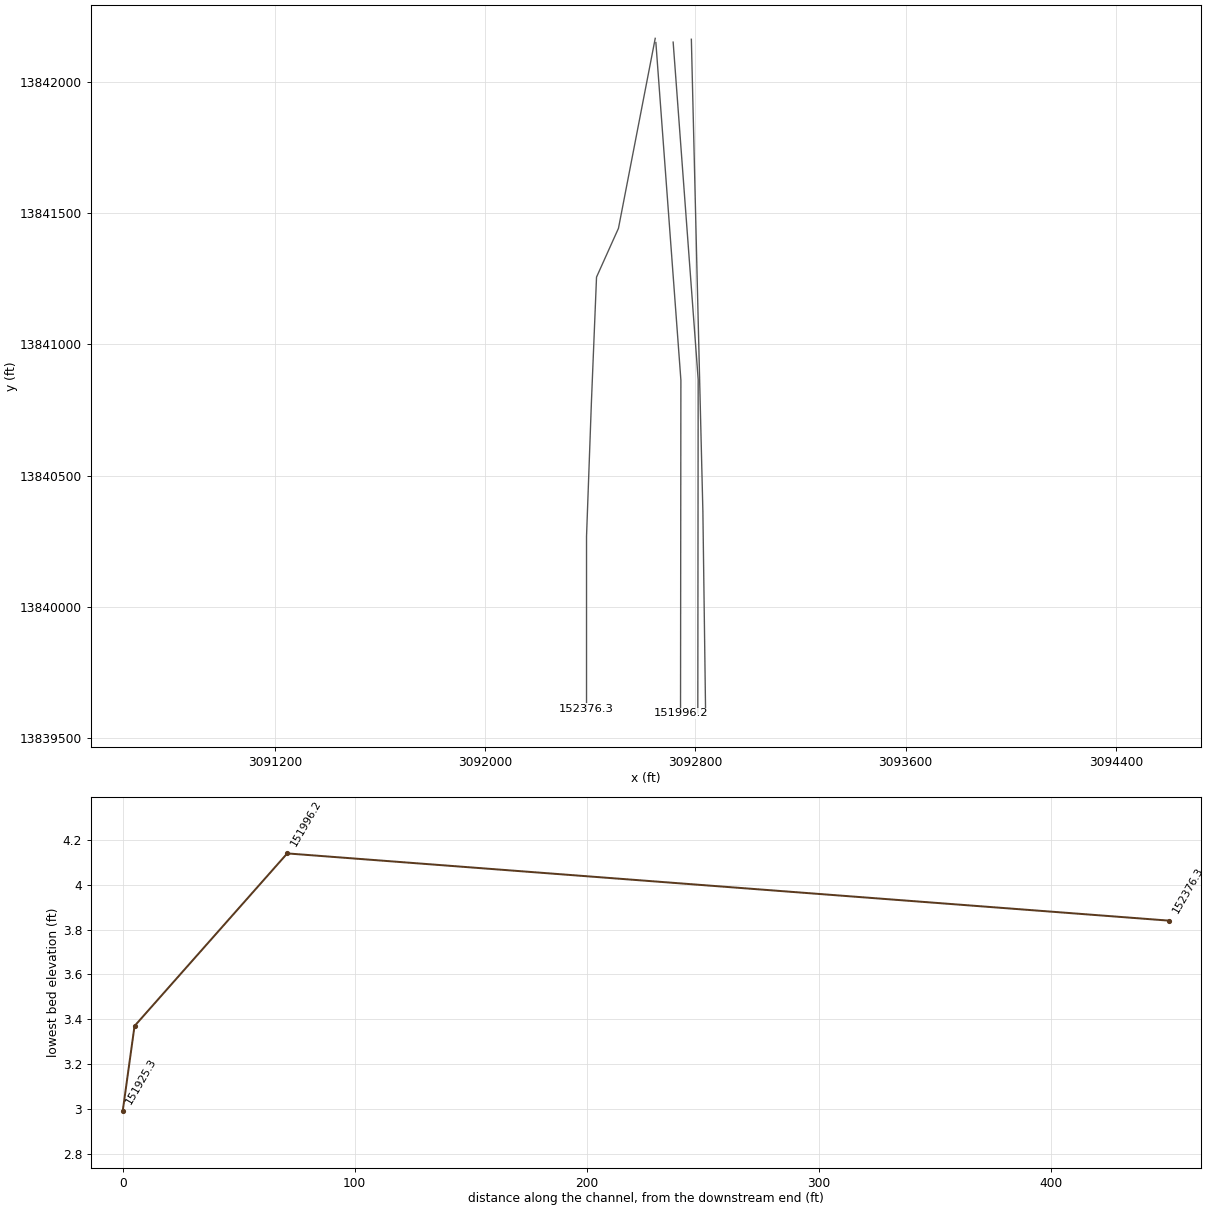
HEC-RAS study W100-00-00.prj: W100-00-00

--- W100-00-00.g01 (geometry) --- (continued)

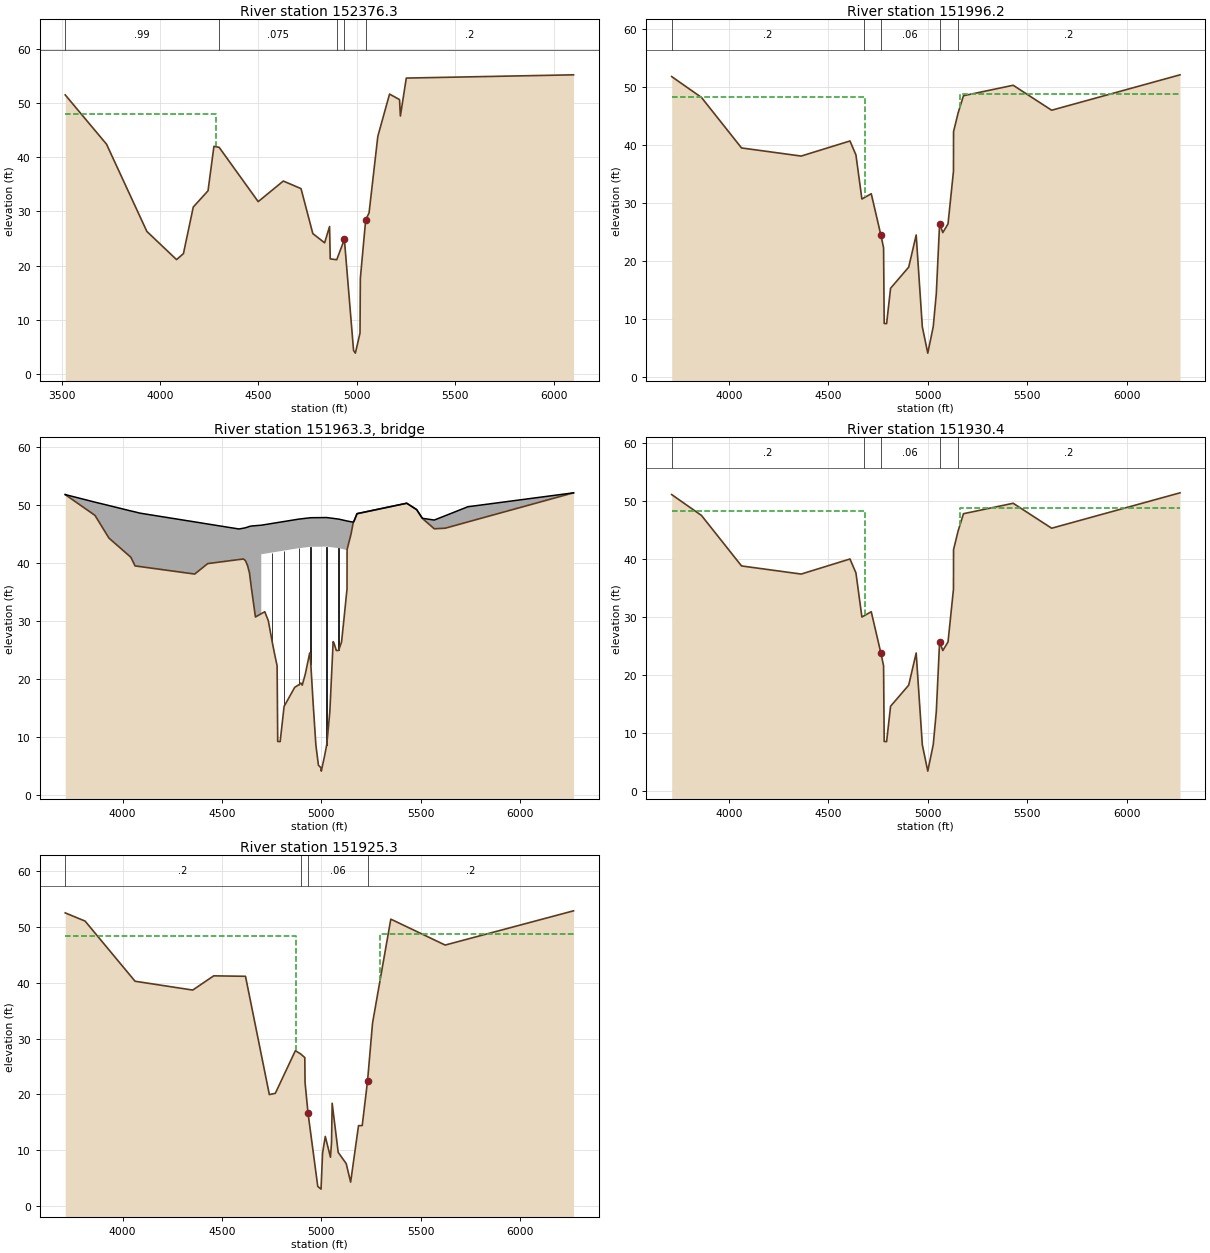
Type RM Length L Ch R = 1 ,152376.3,294.8,380.1,375.7
BEGIN DESCRIPTION:
Cross Section 152376.3 - Interpolated
END DESCRIPTION:
XS GIS Cut Line= 6
      3092646.96      13842164.7      3092507.01     13841441.63
      3092423.53     13841255.91      3092404.05     13840779.63
      3092385.47     13840268.72      3092385.47     13839613.44
#Sta/Elev= 30
  3518.2    51.5  3728.2    42.4  3933.2    26.3    4084    21.1    4119    22.2
    4169    30.8    4244    33.8    4274      42  4300.5   41.82    4499    31.8
  4626.6    35.6  4716.6    34.2  4776.6    25.9  4836.6    24.2  4861.6    27.2
  4865.1   21.23  4898.1   21.08    4937   24.83  4983.6    4.34  4992.8    3.84
  5016.4    7.55  5018.1   17.64  5045.3   28.46  5062.3    29.7  5106.9   43.85
  5166.5   51.65  5217.3   50.63  5221.6    47.6  5251.6    54.6  6101.5    55.2
#Mann= 5 ,-1 , 0
  3518.2     .99       0  4300.5    .075       0  4898.1    .075       0
    4937     .06       0  5045.3      .2       0
#XS Ineff= 2 , 0
            4286      48
Permanent Ineff=
       F       F
Bank Sta=4937,5045.3
XS Rating Curve= 0
Exp/Cntr=.5,.3

Type RM Length L Ch R = 1 ,151996.2,65.8,65.8,65.8
BEGIN DESCRIPTION:
Upstream Section of Bridge/Culvert/Weir
END DESCRIPTION:
XS GIS Cut Line= 3
       3092649.4     13842148.66      3092744.63     13840863.98
      3092743.24     13839595.48
#Sta/Elev= 30
  3711.8    51.8  3861.8    48.2  4063.2    39.5  4363.2    38.1  4608.6    40.7
  4638.6    38.3  4668.6    30.7  4677.5   30.87  4715.6   31.61    4764   24.49
  4777.6   22.29  4780.7    9.25  4792.9    9.23  4812.8   15.32    4904   18.96
  4941.6    24.5  4972.5    8.68  4999.9    4.14  5027.4     8.7  5042.8   14.38
  5059.4   26.45  5075.5   24.92  5101.7    26.4  5129.2   35.51  5129.5    42.3
  5152.3    45.5  5179.5    48.5  5429.5    50.3  5622.9      46  6268.5    52.1
#Mann= 5 ,-1 , 0
  3711.8      .2       0  4677.5     .13       0    4764     .06       0
  5059.4     .13       0  5152.3      .2       0
#XS Ineff= 2 , 0
            4685    48.2    5160            48.8
Permanent Ineff=
       F       F
Bank Sta=4764,5059.4
XS Rating Curve= 0
Exp/Cntr=.5,.3

Type RM Length L Ch R = 3 ,151963.3,,,
BEGIN DESCRIPTION:
I-610 FRONTAGE S
Structure ID: WOO-53
END DESCRIPTION:
Bridge Culvert--1,0,-1,-1, 0
Deck Dist Width WeirC Skew NumUp NumDn MinLoCord MaxHiCord MaxSubmerge Is_Ogee
10,45.8,2.6,0, 33, 33, , , .95, 0, 1,1,,
  3711.8  3861.8  3931.8  4041.8  4063.2  4087.7  4363.2  4428.6  4585.7  4608.6
  4618.6  4628.6  4638.6  4648.6  4668.6 4697.81  4697.9  4886.7  4946.8  5027.4
  5087.4  5129.2  5149.5  5159.5    5165  5179.5  5429.5  5479.5    5508    5568
  5622.9  5736.8  6268.5
    51.8   50.49   49.91   48.98   48.81    48.6   47.09   46.73   45.87   46.01
   46.08   46.19   46.31   46.38   46.44   46.52   46.52   47.57   47.81   47.84
   47.57   47.25   47.11   47.06   47.28   48.51   50.31   49.21   47.71   47.41
   48.15    49.7    52.1
    51.8    48.2    44.3      41    39.5   39.39    38.1    39.9    40.6    40.7
    40.4    39.6    38.3    35.6    30.7   31.27   41.51   42.56    42.8   42.83
   42.56   42.24      45    46.8   47.27    48.5    50.3    49.2    47.7    45.9
      46   47.08    52.1
  3711.8  3861.8  3931.8  4041.8  4063.2  4087.7  4363.2  4428.6  4585.7  4608.6
  4618.6  4628.6  4638.6  4648.6  4668.6 4697.81  4697.9  4886.7  4946.8  5027.4
  5087.4  5129.2  5149.5  5159.5    5165  5179.5  5429.5  5479.5    5508    5568
  5622.9  5736.8  6268.5
    51.8   50.49   49.91   48.98   48.81    48.6   47.09   46.73   45.87   46.01
   46.08   46.19   46.31   46.38   46.44   46.52   46.52   47.57   47.81   47.84
   47.57   47.25   47.11   47.06   47.28   48.51   50.31   49.21   47.71   47.41
   48.15    49.7    52.1
   51.78   48.18   44.28   40.98   39.48   39.37   38.08   39.88   40.58   40.68
   40.38   39.58   38.28   35.58   30.68   31.25   41.49   42.54   42.78   42.81
   42.54   42.22   44.98   46.78   47.25   48.48   50.28   49.18   47.68   45.88
   45.98   47.06   52.08
Pier Skew, UpSta & Num, DnSta & Num=  ,4752.8, 2 ,4752.8, 2 , 0 , 0 , 0 ,,
       3       3
   25.18   42.82
       3       3
   25.16    42.8
Pier Skew, UpSta & Num, DnSta & Num=  ,4812.8, 2 ,4812.8, 2 , 0 , 0 , 0 ,,
       3       3
   13.86   43.16
       3       3
   13.84   43.14
Pier Skew, UpSta & Num, DnSta & Num=  ,4887, 2 ,4887, 2 , 0 , 0 , 0 ,,
       3       3
   17.99   43.57
       3       3
   17.97   43.55
Pier Skew, UpSta & Num, DnSta & Num=  ,4947, 2 ,4947, 2 , 0 , 0 , 0 ,,
       3       3
   20.81    43.8
       3       3
   20.79   43.78
Pier Skew, UpSta & Num, DnSta & Num=  ,5026.8, 2 ,5026.8, 2 , 0 , 0 , 0 ,,
       3       3
    7.37   43.83
       3       3
    7.35   43.81
Pier Skew, UpSta & Num, DnSta & Num=  ,5087, 2 ,5087, 2 , 0 , 0 , 0 ,,
       3       3
   23.95   43.57
       3       3
   23.93   43.55
Abutment Skew #Up #Dn= , 2 , 2
  4697.7  4715.7
   41.51    31.6
  4697.7  4715.7
   41.49   31.58
Abutment Skew #Up #Dn= , 2 , 2
  5101.8 5146.79
   26.43   44.61
  5101.8 5146.79
   26.41   44.59
BR Coef= 1 , 1 , 0 ,1.25, 0 ,,,.8,0,2,0,
WSPro=,,,, 1 ,,,, 0 ,,,, 0 ,,,,-1 ,-1 ,-1 , 0 , 0 , 0 , 0 , 0
BR U #Sta/Elev= 91
  3711.8    51.8    3837    48.8  3861.8    48.2  3931.8    44.3  4041.8      41
  4063.2    39.5  4087.7   39.39  4363.2    38.1  4428.6    39.9  4585.7    40.6
 4590.89   40.62    4591   40.62 4591.11   40.62  4608.6    40.7  4617.2   40.44
    4618   40.42  4618.6    40.4  4628.6    39.6  4638.6    38.3  4641.8   37.44
  4642.1   37.36  4648.6    35.6  4668.6    30.7  4677.5   30.87 4697.81   31.27
  4697.9   31.27  4715.6   31.61  4715.7    31.6  4716.7   31.51  4733.4   30.06
  4752.8   26.44    4764   24.49  4771.6   23.26  4777.6   22.29  4780.7    9.25
  4792.9    9.23  4812.8   15.32  4816.5   15.52  4831.4   16.44  4866.1   18.58
  4886.7   19.02    4887   19.03  4896.8   19.32    4904   18.96  4919.3   20.85
  4941.6    24.5  4942.9   24.21  4946.8   22.75    4947   22.68  4958.4   16.07
  4972.5    8.68  4985.5    5.16  4998.1    4.71  4999.9    4.14  5016.3    6.75
  5026.8    8.64  5027.1    8.67  5027.4     8.7  5042.8   14.38  5059.4   26.45
  5063.8    26.2  5075.5   24.92  5087.1   24.95  5087.4   24.98  5101.7    26.4
  5101.8   26.43  5113.5   30.24  5125.4   34.27  5129.2   35.51  5129.5    42.3
 5146.59   44.61  5146.7   44.62  5147.1   44.68  5149.5      45  5152.3    45.5
  5159.5    46.8    5165   47.27  5179.5    48.5    5211   48.73 5254.19   49.04
  5254.3   49.04 5254.41   49.04  5305.2   49.41  5429.5    50.3  5456.9    49.7
  5479.5    49.2    5508    47.7    5568    45.9  5622.9      46  5736.8   47.08
  6268.5    52.1
BR U #Mann= 5
  3711.8      .2  4677.5     .13    4764     .06  5059.4     .13  5152.3      .2
BR U Banks=4764,5059.4
BR D #Sta/Elev= 91
  3711.8   51.78    3837   48.78  3861.8   48.18  3931.8   44.28  4041.8   40.98
  4063.2   39.48  4087.7   39.37  4363.2   38.08  4428.6   39.88  4585.7   40.58
 4590.89    40.6    4591    40.6 4591.11    40.6  4608.6   40.68  4617.2   40.42
    4618    40.4  4618.6   40.38  4628.6   39.58  4638.6   38.28  4641.8   37.42
  4642.1   37.34  4648.6   35.58  4668.6   30.68  4677.5   30.85 4697.81   31.25
  4697.9   31.25  4715.6   31.59  4715.7   31.58  4716.7   31.49  4733.4   30.04
  4752.8   26.42    4764   24.47  4771.6   23.24  4777.6   22.27  4780.7    9.23
  4792.9    9.21  4812.8    15.3  4816.5    15.5  4831.4   16.42  4866.1   18.56
  4886.7      19    4887   19.01  4896.8    19.3    4904   18.94  4919.3   20.83
  4941.6   24.48  4942.9   24.19  4946.8   22.73    4947   22.66  4958.4   16.05
  4972.5    8.66  4985.5    5.14  4998.1    4.69  4999.9    4.12  5016.3    6.73
  5026.8    8.62  5027.1    8.65  5027.4    8.68  5042.8   14.36  5059.4   26.43
  5063.8   26.18  5075.5    24.9  5087.1   24.93  5087.4   24.96  5101.7   26.38
  5101.8   26.41  5113.5   30.22  5125.4   34.25  5129.2   35.49  5129.5   42.28
 5146.59   44.59  5146.7    44.6  5147.1   44.66  5149.5   44.98  5152.3   45.48
  5159.5   46.78    5165   47.25  5179.5   48.48    5211   48.71 5254.19   49.02
  5254.3   49.02 5254.41   49.02  5305.2   49.39  5429.5   50.28  5456.9   49.68
  5479.5   49.18    5508   47.68    5568   45.88  5622.9   45.98  5736.8   47.06
  6268.5   52.08
BR D #Mann= 5
  3711.8      .2  4677.5     .13    4764     .06  5059.4     .13  5152.3      .2
BR D Banks=4764,5059.4
BC Design=,, 0 ,, 0 ,,,,,,
BC HTab HWMax=52.1

Type RM Length L Ch R = 1 ,151930.4,5.1,5.1,5.1
BEGIN DESCRIPTION:
Downstream Section of Bridge/Culvert/Weir
END DESCRIPTION:
XS GIS Cut Line= 3
      3092715.17     13842150.36      3092810.41     13840865.68
      3092809.02     13839597.18
#Sta/Elev= 30
  3711.8   51.03  3861.8   47.43  4063.2   38.73  4363.2   37.33  4608.6   39.93
  4638.6   37.53  4668.6   29.93  4677.5    30.1  4715.6   30.84    4764   23.72
  4777.6   21.52  4780.7    8.48  4792.9    8.46  4812.8   14.55    4904   18.19
  4941.6   23.73  4972.5    7.91  4999.9    3.37  5027.4    7.93  5042.8   13.61
  5059.4   25.68  5075.5   24.15  5101.7   25.63  5129.2   34.74  5129.5   41.53
  5152.3   44.73  5179.5   47.73  5429.5   49.53  5622.9   45.23  6268.5   51.33
#Mann= 5 ,-1 , 0
  3711.8      .2       0  4677.5     .13       0    4764     .06       0
  5059.4     .13       0  5152.3      .2       0
#XS Ineff= 2 , 0
            4685    48.2    5160            48.7
Permanent Ineff=
       F       F
Bank Sta=4764,5059.4
XS Rating Curve= 0
Exp/Cntr=.5,.3

Type RM Length L Ch R = 1 ,151925.3,158,158,158
BEGIN DESCRIPTION:
Upstream Section of Bridge/Culvert/Weir
END DESCRIPTION:
XS GIS Cut Line= 4
      3092784.46     13842161.18      3092815.75     13840873.36
      3092828.31     13840364.86      3092838.57     13839605.09
#Sta/Elev= 30
  3711.8   52.53  3811.8   51.06  4063.2   40.27  4353.2   38.69  4458.6   41.24
  4618.6   41.16  4738.6   19.95  4768.6   20.17  4869.5   27.82  4896.3   27.23
  4916.9   26.58  4918.1   22.12  4933.1   16.63  4982.1    3.48  4998.5    2.99
  5006.2    9.45  5019.9   12.44    5046    8.71  5051.3   11.38  5054.5   18.39
  5084.9    9.58  5125.1    7.57  5147.4    4.25    5187   14.37  5205.7   14.39
  5232.6   22.45  5257.6   32.77  5349.5   51.41  5622.9   46.76  6268.5    52.9
#Mann= 4 ,-1 , 0
  3711.8      .2       0  4896.3     .06       0  4933.1     .06       0
  5232.6      .2       0
#XS Ineff= 2 , 0
            4875    48.3    5295            48.7
Permanent Ineff=
       F       F
Bank Sta=4933.1,5232.6
XS Rating Curve= 0
Exp/Cntr=.5,.3