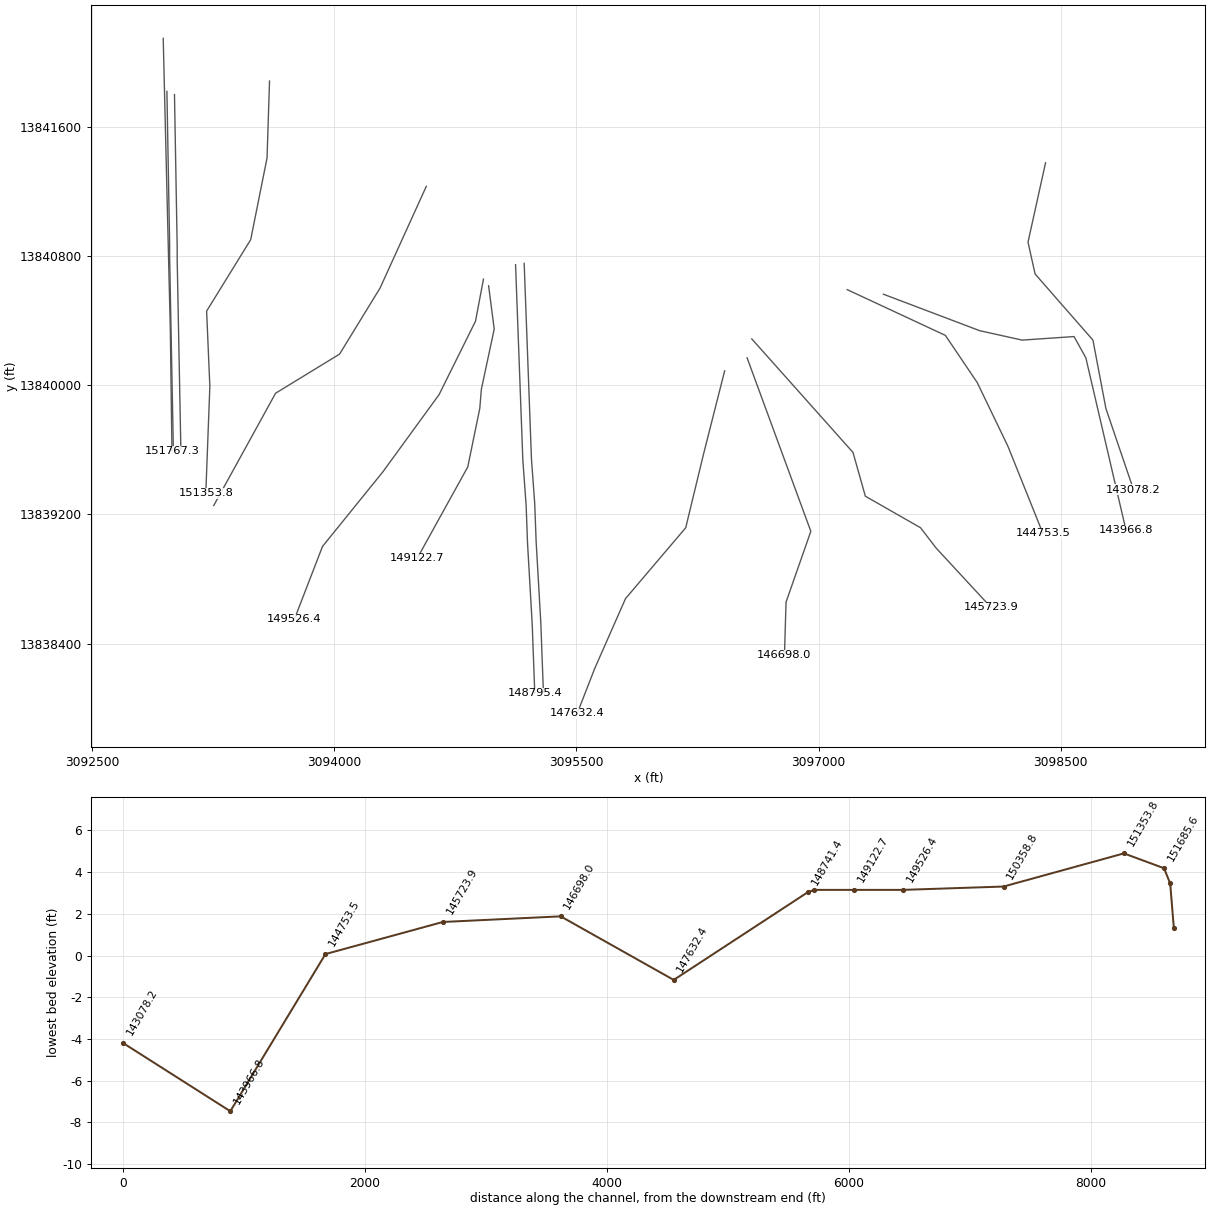
HEC-RAS study W100-00-00.prj: W100-00-00

--- W100-00-00.g01 (geometry) --- (continued)

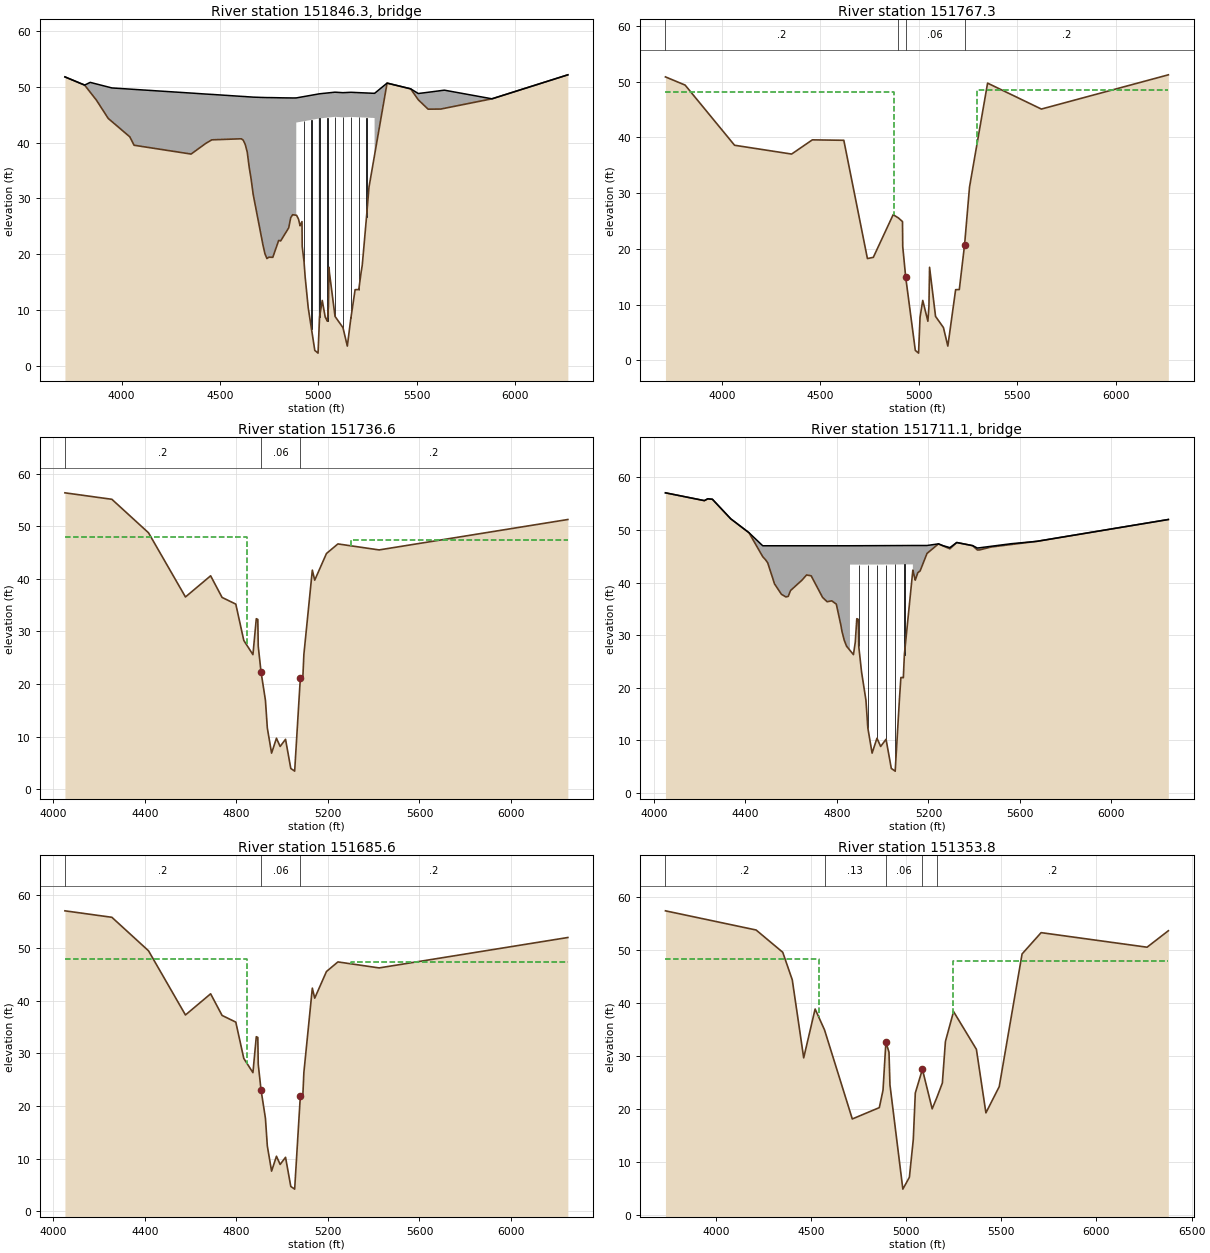
Type RM Length L Ch R = 3 ,151846.3,,,
BEGIN DESCRIPTION:
I-610
Structure ID: W00-52
END DESCRIPTION:
Bridge Culvert--1,0,-1,-1, 0
Deck Dist Width WeirC Skew NumUp NumDn MinLoCord MaxHiCord MaxSubmerge Is_Ogee
10,138,2.6,0, 44, 44, , , .95, 0, 1,1,,
  3711.8  3811.8  3840.4  3871.8  3931.8  3950.4  4041.8  4063.2  4353.2  4428.6
  4458.6  4608.6  4618.6  4628.6  4638.6  4648.6  4658.6  4668.6  4718.6  4728.6
  4738.6  4748.6  4768.6  4798.6  4808.6  4849.5  4859.5  4869.5 4887.71  4887.8
  5006.2  5084.9  5125.1  5165.5 5285.89    5286  5349.5  5469.5    5508    5558
  5622.9  5640.9  5882.9  6268.5
   51.78   50.31    50.8   50.51   49.97    49.8   49.59   49.54   48.88    48.7
   48.64   48.29   48.27   48.25   48.22    48.2   48.18   48.15   48.09   48.08
   48.07   48.07   48.06   48.04   48.03   48.01   48.01      48   48.01   48.01
   48.75   49.04   48.95   49.02   48.83   48.83   50.67   49.64    48.8   49.02
   49.32    49.4   47.85   52.15
   51.78   50.31   49.02   47.61   44.33   43.77   41.02   39.52   37.94   39.87
   40.49   40.68   40.41   39.64   38.29   35.56   33.39   30.73   21.62   20.06
    19.2   19.44   19.42   22.46   22.36   24.71   26.52   27.07   26.97   43.59
   44.33   44.62   44.53    44.6   44.41   37.78   50.66   49.63   47.68   45.99
   46.01   46.14   47.85   52.15
  3711.8  3811.8  3840.4  3871.8  3931.8  3950.4  4041.8  4063.2  4353.2  4428.6
  4458.6  4608.6  4618.6  4628.6  4638.6  4648.6  4658.6  4668.6  4718.6  4728.6
  4738.6  4748.6  4768.6  4798.6  4808.6  4849.5  4859.5  4869.5 4887.71  4887.8
  5006.2  5084.9  5125.1  5165.5 5285.89    5286  5349.5  5469.5    5508    5558
  5622.9  5640.9  5882.9  6268.5
   51.78   50.31    50.8   50.51   49.97    49.8   49.59   49.54   48.88    48.7
   48.64   48.29   48.27   48.25   48.22    48.2   48.18   48.15   48.09   48.08
   48.07   48.07   48.06   48.04   48.03   48.01   48.01      48   48.01   48.01
   48.75   49.04   48.95   49.02   48.83   48.83   50.67   49.64    48.8   49.02
   49.32    49.4   47.85   52.15
   51.68   50.21   48.92   47.51   44.23   43.67   40.92   39.42   37.84   39.77
   40.39   40.58   40.31   39.54   38.19   35.46   33.29   30.63   21.52   19.96
    19.1   19.34   19.32   22.36   22.26   24.61   26.42   26.97   26.87   43.49
   44.23   44.52   44.43    44.5   44.31   37.68   50.56   49.53   47.58   45.89
   45.91   46.04   47.75   52.05
Pier Skew, UpSta & Num, DnSta & Num=  ,4927.3, 2 ,4927.3, 2 , 0 , 0 , 0 ,,
     2.5     2.5
   17.05   44.85
     2.5     2.5
   16.95   44.75
Pier Skew, UpSta & Num, DnSta & Num=  ,4965.2, 2 ,4965.2, 2 , 0 , 0 , 0 ,,
     2.5     2.5
     5.3   45.09
     2.5     2.5
     5.2   44.99
Pier Skew, UpSta & Num, DnSta & Num=  ,5006.2, 2 ,5006.2, 2 , 0 , 0 , 0 ,,
     2.5     2.5
    6.65   45.33
     2.5     2.5
    6.55   45.23
Pier Skew, UpSta & Num, DnSta & Num=  ,5046, 2 ,5046, 2 , 0 , 0 , 0 ,,
     2.5     2.5
    7.06   45.49
     2.5     2.5
    6.96   45.39
Pier Skew, UpSta & Num, DnSta & Num=  ,5084.9, 2 ,5084.9, 2 , 0 , 0 , 0 ,,
     2.5     2.5
    7.76   45.62
     2.5     2.5
    7.66   45.52
Pier Skew, UpSta & Num, DnSta & Num=  ,5125.2, 2 ,5125.2, 2 , 0 , 0 , 0 ,,
     2.5     2.5
    5.62   45.53
     2.5     2.5
    5.52   45.43
Pier Skew, UpSta & Num, DnSta & Num=  ,5165.5, 2 ,5165.5, 2 , 0 , 0 , 0 ,,
     2.5     2.5
     7.2    45.6
     2.5     2.5
     7.1    45.5
Pier Skew, UpSta & Num, DnSta & Num=  ,5205.7, 2 ,5205.7, 2 , 0 , 0 , 0 ,,
     2.5     2.5
   12.64   45.51
     2.5     2.5
   12.54   45.41
Pier Skew, UpSta & Num, DnSta & Num=  ,5245.1, 2 ,5245.1, 2 , 0 , 0 , 0 ,,
     2.5     2.5
   25.22   45.49
     2.5     2.5
   25.12   45.39
Abutment Skew #Up #Dn= , 2 , 2
  4887.6  4907.2
   43.59   25.08
  4887.6  4907.2
   43.49   24.98
BR Coef= 1 , 1 , 0 ,1.25, 0 ,,,.8,0,2,0,
WSPro=,,,, 1 ,,,, 0 ,,,, 0 ,,,,-1 ,-1 ,-1 , 0 , 0 , 0 , 0 , 0
BR U #Sta/Elev= 91
  3711.8   51.78  3811.8   50.31  3840.4   49.02  3871.8   47.61  3931.8   44.33
  3950.4   43.77  4041.8   41.02  4063.2   39.52  4353.2   37.94  4428.6   39.87
  4458.6   40.49  4608.6   40.68  4618.6   40.41  4628.6   39.64  4638.6   38.29
  4648.6   35.56  4658.6   33.39  4668.6   30.73  4692.6   26.36  4718.6   21.62
  4728.6   20.06  4738.6    19.2  4748.6   19.44  4768.6   19.42  4798.6   22.46
  4808.6   22.36  4849.5   24.71  4859.5   26.52  4869.5   27.07  4870.7   27.06
  4883.5   26.99  4885.9   26.98 4887.71   26.97  4887.8   26.97  4889.5   26.96
  4896.3   26.48  4899.5   26.25  4907.1    25.1  4907.2   25.08  4916.9   25.83
  4918.1   21.37  4927.3   18.65  4933.1   15.88  4939.1   13.75  4948.6   10.38
  4956.1    8.65  4965.1    6.58  4965.2    6.58  4982.1    2.73  4998.5    2.24
  5004.3    7.11  5006.2     8.7  5019.9   11.69  5035.1    8.69  5045.5    8.01
  5045.6       8    5046    7.96  5051.3   10.63  5054.5   17.64  5056.1   16.77
  5084.9    8.83  5085.2    8.81  5125.1    6.82  5125.2    6.81  5147.4     3.5
  5165.3    8.49  5165.4    8.52  5165.5    8.52    5187   13.62  5205.5   13.64
  5205.6   13.64  5205.7   13.64  5217.4    16.7  5223.3   18.01  5232.6    21.7
  5245.1   26.72  5245.4   26.85  5257.6   32.02  5285.7   37.72  5285.8   37.74
 5285.89   37.76    5286   37.78  5349.5   50.66  5469.5   49.63    5508   47.68
  5508.6   47.66    5558   45.99  5622.9   46.01  5640.9   46.14  5882.9   47.85
  6268.5   52.15
BR U #Mann= 4
  3711.8      .2  4896.3     .06  4933.1     .06  5232.6      .2
BR U Banks=4933.1,5232.6
BR D #Sta/Elev= 91
  3711.8   51.68  3811.8   50.21  3840.4   48.92  3871.8   47.51  3931.8   44.23
  3950.4   43.67  4041.8   40.92  4063.2   39.42  4353.2   37.84  4428.6   39.77
  4458.6   40.39  4608.6   40.58  4618.6   40.31  4628.6   39.54  4638.6   38.19
  4648.6   35.46  4658.6   33.29  4668.6   30.63  4692.6   26.26  4718.6   21.52
  4728.6   19.96  4738.6    19.1  4748.6   19.34  4768.6   19.32  4798.6   22.36
  4808.6   22.26  4849.5   24.61  4859.5   26.42  4869.5   26.97  4870.7   26.96
  4883.5   26.89  4885.9   26.88 4887.71   26.87  4887.8   26.87  4889.5   26.86
  4896.3   26.38  4899.5   26.15  4907.1      25  4907.2   24.98  4916.9   25.73
  4918.1   21.27  4927.3   18.55  4933.1   15.78  4939.1   13.65  4948.6   10.28
  4956.1    8.55  4965.1    6.48  4965.2    6.48  4982.1    2.63  4998.5    2.14
  5004.3    7.01  5006.2     8.6  5019.9   11.59  5035.1    8.59  5045.5    7.91
  5045.6     7.9    5046    7.86  5051.3   10.53  5054.5   17.54  5056.1   16.67
  5084.9    8.73  5085.2    8.71  5125.1    6.72  5125.2    6.71  5147.4     3.4
  5165.3    8.39  5165.4    8.42  5165.5    8.42    5187   13.52  5205.5   13.54
  5205.6   13.54  5205.7   13.54  5217.4    16.6  5223.3   17.91  5232.6    21.6
  5245.1   26.62  5245.4   26.75  5257.6   31.92  5285.7   37.62  5285.8   37.64
 5285.89   37.66    5286   37.68  5349.5   50.56  5469.5   49.53    5508   47.58
  5508.6   47.56    5558   45.89  5622.9   45.91  5640.9   46.04  5882.9   47.75
  6268.5   52.05
BR D #Mann= 4
  3711.8      .2  4896.3     .06  4933.1     .06  5232.6      .2
BR D Banks=4933.1,5232.6
BC Design=,, 0 ,, 0 ,,,,,,
BC HTab HWMax=52.9

Type RM Length L Ch R = 1 ,151767.3,30.7,30.7,30.7
BEGIN DESCRIPTION:
Downstream Section of Bridge/Culvert/Weir
END DESCRIPTION:
XS GIS Cut Line= 4
      3092941.94     13842148.46      3092973.23     13840860.64
      3092985.79     13840352.14      3092996.06     13839592.36
#Sta/Elev= 30
  3711.8   50.84  3811.8   49.37  4063.2   38.58  4353.2      37  4458.6   39.55
  4618.6   39.47  4738.6   18.26  4768.6   18.48  4869.5   26.13  4896.3   25.54
  4916.9   24.89  4918.1   20.43  4933.1   14.94  4982.1    1.79  4998.5     1.3
  5006.2    7.76  5019.9   10.75    5046    7.02  5051.3    9.69  5054.5    16.7
  5084.9    7.89  5125.1    5.88  5147.4    2.56    5187   12.68  5205.7    12.7
  5232.6   20.76  5257.6   31.08  5349.5   49.72  5622.9   45.07  6268.5   51.21
#Mann= 4 ,-1 , 0
  3711.8      .2       0  4896.3     .06       0  4933.1     .06       0
  5232.6      .2       0
#XS Ineff= 2 , 0
            4875    48.2    5295            48.5
Permanent Ineff=
       F       F
Bank Sta=4933.1,5232.6
XS Rating Curve= 0
Exp/Cntr=.5,.3

Type RM Length L Ch R = 1 ,151736.6,51,51,51
BEGIN DESCRIPTION:
Upstream Section of Bridge/Culvert/Weir
END DESCRIPTION:
XS GIS Cut Line= 4
      3092964.87     13841819.88      3092981.67     13840873.92
      3092981.55     13840800.89      3093004.34     13839622.15
#Sta/Elev= 30
  4050.5   56.35  4255.7   55.12  4415.7   48.76  4577.3   36.56  4687.3   40.58
  4737.3   36.47  4797.3    35.2  4832.2    28.3  4872.2    25.6  4886.9   32.43
  4893.5   32.28  4895.4   27.18  4907.7   22.29  4926.8   16.94  4935.1   11.66
  4953.7    6.88    4975    9.71  4991.1    8.15  5014.7    9.51  5037.7    3.97
  5054.6    3.46  5079.5   21.25  5090.3   21.22  5094.8   25.61  5131.8   41.66
  5142.2   39.75  5193.6   44.82  5243.6   46.64  5423.7    45.5  6248.6   51.28
#Mann= 3 ,-1 , 0
  4050.5      .2       0  4907.7     .06       0  5079.5      .2       0
#XS Ineff= 2 , 0
            4847      48    5300            47.4
Permanent Ineff=
       F       F
Bank Sta=4907.7,5079.5
XS Rating Curve= 0
Exp/Cntr=.5,.3

Type RM Length L Ch R = 3 ,151711.1,,,
BEGIN DESCRIPTION:
I-610 FRONTAGE N
Structure ID: W00-51
END DESCRIPTION:
Bridge Culvert--1,0,-1,-1, 0
Deck Dist Width WeirC Skew NumUp NumDn MinLoCord MaxHiCord MaxSubmerge Is_Ogee
10,31,2.6,0, 44, 44, , , .95, 0, 1,1,,
  4050.5  4220.5  4235.7  4255.7  4335.7  4415.7  4475.7  4487.3  4497.3  4527.3
  4557.3  4577.3  4587.3  4597.3  4647.3  4667.3  4687.3  4737.3  4757.3  4777.3
  4797.3  4817.3  4822.2  4832.2  4842.2 4856.91    4857 5131.89    5132  5142.2
  5153.6  5163.6  5193.6  5243.6 5261.49  5293.6  5323.6  5393.6  5413.6  5423.7
  5473.7  5563.7  5673.7  6248.6
   57.06   55.58   55.93   55.84   52.13   49.48      47      47      47      47
      47      47      47      47      47      47      47      47      47      47
      47      47      47      47      47      47      47   47.05   47.05   47.05
   47.05   47.05   47.05   47.36   47.05   46.65   47.62   47.02   46.57   46.62
    46.9    47.4   47.84   51.99
   57.06   55.57   55.92   55.83   52.12   49.47   44.92   44.37   43.77   39.75
   37.78   37.27   37.38   38.49   40.46   41.45   41.29   37.18   36.36   36.53
   35.91   31.88   30.69   29.01    27.9   27.12   43.41   43.46   42.33   40.46
   41.88   42.21   45.53   47.35   47.02   46.42   47.61   47.01    46.2   46.21
   46.76   47.25   47.84   51.99
  4050.5  4220.5  4235.7  4255.7  4335.7  4415.7  4475.7  4487.3  4497.3  4527.3
  4557.3  4577.3  4587.3  4597.3  4647.3  4667.3  4687.3  4737.3  4757.3  4777.3
  4797.3  4817.3  4822.2  4832.2  4842.2 4856.91    4857 5131.89    5132  5142.2
  5153.6  5163.6  5193.6  5243.6 5261.49  5293.6  5323.6  5393.6  5413.6  5423.7
  5473.7  5563.7  5673.7  6248.6
   57.06   55.58   55.93   55.84   52.13   49.48      47      47      47      47
      47      47      47      47      47      47      47      47      47      47
      47      47      47      47      47      47      47   47.05   47.05   47.05
   47.05   47.05   47.05   47.36   47.05   46.65   47.62   47.02   46.57   46.62
    46.9    47.4   47.84   51.99
   57.06   55.57   55.92   55.83   52.12   49.47   44.92   44.37   43.77   39.75
   37.78   37.27   37.38   38.49   40.46   41.45   41.29   37.18   36.36   36.53
   35.91   31.88   30.69   29.01    27.9   27.12   43.41   43.46   42.33   40.46
   41.88   42.21   45.53   47.35   47.02   46.42   47.61   47.01    46.2   46.21
   46.76   47.25   47.84   51.99
Pier Skew, UpSta & Num, DnSta & Num=  ,4895.4, 2 ,4895.4, 2 , 0 , 0 , 0 ,,
     1.4     1.4
   26.61   44.42
     1.4     1.4
   26.61   44.42
Pier Skew, UpSta & Num, DnSta & Num=  ,4935.1, 2 ,4935.1, 2 , 0 , 0 , 0 ,,
     1.4     1.4
   11.19   44.42
     1.4     1.4
   11.19   44.42
Pier Skew, UpSta & Num, DnSta & Num=  ,4975, 2 ,4975, 2 , 0 , 0 , 0 ,,
     1.4     1.4
    9.33   44.43
     1.4     1.4
    9.33   44.43
Pier Skew, UpSta & Num, DnSta & Num=  ,5014.7, 2 ,5014.7, 2 , 0 , 0 , 0 ,,
     1.4     1.4
    9.05   44.44
     1.4     1.4
    9.05   44.44
Pier Skew, UpSta & Num, DnSta & Num=  ,5054.6, 2 ,5054.6, 2 , 0 , 0 , 0 ,,
     1.4     1.4
    3.19   44.45
     1.4     1.4
    3.19   44.45
Pier Skew, UpSta & Num, DnSta & Num=  ,5094.8, 2 ,5094.8, 2 , 0 , 0 , 0 ,,
     1.4     1.4
   24.64   44.45
     1.4     1.4
   24.64   44.45
Abutment Skew #Up #Dn= , 2 , 2
  4856.8  4886.9
   43.41   33.14
  4856.8  4886.9
   43.41   33.14
Abutment Skew #Up #Dn= , 2 , 2
  5090.3 5132.09
   21.93   43.46
  5090.3 5132.09
   21.93   43.46
BR Coef= 1 , 1 , 0 ,1.25, 0 ,,,.8,0,2,0,
WSPro=,,,, 1 ,,,, 0 ,,,, 0 ,,,,-1 ,-1 ,-1 , 0 , 0 , 0 , 0 , 0
BR U #Sta/Elev= 76
  4050.5   57.06  4179.8   55.93  4220.5   55.57  4235.7   55.92  4255.7   55.83
  4335.7   52.12  4415.7   49.47  4475.7   44.92  4476.9   44.86  4487.3   44.37
  4497.3   43.77  4527.3   39.75  4557.3   37.78  4577.3   37.27  4587.3   37.38
  4597.3   38.49 4627.69   39.69  4627.8   39.69 4627.91    39.7  4647.3   40.46
  4667.3   41.45  4687.3   41.29  4737.3   37.18  4757.3   36.36  4777.3   36.53
  4797.3   35.91  4817.3   31.88  4822.2   30.69  4832.2   29.01  4842.2    27.9
  4856.8   27.13 4856.91   27.12    4857   27.12  4872.2   26.31  4880.2   28.68
  4886.8   33.07  4886.9   33.14  4893.5   32.99  4895.4   27.89  4907.7      23
  4926.8   17.65  4935.1   12.37  4953.7    7.59    4975   10.42  4991.1    8.86
  5014.7   10.22  5037.7    4.68  5054.6    4.17  5073.2   17.81  5079.5   21.96
  5090.2   21.93  5090.3   21.93  5094.8   26.32  5131.8   42.37 5131.89   42.35
    5132   42.33  5132.1   42.31  5142.2   40.46  5143.6   40.62  5153.6   41.88
  5163.6   42.21  5193.6   45.53  5243.6   47.35 5261.49   47.02  5261.6   47.02
 5261.71   47.01  5293.6   46.42  5323.6   47.61  5335.4   47.51  5393.6   47.01
  5413.6    46.2  5423.7   46.21  5473.7   46.76  5563.7   47.25  5673.7   47.84
  6248.6   51.99
BR U #Mann= 3
  4050.5      .2  4907.7     .06  5079.5      .2
BR U Banks=4907.7,5079.5
BR D #Sta/Elev= 76
  4050.5   57.06  4179.8   55.93  4220.5   55.57  4235.7   55.92  4255.7   55.83
  4335.7   52.12  4415.7   49.47  4475.7   44.92  4476.9   44.86  4487.3   44.37
  4497.3   43.77  4527.3   39.75  4557.3   37.78  4577.3   37.27  4587.3   37.38
  4597.3   38.49 4627.69   39.69  4627.8   39.69 4627.91    39.7  4647.3   40.46
  4667.3   41.45  4687.3   41.29  4737.3   37.18  4757.3   36.36  4777.3   36.53
  4797.3   35.91  4817.3   31.88  4822.2   30.69  4832.2   29.01  4842.2    27.9
  4856.8   27.13 4856.91   27.12    4857   27.12  4872.2   26.31  4880.2   28.68
  4886.8   33.07  4886.9   33.14  4893.5   32.99  4895.4   27.89  4907.7      23
  4926.8   17.65  4935.1   12.37  4953.7    7.59    4975   10.42  4991.1    8.86
  5014.7   10.22  5037.7    4.68  5054.6    4.17  5073.2   17.81  5079.5   21.96
  5090.2   21.93  5090.3   21.93  5094.8   26.32  5131.8   42.37 5131.89   42.35
    5132   42.33  5132.1   42.31  5142.2   40.46  5143.6   40.62  5153.6   41.88
  5163.6   42.21  5193.6   45.53  5243.6   47.35 5261.49   47.02  5261.6   47.02
 5261.71   47.01  5293.6   46.42  5323.6   47.61  5335.4   47.51  5393.6   47.01
  5413.6    46.2  5423.7   46.21  5473.7   46.76  5563.7   47.25  5673.7   47.84
  6248.6   51.99
BR D #Mann= 3
  4050.5      .2  4907.7     .06  5079.5      .2
BR D Banks=4907.7,5079.5
BC Design=,, 0 ,, 0 ,,,,,,
BC HTab HWMax=56.35

Type RM Length L Ch R = 1 ,151685.6,331.8,331.8,331.8
BEGIN DESCRIPTION:
Downstream Section of Bridge/Culvert/Weir
END DESCRIPTION:
XS GIS Cut Line= 4
      3093011.73     13841799.76      3093028.53      13840853.8
      3093028.41     13840780.77       3093051.2     13839602.03
#Sta/Elev= 30
  4050.5   57.08  4255.7   55.85  4415.7   49.49  4577.3   37.29  4687.3   41.31
  4737.3    37.2  4797.3   35.93  4832.2   29.03  4872.2   26.33  4886.9   33.16
  4893.5   33.01  4895.4   27.91  4907.7   23.02  4926.8   17.67  4935.1   12.39
  4953.7    7.61    4975   10.44  4991.1    8.88  5014.7   10.24  5037.7     4.7
  5054.6    4.19  5079.5   21.98  5090.3   21.95  5094.8   26.34  5131.8   42.39
  5142.2   40.48  5193.6   45.55  5243.6   47.37  5423.7   46.23  6248.6   52.01
#Mann= 3 ,-1 , 0
  4050.5      .2       0  4907.7     .06       0  5079.5      .2       0
#XS Ineff= 2 , 0
            4847      48    5300            47.4
Permanent Ineff=
       F       F
Bank Sta=4907.7,5079.5
XS Rating Curve= 0
Exp/Cntr=.5,.3

Type RM Length L Ch R = 1 ,151353.8,986.3,995,691.3
BEGIN DESCRIPTION:
Cross Section 151353.8
END DESCRIPTION:
XS GIS Cut Line= 6
       3093600.3     13841884.05      3093584.95     13841408.07
      3093483.69     13840901.76       3093210.7     13840459.35
      3093230.75     13839993.32      3093205.69     13839331.86
#Sta/Elev= 30
  3735.8   57.45    4212   53.83    4352   49.62    4402   44.42    4462   29.69
    4522   38.91  4571.5   34.96  4717.3   18.15  4859.2   20.29  4878.7   23.58
  4893.8   32.67  4910.1   30.75  4915.1    24.6  4982.9     4.9  5017.2    7.14
  5037.7   14.26  5048.3   23.05  5085.6   27.52  5136.9   20.06  5162.1   22.25
  5190.4   24.94  5206.5   32.78  5249.2   38.43  5369.2    31.3  5419.2    19.3
  5489.2   24.26  5609.2   49.31  5709.2   53.33  6265.7   50.58  6377.6   53.69
#Mann= 5 ,-1 , 0
  3735.8      .2       0  4571.5     .13       0  4893.8     .06       0
  5085.6     .07       0  5162.1      .2       0
#XS Ineff= 2 , 0
            4540    48.3    5246              48
Permanent Ineff=
       F       F
Bank Sta=4893.8,5085.6
XS Rating Curve= 0
Exp/Cntr=.3,.1

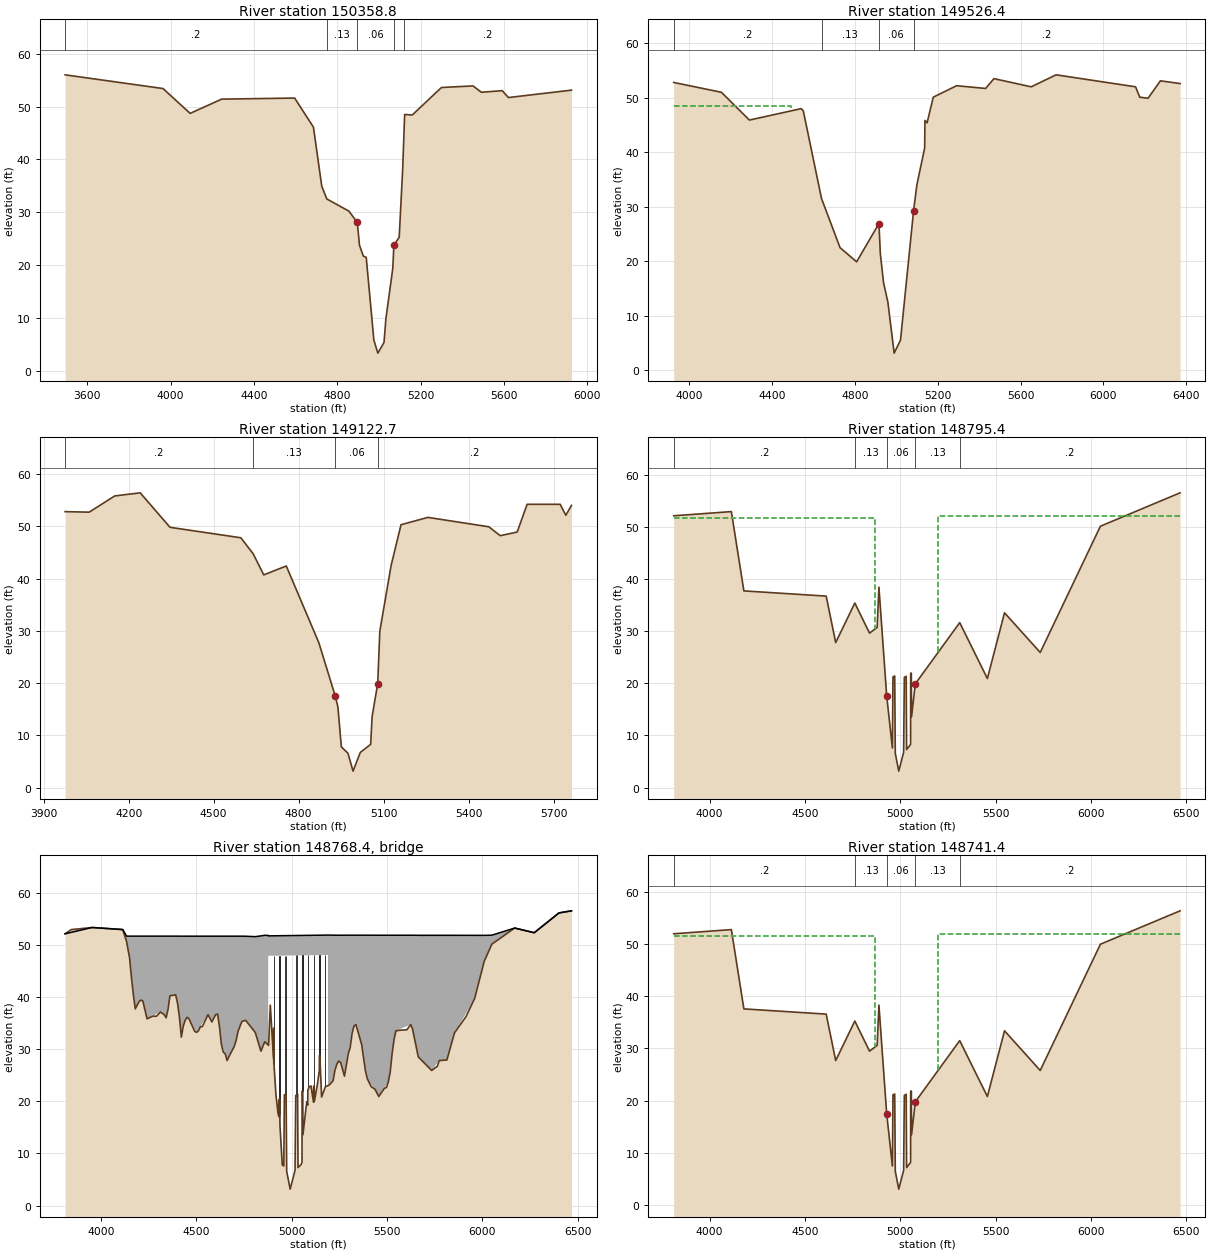
Type RM Length L Ch R = 1 ,150358.8,718.9,832.4,841.7
BEGIN DESCRIPTION:
Cross Section 150358.8
END DESCRIPTION:
XS GIS Cut Line= 6
      3094571.16     13841231.96      3094284.98     13840602.37
      3094034.03     13840192.92      3093637.78     13839950.77
      3093492.49     13839686.61      3093254.75     13839255.14
#Sta/Elev= 30
  3493.8      56  3963.8    53.4  4093.8    48.7  4245.4    51.4  4595.4    51.6
  4685.6    46.1  4725.6    34.9  4749.8    32.5  4855.6    30.2    4896   28.07
  4906.6   23.73  4925.1   21.67  4938.9   21.44  4975.7    5.77  4994.7    3.31
  5024.3    5.33  5033.3    9.79  5066.4   19.36  5071.7   23.74  5097.2   25.25
  5113.9   38.14  5119.5   44.24  5123.4   48.49    5160    48.4    5300    53.6
  5451.5    53.9  5491.5    52.7  5591.5      53  5621.5    51.7  5924.1    53.1
#Mann= 5 ,-1 , 0
  3493.8      .2       0  4749.8     .13       0    4896     .06       0
  5071.7      .1       0  5119.5      .2       0
Bank Sta=4896,5071.7
XS Rating Curve= 0
Exp/Cntr=.3,.1

Type RM Length L Ch R = 1 ,149526.4,267,403.7,444.8
BEGIN DESCRIPTION:
Cross Section 149526.4
END DESCRIPTION:
XS GIS Cut Line= 6
      3094925.14     13840657.41      3094875.83     13840396.77
      3094650.41     13839942.41      3094301.71     13839463.39
      3093928.36     13839001.99      3093753.66     13838549.74
#Sta/Elev= 30
  3926.7    52.8  4156.7      51    4292    45.9    4542      48    4552    47.6
  4639.8   31.52  4729.2    22.5  4809.2    19.9    4917   26.92  4923.7   21.37
  4939.2   16.07  4960.2   12.48  4990.3    3.15    5021    5.54  5084.1   29.27
  5099.7   33.96  5137.5   40.77  5138.9   45.83  5149.2    45.4  5179.2    50.1
  5291.7    52.2  5431.7    51.7  5471.7    53.5  5651.7      52  5771.7    54.2
  6155.2      52  6175.2    50.1  6215.2    49.9  6275.2    53.1    6370    52.6
#Mann= 4 ,-1 , 0
  3926.7      .2       0  4639.8     .13       0    4917     .06       0
  5084.1      .2       0
#XS Ineff= 2 , 0
            4492    48.4
Permanent Ineff=
       F       F
Bank Sta=4917,5084.1
XS Rating Curve= 0
Exp/Cntr=.3,.1

Type RM Length L Ch R = 1 ,149122.7,220.6,327.3,332.9
BEGIN DESCRIPTION:
Cross Section 149122.7 - Interpolated
END DESCRIPTION:
XS GIS Cut Line= 6
      3094956.95     13840616.22       3094991.7     13840348.15
      3094912.27     13839975.83      3094902.35     13839856.69
      3094827.88      13839494.3      3094514.92     13838928.52
#Sta/Elev= 30
  3975.8    52.8  4060.8    52.7  4150.8    55.8  4240.8    56.4  4346.1    49.8
  4596.1    47.8  4639.8   44.71  4676.8    40.7  4756.4    42.4  4871.4    27.7
  4928.8   17.58  4938.5   15.45  4950.7    7.79  4973.9    6.58    4992    3.15
  5017.6    6.73  5054.2    8.28  5059.2   13.59    5079   19.89  5086.4    29.9
  5126.3    42.5  5161.3    50.3  5256.3    51.7  5471.3    49.9  5511.3    48.2
  5571.3    48.9  5606.3    54.2  5722.9    54.2  5742.9    52.1  5762.9      54
#Mann= 4 ,-1 , 0
  3975.8      .2       0  4639.8     .13       0  4928.8     .06       0
    5079      .2       0
Bank Sta=4928.8,5079
XS Rating Curve= 0
Exp/Cntr=.5,.3

Type RM Length L Ch R = 1 ,148795.4,54,54,54
BEGIN DESCRIPTION:
Upstream Section of Bridge/Culvert/Weir
END DESCRIPTION:
XS GIS Cut Line= 6
      3095123.89     13840746.52      3095168.97     13839535.38
      3095189.26     13839258.11      3095197.93     13839024.04
      3095227.12     13838517.05      3095242.83     13838092.67
#Sta/Elev= 30
  3811.4    52.1  4113.9    52.9  4179.5    37.7  4611.3    36.7  4661.3    27.8
  4761.6   35.37  4838.8    29.6  4878.8    30.7    4888   38.42  4928.8   17.58
  4958.7    7.58  4961.8   21.23  4970.8   21.39  4973.9    6.58    4992    3.15
  5017.6    6.73  5021.4   21.12  5031.1   21.34  5033.3    7.28  5054.2    8.28
  5054.7   21.94  5058.1   21.94  5059.2   13.59    5079   19.89  5311.9   31.62
    5457    20.9    5547    33.5  5734.3    25.9  6050.1    50.1  6468.1    56.5
#Mann= 5 ,-1 , 0
  3811.4      .2       0  4761.6     .13       0  4928.8     .06       0
    5079     .13       0  5311.9      .2       0
#XS Ineff= 2 , 0
            4865    51.6    5200              52
Permanent Ineff=
       F       F
Bank Sta=4928.8,5079
XS Rating Curve= 0
Exp/Cntr=.5,.3

Type RM Length L Ch R = 3 ,148768.4,,,
BEGIN DESCRIPTION:
SOUTHERN PACIFIC RAILROAD
Structure ID: WOO-50
END DESCRIPTION:
Bridge Culvert--1,0,-1,-1, 0
Deck Dist Width WeirC Skew NumUp NumDn MinLoCord MaxHiCord MaxSubmerge Is_Ogee
10,34,2.6,0, 60, 60, , , .95, 0, 1,1,,
  3811.4  3953.9  4113.9  4133.9  4149.5  4179.5  4209.5  4219.5  4241.3  4311.3
  4341.3  4361.3  4391.3  4401.3  4421.3  4431.3  4451.3  4501.3  4561.3  4581.3
  4611.3  4631.3  4661.3  4698.8  4738.8  4758.8  4808.8  4838.8  4858.8 4876.91
    4877 5190.69  5190.8    5217    5227    5247    5277    5317    5337    5367
    5387    5397    5457    5507    5517    5537    5547  5624.3  5664.3  5734.3
  5774.3  5814.3  5854.3  5960.1  6010.1  6050.1  6170.1  6272.5  6402.5  6468.1
    52.1   53.31   52.91   51.65   51.65   51.65   51.65   51.65   51.65   51.65
   51.65   51.65   51.65   51.65   51.64   51.64   51.64   51.64   51.64   51.64
   51.64   51.64   51.64   51.64   51.64   51.63   51.55    51.7   51.81   51.79
    51.7   51.85   51.85   51.84   51.82   51.82   51.83   51.83   51.83   51.83
   51.83   51.83   51.82   51.82   51.82   51.82   51.82   51.82   51.81   51.81
   51.81   51.81   51.81    51.8    51.8   51.83    53.2    52.3    56.1    56.5
    52.1    53.3    52.9    50.6    47.5    37.7    39.4    39.2    35.8    37.1
      36    40.2    40.4    38.8    32.3    34.4    36.1    33.2    36.6    35.2
    36.7    30.9    27.8    30.5    35.3    35.5    33.2    29.6    31.4   30.77
   47.88   48.03   23.01    23.9    25.9    27.7    24.8      33    34.7    30.9
    25.8    24.3    20.9    23.7    25.6    31.8    33.5    34.7    28.5    25.9
    27.8    27.9    33.1    39.7    46.8    50.1    53.2    52.3    56.1    56.5
  3811.4  3953.9  4113.9  4133.9  4149.5  4179.5  4209.5  4219.5  4241.3  4311.3
  4341.3  4361.3  4391.3  4401.3  4421.3  4431.3  4451.3  4501.3  4561.3  4581.3
  4611.3  4631.3  4661.3  4698.8  4738.8  4758.8  4808.8  4838.8  4858.8 4876.91
    4877 5190.69  5190.8    5217    5227    5247    5277    5317    5337    5367
    5387    5397    5457    5507    5517    5537    5547  5624.3  5664.3  5734.3
  5774.3  5814.3  5854.3  5960.1  6010.1  6050.1  6170.1  6272.5  6402.5  6468.1
    52.1   53.31   52.91   51.65   51.65   51.65   51.65   51.65   51.65   51.65
   51.65   51.65   51.65   51.65   51.64   51.64   51.64   51.64   51.64   51.64
   51.64   51.64   51.64   51.64   51.64   51.63   51.55    51.7   51.81   51.79
    51.7   51.85   51.85   51.84   51.82   51.82   51.83   51.83   51.83   51.83
   51.83   51.83   51.82   51.82   51.82   51.82   51.82   51.82   51.81   51.81
   51.81   51.81   51.81    51.8    51.8   51.83    53.2    52.3    56.1    56.5
   52.03   53.23   52.83   50.53   47.43   37.63   39.33   39.13   35.73   37.03
   35.93   40.13   40.33   38.73   32.23   34.33   36.03   33.13   36.53   35.13
   36.63   30.83   27.73   30.43   35.23   35.43   33.13   29.53   31.33    30.7
   47.81   47.96   22.94   23.83   25.83   27.63   24.73   32.93   34.63   30.83
   25.73   24.23   20.83   23.63   25.53   31.73   33.43   34.63   28.43   25.83
   27.73   27.83   33.03   39.63   46.73   50.03   53.13   52.23   56.03   56.43
Pier Skew, UpSta & Num, DnSta & Num=  ,4906.4, 2 ,4906.4, 2 , 0 , 0 , 0 ,,
       2       2
   30.37   48.88
       2       2
    30.3   48.81
Pier Skew, UpSta & Num, DnSta & Num=  ,4936, 2 ,4936, 2 , 0 , 0 , 0 ,,
       2       2
   17.91   48.98
       2       2
   17.84   48.91
Pier Skew, UpSta & Num, DnSta & Num=  ,4964.2, 2 ,4964.2, 2 , 0 , 0 , 0 ,,
       2       2
   20.26   49.07
       2       2
   20.19      49
Pier Skew, UpSta & Num, DnSta & Num=  ,4968.9, 2 ,4968.9, 2 , 0 , 0 , 0 ,,
       2       2
   20.29   49.09
       2       2
   20.22   49.02
Pier Skew, UpSta & Num, DnSta & Num=  ,5024.3, 2 ,5024.3, 2 , 0 , 0 , 0 ,,
       2       2
   20.11   49.17
       2       2
   20.04    49.1
Pier Skew, UpSta & Num, DnSta & Num=  ,5028.5, 2 ,5028.5, 2 , 0 , 0 , 0 ,,
       2       2
   20.13   49.17
       2       2
   20.06    49.1
Pier Skew, UpSta & Num, DnSta & Num=  ,5056.7, 2 ,5056.7, 2 , 0 , 0 , 0 ,,
       2       2
   20.92   49.15
       2       2
   20.85   49.08
Pier Skew, UpSta & Num, DnSta & Num=  ,5087, 2 ,5087, 2 , 0 , 0 , 0 ,,
       2       2
   21.22   49.13
       2       2
   21.15   49.06
Pier Skew, UpSta & Num, DnSta & Num=  ,5116.6, 2 ,5116.6, 2 , 0 , 0 , 0 ,,
       2       2
   21.88    49.1
       2       2
   21.81   49.03
Pier Skew, UpSta & Num, DnSta & Num=  ,5146.7, 2 ,5146.7, 2 , 0 , 0 , 0 ,,
       2       2
   27.72   49.07
       2       2
   27.65      49
Pier Skew, UpSta & Num, DnSta & Num=  ,5176.4, 2 ,5176.4, 2 , 0 , 0 , 0 ,,
       2       2
   21.64   49.04
       2       2
   21.57   48.97
Abutment Skew #Up #Dn= , 2 , 2
  4876.8  4917.8
   47.88   21.08
  4876.8  4917.8
   47.81   21.01
Abutment Skew #Up #Dn= , 2 , 2
  5135.3 5190.89
    23.3   48.03
  5135.3 5190.89
   23.23   47.96
BR Coef= 1 , 1 , 0 ,1.25, 0 ,,,.8,0,2,0,
WSPro=,,,, 1 ,,,, 0 ,,,, 0 ,,,,-1 ,-1 ,-1 , 0 , 0 , 0 , 0 , 0
BR U #Sta/Elev= 179
  3811.4    52.1  3843.9    52.9  3953.9    53.3  4001.4   53.18  4061.4   53.03
  4099.9   52.94  4113.9    52.9  4133.9    50.6  4149.5    47.5  4159.5    43.7
  4169.5    40.4  4179.5    37.7  4199.5    39.1  4209.5    39.4  4219.5    39.2
  4221.3    38.9  4241.3    35.8  4271.3    36.3  4291.3    36.3  4311.3    37.1
  4331.3    36.6  4341.3      36  4351.3    37.6  4361.3    40.2  4391.3    40.4
  4401.3    38.8  4411.3    36.1  4421.3    32.3  4431.3    34.4  4441.3    35.5
  4451.3    36.1  4461.3    35.8  4491.3    33.4  4501.3    33.2  4511.3    33.5
  4521.3    34.3  4531.3    34.3  4561.3    36.6  4581.3    35.2  4601.3    36.6
  4611.3    36.7  4621.3    34.3  4631.3    30.9  4641.3    29.4  4651.3    29.1
  4661.3    27.8  4668.8    28.4  4698.8    30.5  4708.8    31.7  4718.8    33.4
 4727.09   34.19  4727.2    34.2 4727.31   34.21  4738.8    35.3  4754.3   35.45
  4758.8    35.5  4761.6   35.37  4808.8    33.2  4808.9   33.19  4838.8    29.6
  4858.8    31.4  4876.8   30.77 4876.91   30.77    4877   30.76  4877.1   30.76
  4878.8    30.7    4888   38.42  4904.9   28.09  4905.8      34  4906.4   27.22
    4907    33.9  4908.2   26.52  4917.7   21.11  4917.8   21.08  4928.8   17.58
  4934.6   16.97  4935.3   20.37    4936   17.55  4937.5   20.32  4938.5   15.45
  4950.7    7.79  4958.7    7.58  4961.8   21.23  4964.3   21.28  4968.9   21.29
  4970.8   21.39  4973.9    6.58    4992    3.15  5001.2    4.44  5017.6    6.73
  5021.4   21.12  5024.3   21.11  5028.5   21.13  5031.1   21.34  5033.3    7.28
  5049.4    7.87  5054.2    8.28  5054.7   21.94  5056.7    21.9  5058.1   21.94
  5059.2   13.59    5079   19.89  5084.2   19.26  5084.9   22.16    5087   22.27
  5088.9   22.38  5089.8   22.64  5090.1   22.73  5101.3   22.94  5114.7    19.8
  5115.3   22.86  5116.6   22.93  5118.1   22.89  5119.1   19.94  5135.2   23.28
  5135.3    23.3  5145.1   25.85  5145.6   28.75  5146.7   28.78  5147.6   28.78
  5148.2   28.39    5157    20.8    5177    22.8 5190.69   23.01  5190.8   23.01
  5190.9   23.01    5191   23.01    5197    23.1    5217    23.9    5227    25.9
    5233   26.62    5237    27.1    5247    27.7    5257    27.4    5277    24.8
  5278.8   25.19 5278.89   25.21    5279   25.23 5279.11   25.25    5297    29.1
    5307    30.3  5311.9   31.62    5317      33    5327    34.4    5337    34.7
    5367    30.9    5387    25.8    5397    24.3    5417    22.8    5437    22.3
    5457    20.9    5487    22.5    5497    22.6    5507    23.7    5517    25.6
    5527    29.1    5537    31.8    5547    33.5  5564.3    33.6  5604.3    33.7
  5624.3    34.7  5634.3    33.8  5664.3    28.5  5734.3    25.9  5764.3    26.7
  5774.3    27.8  5814.3    27.9  5854.3    33.1  5914.3    36.2  5960.1    39.7
  6010.1    46.8  6047.9   49.92  6050.1    50.1  6085.6   51.02  6085.9   51.02
  6170.1    53.2  6272.5    52.3  6402.5    56.1  6468.1    56.5
BR U #Mann= 5
  3811.4      .2  4761.6     .13  4928.8     .06    5079     .13  5311.9      .2
BR U Banks=4928.8,5079
BR D #Sta/Elev= 179
  3811.4   52.03  3843.9   52.83  3953.9   53.23  4001.4   53.11  4061.4   52.96
  4099.9   52.87  4113.9   52.83  4133.9   50.53  4149.5   47.43  4159.5   43.63
  4169.5   40.33  4179.5   37.63  4199.5   39.03  4209.5   39.33  4219.5   39.13
  4221.3   38.83  4241.3   35.73  4271.3   36.23  4291.3   36.23  4311.3   37.03
  4331.3   36.53  4341.3   35.93  4351.3   37.53  4361.3   40.13  4391.3   40.33
  4401.3   38.73  4411.3   36.03  4421.3   32.23  4431.3   34.33  4441.3   35.43
  4451.3   36.03  4461.3   35.73  4491.3   33.33  4501.3   33.13  4511.3   33.43
  4521.3   34.23  4531.3   34.23  4561.3   36.53  4581.3   35.13  4601.3   36.53
  4611.3   36.63  4621.3   34.23  4631.3   30.83  4641.3   29.33  4651.3   29.03
  4661.3   27.73  4668.8   28.33  4698.8   30.43  4708.8   31.63  4718.8   33.33
 4727.09   34.12  4727.2   34.13 4727.31   34.14  4738.8   35.23  4754.3   35.38
  4758.8   35.43  4761.6    35.3  4808.8   33.13  4808.9   33.12  4838.8   29.53
  4858.8   31.33  4876.8    30.7 4876.91    30.7    4877   30.69  4877.1   30.69
  4878.8   30.63    4888   38.35  4904.9   28.02  4905.8   33.93  4906.4   27.15
    4907   33.83  4908.2   26.45  4917.7   21.04  4917.8   21.01  4928.8   17.51
  4934.6    16.9  4935.3    20.3    4936   17.48  4937.5   20.25  4938.5   15.38
  4950.7    7.72  4958.7    7.51  4961.8   21.16  4964.3   21.21  4968.9   21.22
  4970.8   21.32  4973.9    6.51    4992    3.08  5001.2    4.37  5017.6    6.66
  5021.4   21.05  5024.3   21.04  5028.5   21.06  5031.1   21.27  5033.3    7.21
  5049.4     7.8  5054.2    8.21  5054.7   21.87  5056.7   21.83  5058.1   21.87
  5059.2   13.52    5079   19.82  5084.2   19.19  5084.9   22.09    5087    22.2
  5088.9   22.31  5089.8   22.57  5090.1   22.66  5101.3   22.87  5114.7   19.73
  5115.3   22.79  5116.6   22.86  5118.1   22.82  5119.1   19.87  5135.2   23.21
  5135.3   23.23  5145.1   25.78  5145.6   28.68  5146.7   28.71  5147.6   28.71
  5148.2   28.32    5157   20.73    5177   22.73 5190.69   22.94  5190.8   22.94
  5190.9   22.94    5191   22.94    5197   23.03    5217   23.83    5227   25.83
    5233   26.55    5237   27.03    5247   27.63    5257   27.33    5277   24.73
  5278.8   25.12 5278.89   25.14    5279   25.16 5279.11   25.18    5297   29.03
    5307   30.23  5311.9   31.55    5317   32.93    5327   34.33    5337   34.63
    5367   30.83    5387   25.73    5397   24.23    5417   22.73    5437   22.23
    5457   20.83    5487   22.43    5497   22.53    5507   23.63    5517   25.53
    5527   29.03    5537   31.73    5547   33.43  5564.3   33.53  5604.3   33.63
  5624.3   34.63  5634.3   33.73  5664.3   28.43  5734.3   25.83  5764.3   26.63
  5774.3   27.73  5814.3   27.83  5854.3   33.03  5914.3   36.13  5960.1   39.63
  6010.1   46.73  6047.9   49.85  6050.1   50.03  6085.6   50.95  6085.9   50.95
  6170.1   53.13  6272.5   52.23  6402.5   56.03  6468.1   56.43
BR D #Mann= 5
  3811.4      .2  4761.6     .13  4928.8     .06    5079     .13  5311.9      .2
BR D Banks=4928.8,5079
BC Design=,, 0 ,, 0 ,,,,,,
BC HTab HWMax=56.5

Type RM Length L Ch R = 1 ,148741.4,1109,1109,1109
BEGIN DESCRIPTION:
Downstream Section of Bridge/Culvert/Weir
END DESCRIPTION:
XS GIS Cut Line= 6
      3095177.23     13840754.98      3095222.31     13839543.84
       3095242.6     13839266.57      3095251.27      13839032.5
      3095280.46     13838525.51      3095296.16     13838101.14
#Sta/Elev= 30
  3811.4   51.99  4113.9   52.79  4179.5   37.59  4611.3   36.59  4661.3   27.69
  4761.6   35.26  4838.8   29.49  4878.8   30.59    4888   38.31  4928.8   17.47
  4958.7    7.47  4961.8   21.12  4970.8   21.28  4973.9    6.47    4992    3.04
  5017.6    6.62  5021.4   21.01  5031.1   21.23  5033.3    7.17  5054.2    8.17
  5054.7   21.83  5058.1   21.83  5059.2   13.48    5079   19.78  5311.9   31.51
    5457   20.79    5547   33.39  5734.3   25.79  6050.1   49.99  6468.1   56.39
#Mann= 5 ,-1 , 0
  3811.4      .2       0  4761.6     .13       0  4928.8     .06       0
    5079     .13       0  5311.9      .2       0
#XS Ineff= 2 , 0
            4865    51.6    5200              52
Permanent Ineff=
       F       F
Bank Sta=4928.8,5079
XS Rating Curve= 0
Exp/Cntr=.5,.3

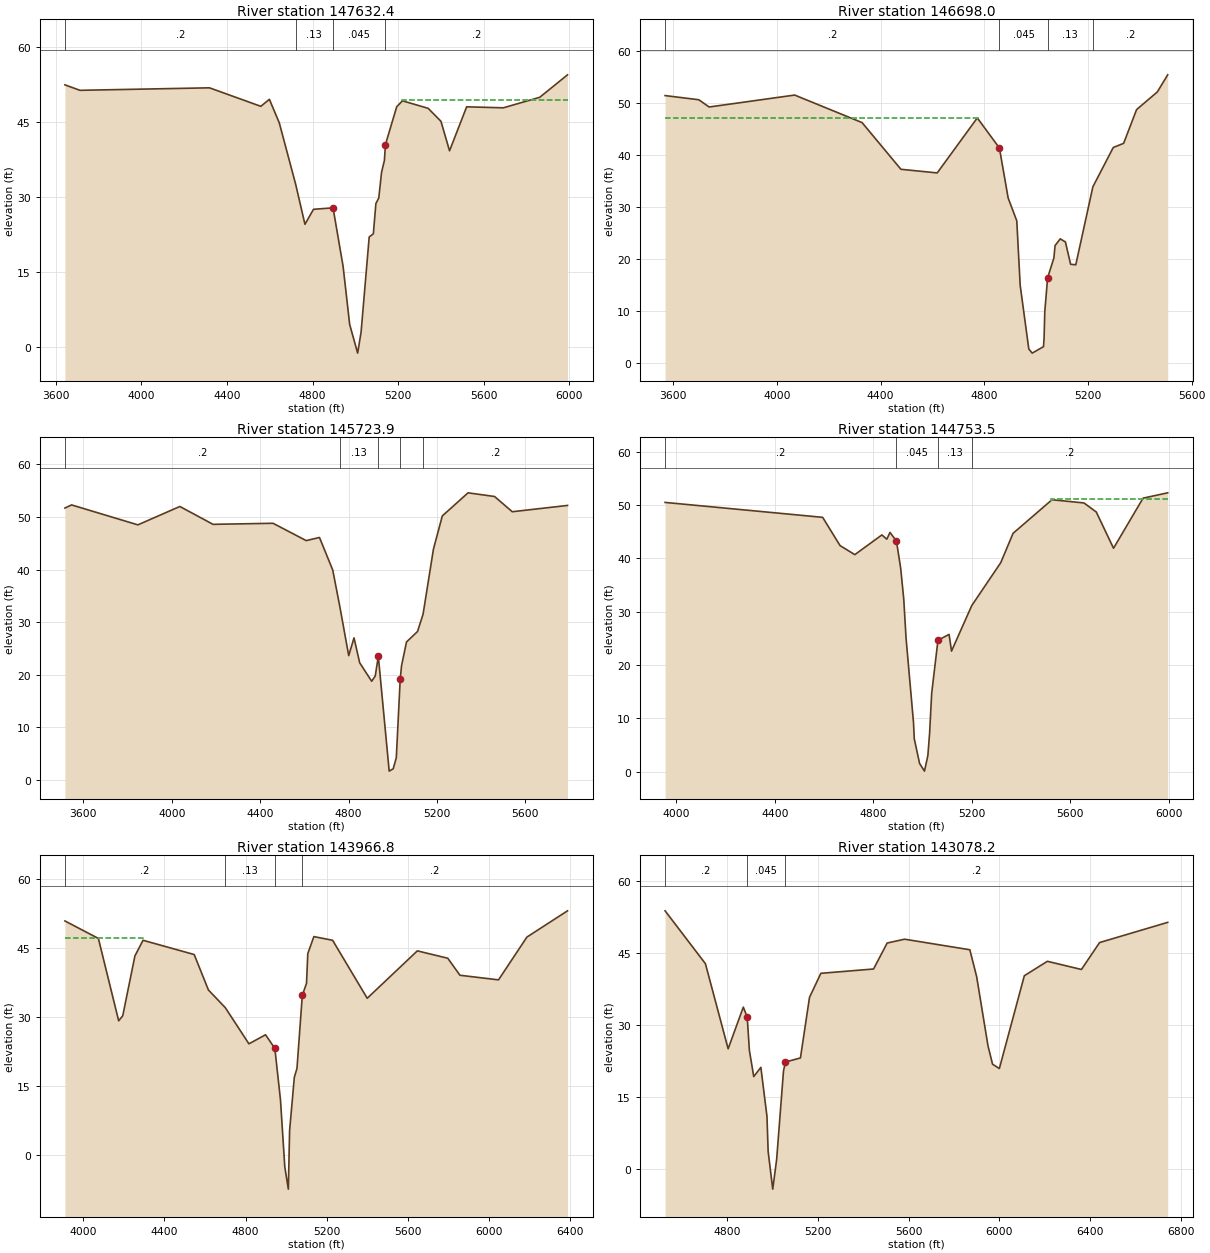
Type RM Length L Ch R = 1 ,147632.4,772.6,934.4,929
BEGIN DESCRIPTION:
Cross Section 147632.4
END DESCRIPTION:
XS GIS Cut Line= 6
      3096418.74     13840089.69      3096287.17     13839570.72
      3096177.53     13839117.54      3095804.75     13838678.98
       3095614.7     13838247.72      3095505.75     13837968.23
#Sta/Elev= 30
  3642.7    52.5  3712.7    51.4  4318.1    51.9  4558.1    48.2  4598.1    49.6
  4644.3    44.9  4720.6   32.66  4764.3    24.6  4804.3    27.6  4895.6   27.89
  4942.5   16.19  4973.3    4.56  5010.6   -1.17  5026.6    3.04  5064.5   22.07
  5083.8   22.69  5095.8   28.75  5109.2   29.86  5122.3      35  5135.5   37.36
  5140.4   40.55  5193.1   48.12  5219.9    49.3  5339.9    47.8  5399.9    45.2
  5439.9    39.3  5519.9    48.1  5691.2    47.9  5861.2      50  5991.2    54.5
#Mann= 4 ,-1 , 0
  3642.7      .2       0  4720.6     .13       0  4895.6    .045       0
  5140.4      .2       0
#XS Ineff= 2 , 0
                            5220            49.5
Permanent Ineff=
       F       F
Bank Sta=4895.6,5140.4
XS Rating Curve= 0
Exp/Cntr=.3,.1

Type RM Length L Ch R = 1 ,146698.0,619,974.1,1120.3
BEGIN DESCRIPTION:
Cross Section 146698.0
END DESCRIPTION:
XS GIS Cut Line= 4
      3096557.61     13840170.09      3096952.32     13839095.61
      3096798.82     13838657.05      3096788.98     13838327.21
#Sta/Elev= 30
  3568.2    51.5  3698.2    50.7  3738.2    49.3  4068.2    51.6  4328.2    46.3
  4478.2    37.3  4618.2    36.6  4772.9    47.2  4858.2    41.4  4891.9   31.78
  4925.2   27.37  4938.3   14.96  4971.6    2.68  4984.7    1.88  5028.3    3.13
  5030.6    4.84  5033.2    9.82  5044.1   16.38  5068.4   20.21  5072.9    22.6
  5092.9    23.9  5112.9    23.3  5132.9      19  5152.9    18.9  5218.8   33.92
  5297.5    41.5  5337.5    42.3  5387.5    48.8  5467.5    52.2  5507.5    55.5
#Mann= 4 ,-1 , 0
  3568.2      .2       0  4858.2    .045       0  5044.1     .13       0
  5218.8      .2       0
#XS Ineff= 2 , 0
            4776    47.2
Permanent Ineff=
       F       F
Bank Sta=4858.2,5044.1
XS Rating Curve= 0
Exp/Cntr=.3,.1

Type RM Length L Ch R = 1 ,145723.9,1033.3,970.4,844.7
BEGIN DESCRIPTION:
Cross Section 145723.9
END DESCRIPTION:
XS GIS Cut Line= 6
      3096586.85     13840287.04      3097213.53     13839584.13
      3097289.93      13839313.1       3097632.1     13839117.54
      3097727.12     13838993.28      3098066.61     13838626.08
#Sta/Elev= 30
  3516.8    51.7  3546.8    52.3  3846.8    48.5  4036.8      52  4186.8    48.6
  4458.5    48.8  4608.5    45.5  4668.5    46.1  4728.5    39.9  4761.2    32.8
  4800.8    23.6  4824.7   26.99  4850.4   22.24  4904.7   18.72  4920.8   19.72
  4934.7   23.49  4983.9    1.61  5002.1    2.06  5016.1    4.18  5033.7    19.1
  5039.7   21.65  5062.2    26.2  5112.2    28.2  5137.2    31.5  5184.2    43.9
  5224.2    50.2  5340.7    54.6  5460.7    53.9  5540.7      51  5790.7    52.2
#Mann= 5 ,-1 , 0
  3516.8      .2       0  4761.2     .13       0  4934.7    .045       0
  5033.7     .13       0  5137.2      .2       0
Bank Sta=4934.7,5033.7
XS Rating Curve= 0
Exp/Cntr=.3,.1

Type RM Length L Ch R = 1 ,144753.5,341.5,786.7,870.5
BEGIN DESCRIPTION:
Cross Section 144753.5
END DESCRIPTION:
XS GIS Cut Line= 5
      3097177.71     13840592.26      3097785.59     13840308.97
      3097982.95      13840016.6      3098172.99     13839621.89
        3098389.      13839083.7
#Sta/Elev= 30
  3954.8    50.5  4594.8    47.7  4665.4    42.4  4725.4    40.7  4835.4    44.4
  4855.4    43.6  4868.3   44.87  4894.4   43.26  4911.6   38.19  4924.2   32.34
  4933.6   24.98  4963.8    9.18  4966.9    6.15  4988.4    1.52  5008.3     .07
  5022.1       3  5029.2    7.21  5037.6   14.68  5063.1   24.63  5108.3   25.73
  5118.2    22.6  5200.5   31.15  5318.2    39.2  5368.2    44.7  5526.2      51
  5656.2    50.4  5706.2    48.7  5776.2    41.9  5896.2    51.3  5996.2    52.3
#Mann= 4 ,-1 , 0
  3954.8      .2       0  4894.4    .045       0  5063.1     .13       0
  5200.5      .2       0
#XS Ineff= 2 , 0
                            5522            51.2
Permanent Ineff=
       F       F
Bank Sta=4894.4,5063.1
XS Rating Curve= 0
Exp/Cntr=.3,.1

Type RM Length L Ch R = 1 ,143966.8,1050.6,888.6,632.6
BEGIN DESCRIPTION:
Cross Section 143966.8
END DESCRIPTION:
XS GIS Cut Line= 6
      3097401.92     13840563.89      3097997.56     13840338.21
       3098260.7     13840279.73      3098582.32     13840301.66
      3098655.41     13840170.09      3098904.07     13839102.35
#Sta/Elev= 30
  3909.9    50.8  4074.8      47  4174.8    29.1  4194.8    30.2  4254.8    43.2
  4294.8    46.6  4546.9    43.5  4616.9    35.8  4700.1   31.96  4816.5    24.1
  4898.4   26.07  4944.3    23.1    4972    11.9  4993.2   -2.63  5010.7   -7.47
  5016.9    5.25  5040.1    16.8  5053.3   18.78  5079.4   34.61  5100.3   37.27
  5106.5    43.7  5136.5    47.4  5228.8    46.6  5399.3      34  5646.2    44.3
  5796.2    42.7  5856.2      39  6046.2      38  6186.2    47.3  6386.2      53
#Mann= 4 ,-1 , 0
  3909.9      .2       0  4700.1     .13       0  4944.3    .045       0
  5079.4      .2       0
#XS Ineff= 2 , 0
            4295      47
Permanent Ineff=
       F       F
Bank Sta=4944.3,5079.4
XS Rating Curve= 0
Exp/Cntr=.3,.1

Type RM Length L Ch R = 1 ,143078.2,1089.9,1016.8,910.9
BEGIN DESCRIPTION:
Cross Section 143078.2
END DESCRIPTION:
XS GIS Cut Line= 6
      3098405.86     13841377.56      3098297.25     13840886.41
      3098341.11     13840689.06      3098699.27     13840279.73
      3098779.67     13839855.79      3098950.47     13839354.06
#Sta/Elev= 30
  4527.3    53.7    4705    42.7    4805      25  4871.9   33.67  4889.1   31.59
  4898.6   24.69  4917.8   19.22  4949.2   21.14  4976.1   10.93  4981.3    3.64
  5001.5   -4.19  5018.7    1.98    5049   20.44  5057.7   22.25  5123.5    23.1
  5163.5    35.7  5213.5    40.7  5445.6    41.6  5505.6      47  5582.3    47.8
  5869.8    45.6  5899.8      40  5949.8    25.6  5969.8    21.8  5999.8    20.9
  6109.8    40.2  6211.3    43.2  6361.3    41.5  6441.3    47.1  6741.3    51.3
#Mann= 3 ,-1 , 0
  4527.3      .2       0  4889.1    .045       0  5057.7      .2       0
Bank Sta=4889.1,5057.7
XS Rating Curve= 0
Exp/Cntr=.3,.1