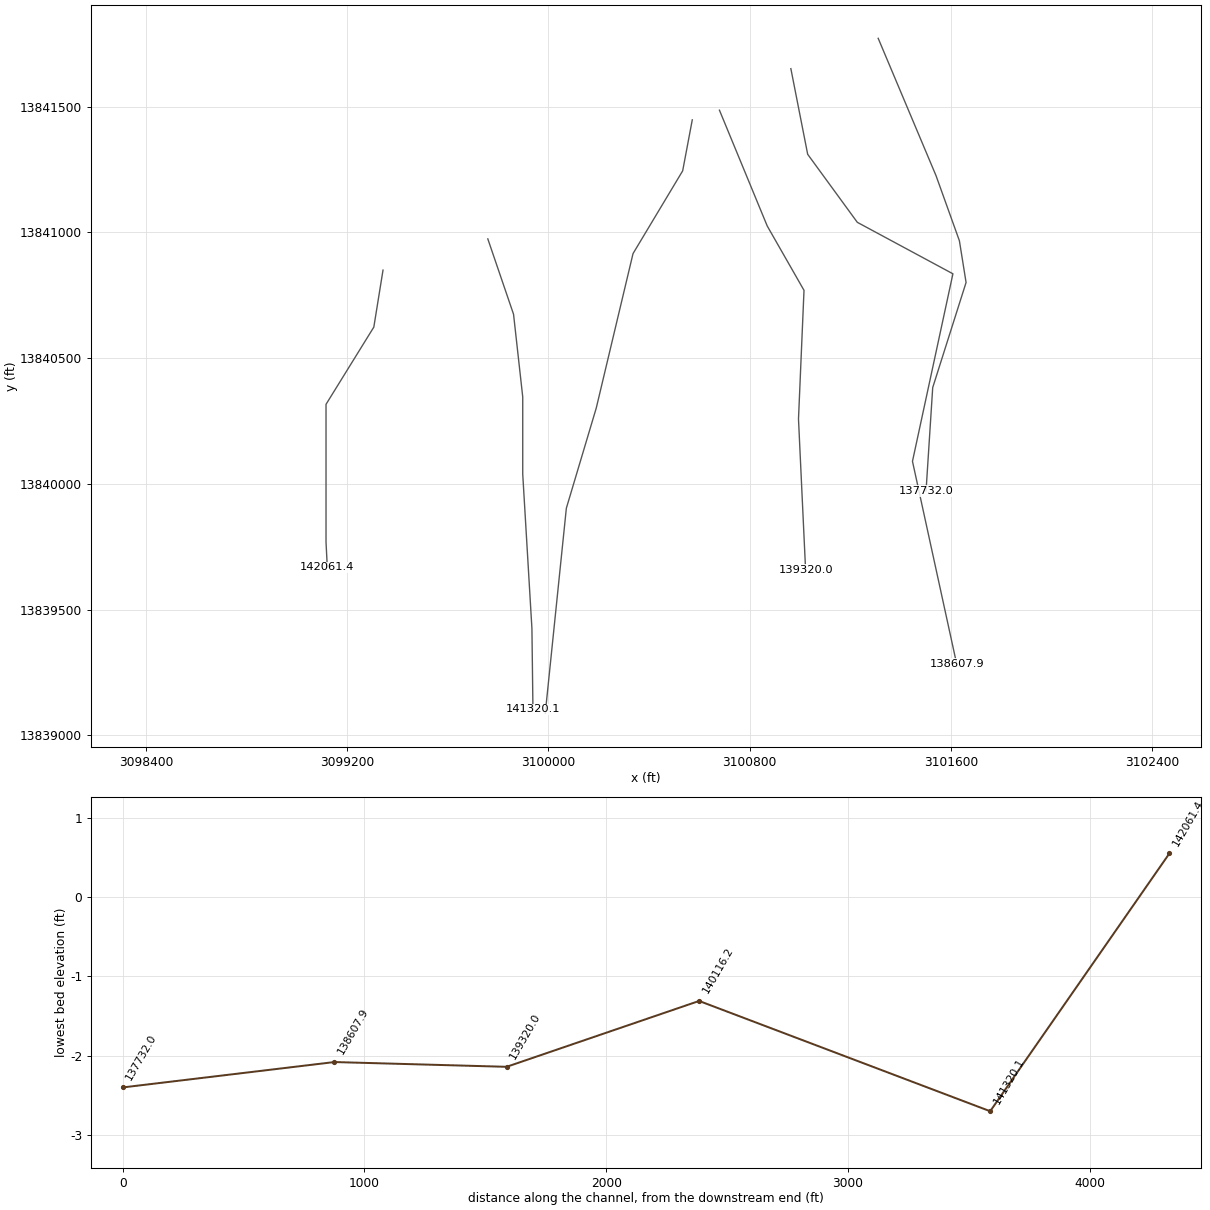
HEC-RAS study W100-00-00.prj: W100-00-00

--- W100-00-00.g01 (geometry) --- (continued)

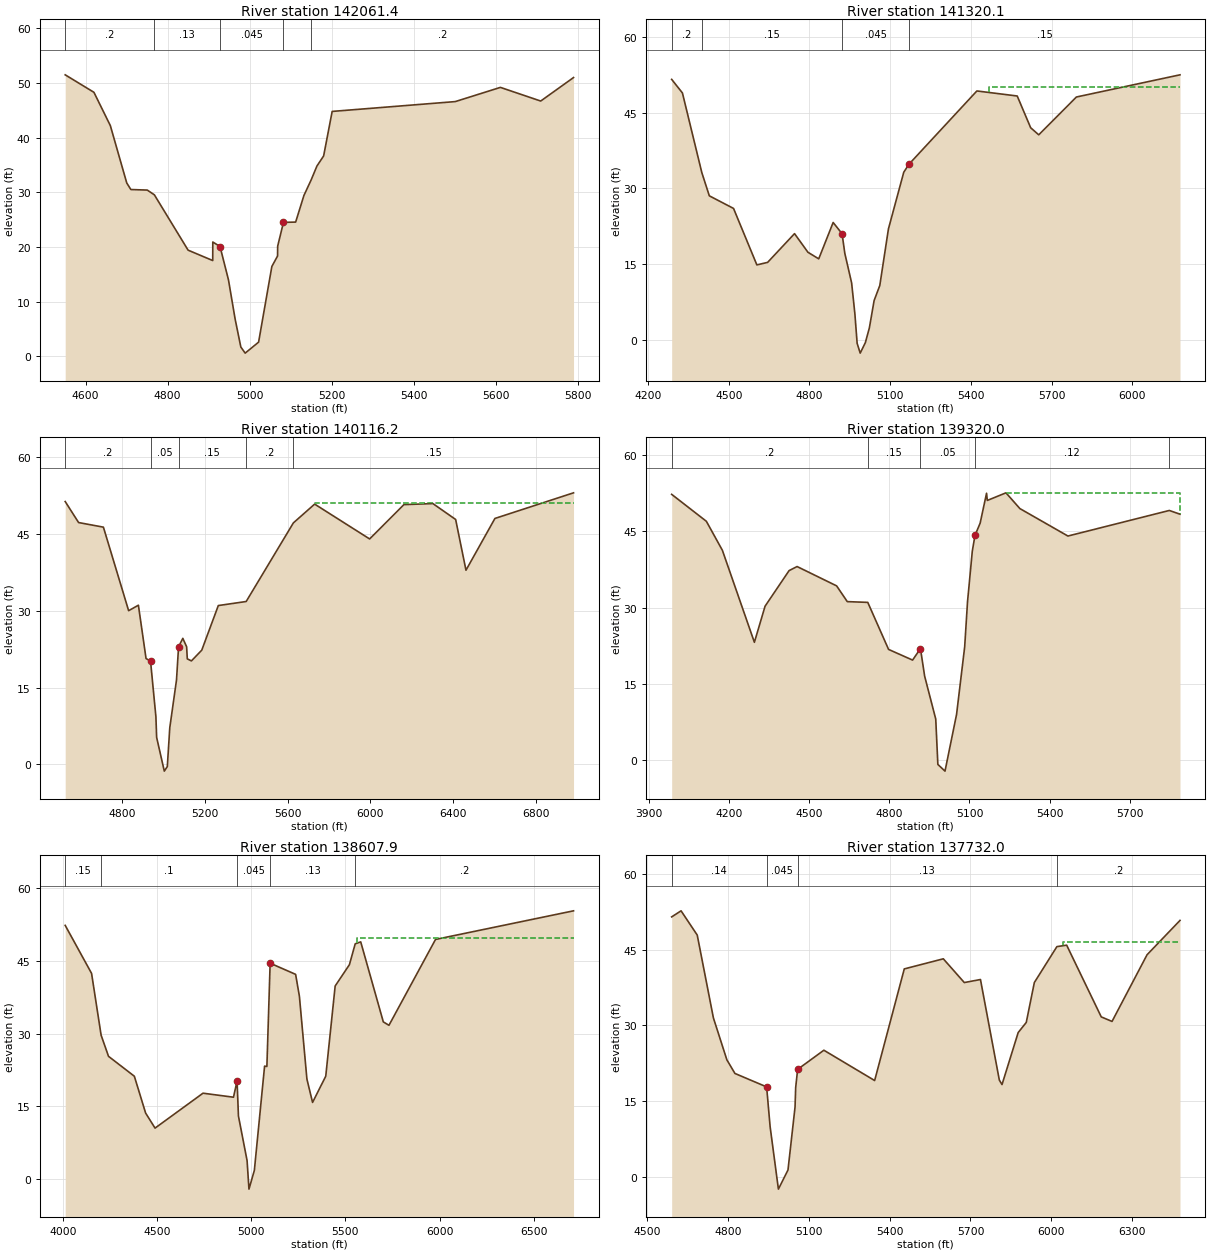
Type RM Length L Ch R = 1 ,142061.4,637.2,741.3,841.4
BEGIN DESCRIPTION:
Cross Section 142061.4
END DESCRIPTION:
XS GIS Cut Line= 6
      3099342.49     13840849.88      3099342.49     13840849.87
      3099305.95     13840623.28       3099115.9     13840316.28
       3099115.9     13839768.08      3099120.97      13839668.2
#Sta/Elev= 30
  4550.3    51.5  4620.3    48.3  4660.3    42.2  4700.3    31.7  4710.3    30.5
  4750.3    30.4  4767.6   29.53  4849.8    19.4  4909.8    17.5    4910   20.89
  4927.6   20.07  4948.2   13.96  4964.5    6.75  4978.3    1.67  4988.9     .55
  5021.6    2.56  5053.9   16.41  5067.8   18.33  5068.1   20.13  5082.2   24.49
  5111.9   24.54    5132    29.4  5149.7   32.26  5163.8   34.81  5180.1   36.65
  5200.9    44.8  5500.9    46.6  5610.9    49.2  5709.1    46.7  5789.1      51
#Mann= 5 ,-1 , 0
  4550.3      .2       0  4767.6     .13       0  4927.6    .045       0
  5082.2     .13       0  5149.7      .2       0
Bank Sta=4927.6,5082.2
XS Rating Curve= 0
Exp/Cntr=.3,.1

Type RM Length L Ch R = 1 ,141320.1,997.5,1203.9,745.8
BEGIN DESCRIPTION:
Cross Section 141320.1
END DESCRIPTION:
XS GIS Cut Line= 6
      3099759.15     13840974.08      3099861.46     13840674.44
      3099898.01     13840345.52      3099898.01     13840038.52
      3099934.55     13839424.54       3099938.6     13839104.51
#Sta/Elev= 30
  4287.8    51.6  4327.8    48.9  4399.9    33.1  4427.8    28.5  4517.8      26
  4604.5    14.8  4644.5    15.3  4744.5      21  4794.5    17.3  4834.5      16
  4888.1   23.21  4921.2   20.99  4931.6   17.06  4956.8   11.22  4968.9     5.1
  4977.3    -.76  4988.7    -2.7  5007.8    -.62  5022.7    2.29  5040.4    7.73
  5061.5   10.71  5093.6   21.93  5150.6   33.18  5169.8   34.76  5422.4    49.3
  5572.4    48.3  5622.4      42  5652.4    40.6  5792.4    48.1  6177.5    52.5
#Mann= 4 ,-1 , 0
  4287.8      .2       0  4399.9     .15       0  4921.2    .045       0
  5169.8     .15       0
#XS Ineff= 2 , 0
                            5467              50
Permanent Ineff=
       F       F
Bank Sta=4921.2,5169.8
XS Rating Curve= 0
Exp/Cntr=.3,.1

Type RM Length L Ch R = 1 ,140116.2,415.5,796.2,807.4
BEGIN DESCRIPTION:
Cross Section 140116.2
END DESCRIPTION:
XS GIS Cut Line= 6
      3100572.12     13841447.37      3100533.92     13841244.57
      3100336.57     13840915.65      3100190.38     13840301.66
      3100071.43     13839903.19      3099987.55     13839087.49
#Sta/Elev= 30
  4524.2    51.3  4588.9    47.2  4708.9    46.3  4830.9      30  4878.1   31.07
    4915   20.67  4936.8   20.16  4962.8    9.28  4966.3    5.27  5003.4   -1.31
  5017.9    -.42  5029.8    7.14  5062.4    16.5  5072.3   22.95  5092.9    24.6
  5111.3   22.96  5114.5    20.6  5134.5    20.2  5184.5    22.3  5264.5      31
  5399.2   31.79  5627.4   47.13  5730.3    50.8  5996.1      44    6162    50.7
    6302    50.9    6412    47.8    6462    37.9    6602      48    6982      53
#Mann= 5 ,-1 , 0
  4524.2      .2       0  4936.8     .05       0  5072.3     .15       0
  5399.2      .2       0  5627.4     .15       0
#XS Ineff= 2 , 0
                            5730              51
Permanent Ineff=
       F       F
Bank Sta=4936.8,5072.3
XS Rating Curve= 0
Exp/Cntr=.3,.1

Type RM Length L Ch R = 1 ,139320.0,366,712.1,787.7
BEGIN DESCRIPTION:
Cross Section 139320.0
END DESCRIPTION:
XS GIS Cut Line= 5
      3100680.13     13841485.72      3100870.15     13841025.29
      3101016.34     13840769.46      3100994.41     13840257.81
      3101022.62     13839658.45
#Sta/Elev= 30
    3984    52.3    4114      47    4174    41.3    4294    23.2    4334    30.3
    4424    37.3    4454    38.1  4602.1    34.3  4642.1    31.2  4718.9   31.05
  4796.8    21.8  4886.8    19.7  4916.3   21.96    4932   16.54  4973.6     8.1
  4981.5    -.82  5008.3   -2.14  5051.6    9.01    5082   22.29  5092.7   31.19
  5110.6   41.14  5120.7   44.23    5140   46.64    5164   52.52  5166.8    51.1
  5236.8    52.6  5288.9    49.5  5468.9    44.1  5848.8   49.13  5888.9    48.4
#Mann= 5 ,-1 , 0
    3984      .2       0  4718.9     .15       0  4916.3     .05       0
  5120.7     .12       0  5848.8      .2       0
#XS Ineff= 2 , 0
                          5236.8            52.6
Permanent Ineff=
       F       F
Bank Sta=4916.3,5120.7
XS Rating Curve= 0
Exp/Cntr=.3,.1

Type RM Length L Ch R = 1 ,138607.9,456.6,875.9,363
BEGIN DESCRIPTION:
Cross Section 138607.9
END DESCRIPTION:
XS GIS Cut Line= 6
      3100964.06     13841650.96      3101030.96     13841310.36
      3101228.31     13841039.91       3101608.4     13840835.25
       3101447.6     13840089.69      3101623.02     13839285.66
#Sta/Elev= 30
  4011.9    52.3  4151.9    42.4  4202.6   29.66  4241.9    25.3    4379    21.2
    4439    13.6    4489    10.5  4743.8    17.7  4905.6   16.87  4924.5   20.22
  4931.9   12.98  4977.7    3.81  4987.7   -2.08  5016.4    1.79  5070.7   23.28
  5082.9   23.21  5100.2    44.5  5235.5    42.2  5255.5    37.7  5295.5    20.6
  5325.5    15.8  5395.5    21.2  5445.5    39.8  5521.2    44.2    5552    48.5
  5581.2    48.9  5701.2    32.4  5731.2    31.7  5978.4    49.4  6711.3    55.3
#Mann= 5 ,-1 , 0
  4011.9     .15       0  4202.6      .1       0  4924.5    .045       0
  5100.2     .13       0    5552      .2       0
#XS Ineff= 2 , 0
                            5560            49.8
Permanent Ineff=
       F       F
Bank Sta=4924.5,5100.2
XS Rating Curve= 0
Exp/Cntr=.3,.1

Type RM Length L Ch R = 1 ,137732.0,902.9,619,405.5
BEGIN DESCRIPTION:
Cross Section 137732.0-Interpolated
END DESCRIPTION:
XS GIS Cut Line= 6
      3101311.34     13841771.43      3101541.34     13841225.21
      3101634.19     13840966.55      3101660.72     13840800.74
      3101528.07     13840382.91      3101501.54     13839971.69
#Sta/Elev= 30
  4590.8    51.5  4625.7    52.7  4685.7    47.9  4745.7    31.5  4795.7    23.2
  4825.7    20.5  4943.3   17.84  4956.3    9.95    4987    -2.4  5022.6    1.39
  5048.8   13.85  5051.1   17.68  5058.4   21.31  5155.8    25.1  5344.3    19.1
  5454.3    41.2  5599.2    43.2  5677.1    38.5  5737.1    39.1  5807.1    19.2
  5817.1    18.3  5877.1    28.6  5907.1    30.6  5937.1    38.5  6020.8   45.61
  6057.1    45.9  6185.5    31.7  6225.5    30.8  6355.5      44  6477.8    50.8
#Mann= 4 ,-1 , 0
  4590.8     .14       0  4943.3    .045       0  5058.4     .13       0
  6020.8      .2       0
#XS Ineff= 2 , 0
                            6045            46.5
Permanent Ineff=
       F       F
Bank Sta=4943.3,5058.4
XS Rating Curve= 0
Exp/Cntr=.3,.1