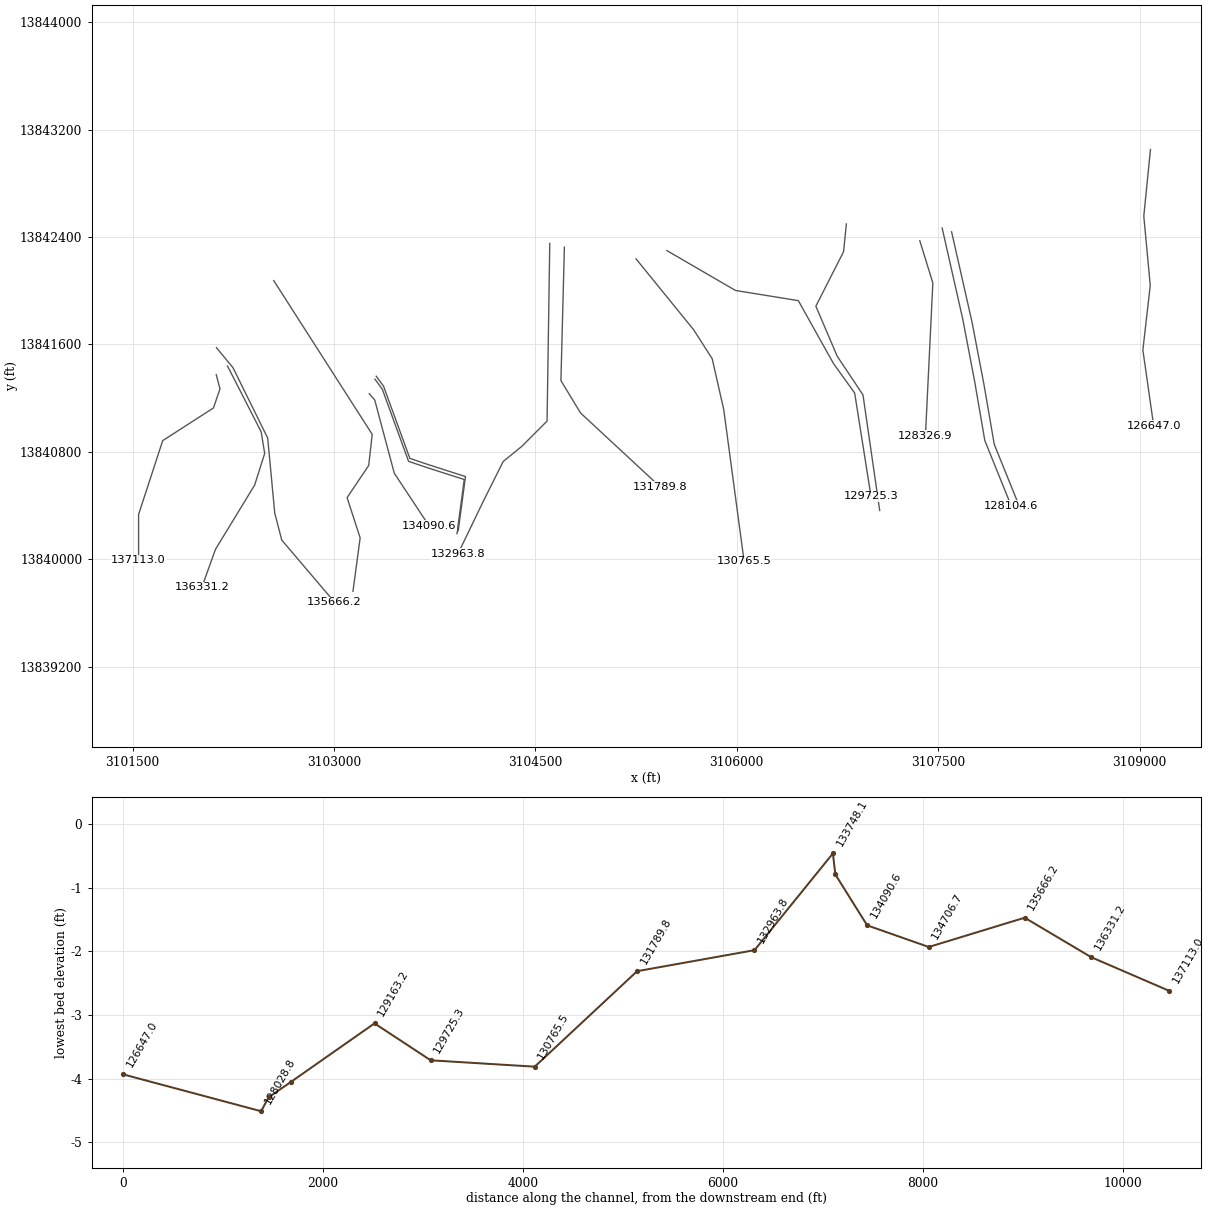
HEC-RAS study W100-00-00.prj: W100-00-00

--- W100-00-00.g01 (geometry) --- (continued)

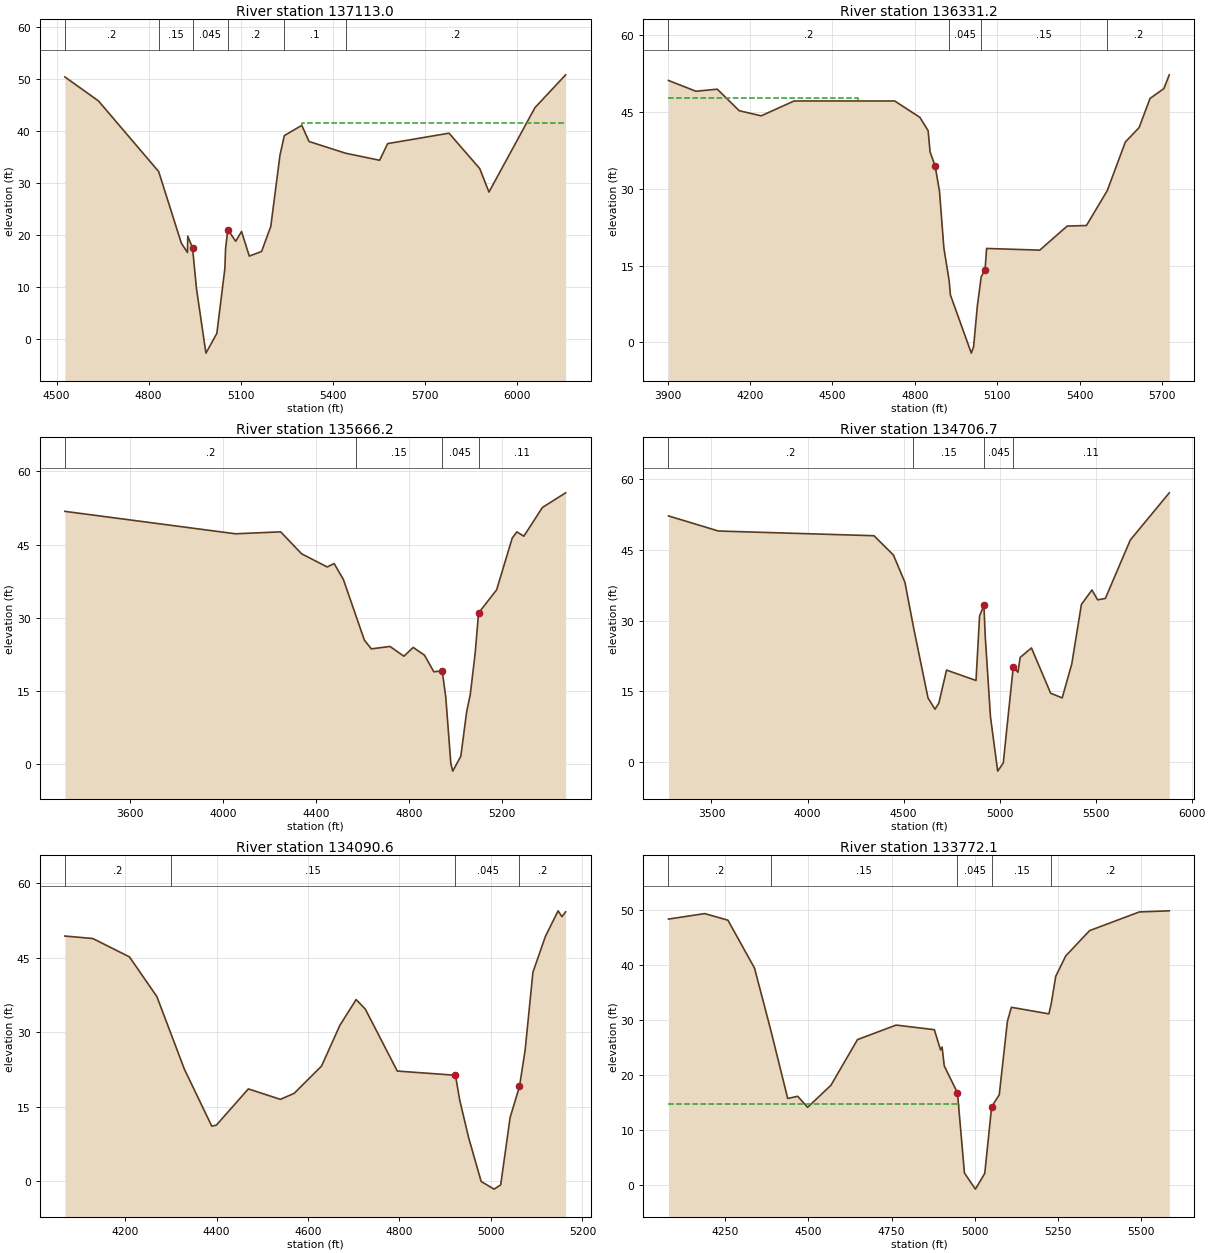
Type RM Length L Ch R = 1 ,137113.0,663,781.8,926.3
BEGIN DESCRIPTION:
Cross Section 137113.0
END DESCRIPTION:
XS GIS Cut Line= 6
      3102122.33     13841375.21      3102150.12     13841269.34
      3102101.47     13841127.13      3101723.48     13840883.87
      3101543.85     13840333.74      3101543.85     13839993.66
#Sta/Elev= 30
    4527    50.4  4636.5    45.8  4832.9   32.24  4906.8    18.5  4926.8    16.7
  4927.8   19.83  4943.3   17.62  4956.3    9.73    4987   -2.62  5022.6    1.17
  5048.8   13.63  5051.1   17.46  5058.4   21.09  5084.2   18.85  5103.1   20.74
  5128.5      16  5168.5    16.9  5198.5    21.7  5228.5    35.4  5242.7   39.14
  5299.6    41.1  5323.3      38  5442.7   35.75  5553.3    34.4  5579.6    37.6
  5779.6    39.6  5879.8    32.8  5909.8    28.3  6059.8    44.5  6159.8    50.8
#Mann= 6 ,-1 , 0
    4527      .2       0  4832.9     .15       0  4943.3    .045       0
  5058.4      .2       0  5242.7      .1       0  5442.7      .2       0
#XS Ineff= 2 , 0
                            5300            41.5
Permanent Ineff=
       F       F
Bank Sta=4943.3,5058.4
XS Rating Curve= 0
Exp/Cntr=.3,.1

Type RM Length L Ch R = 1 ,136331.2,162.2,665,745.6
BEGIN DESCRIPTION:
Cross Section 136331.2
END DESCRIPTION:
XS GIS Cut Line= 6
      3102206.25     13841439.62      3102456.99     13840949.36
      3102483.19     13840788.44      3102408.34     13840552.67
      3102116.43     13840073.64      3102014.85     13839791.36
#Sta/Elev= 30
  3902.4    51.1  4002.4      49  4080.2    49.4  4160.2    45.2  4240.2    44.2
  4360.2    47.1  4726.7    47.1  4818.5    43.9  4848.5    41.3  4855.5   37.18
  4874.2   34.35  4889.8   29.53  4905.7   18.48  4925.3   11.95  4929.6    9.27
  5005.8   -2.09  5014.2    -.83  5027.8    7.12  5041.8   12.79  5055.9   14.18
  5061.5   18.33  5255.2      18  5355.2    22.7  5425.2    22.8  5501.1   29.61
  5567.1    39.1  5617.1    41.9  5657.1    47.6  5707.1    49.5  5727.1    52.2
#Mann= 4 ,-1 , 0
  3902.4      .2       0  4925.3    .045       0  5041.8     .15       0
  5501.1      .2       0
#XS Ineff= 2 , 0
          4593.7    47.7
Permanent Ineff=
       F       F
Bank Sta=4874.2,5055.9
XS Rating Curve= 0
Exp/Cntr=.3,.1

Type RM Length L Ch R = 1 ,135666.2,888.7,959.5,634.3
BEGIN DESCRIPTION:
Cross Section 135666.2
END DESCRIPTION:
XS GIS Cut Line= 6
      3102123.95     13841576.17      3102247.42     13841426.52
      3102505.65     13840902.58      3102558.04     13840344.96
      3102610.43     13840142.87       3103003.4     13839680.65
#Sta/Elev= 30
  3318.3    51.8  4052.3    47.2  4246.6    47.6  4336.6    43.1  4446.6    40.4
  4476.6    41.1  4516.6    37.8    4571    30.3  4606.6    25.4  4636.6    23.6
  4716.6    24.1  4776.6    22.1  4816.6    23.9  4865.3    22.3  4905.3    18.9
  4941.3   19.11  4956.7   13.72  4978.5     .11  4986.6   -1.47  5021.5    1.59
  5046.3   10.65    5062   14.24  5082.9   22.59  5097.7   30.96  5175.3    35.7
  5242.4    46.3  5262.4    47.6  5292.4    46.7  5372.4    52.6  5472.2    55.6
#Mann= 4 ,-1 , 0
  3318.3      .2       0    4571     .15       0  4941.3    .045       0
  5097.7     .11       0
Bank Sta=4941.3,5097.7
XS Rating Curve= 0
Exp/Cntr=.3,.1

Type RM Length L Ch R = 1 ,134706.7,89.3,616.1,653.9
BEGIN DESCRIPTION:
Cross Section 134706.7
END DESCRIPTION:
XS GIS Cut Line= 6
      3102550.55     13842075.83      3103284.07     13840930.65
      3103257.87     13840698.62      3103096.95     13840459.11
      3103194.25     13840159.71      3103140.73     13839761.53
#Sta/Elev= 30
  3276.2    52.2  3536.2      49  4346.2      48  4447.4    43.9  4507.4    38.1
  4551.5   28.67  4627.4    13.6  4663.8    11.2  4683.8    12.5  4723.8    19.5
  4877.3    17.3  4895.9   30.98  4918.5   33.25  4925.4   26.61  4952.6    9.59
  4990.2   -1.93  5019.1    -.22  5071.1   20.12  5095.7   19.05  5107.1   22.18
  5165.9    24.2  5265.9    14.6  5325.9    13.6  5375.9    20.8  5425.9    33.4
  5480.7    36.5  5510.7    34.4  5550.7    34.7  5680.7    47.1  5883.5    57.1
#Mann= 4 ,-1 , 0
  3276.2      .2       0  4551.5     .15       0  4918.5    .045       0
  5071.1     .11       0
Bank Sta=4918.5,5071.1
XS Rating Curve= 0
Exp/Cntr=.3,.1

Type RM Length L Ch R = 1 ,134090.6,83.7,318.5,362.5
BEGIN DESCRIPTION:
Cross Section 134090.6
END DESCRIPTION:
XS GIS Cut Line= 4
      3103262.02     13841232.75      3103302.78       13841187.
      3103448.73     13840640.61      3103706.91     13840250.04
#Sta/Elev= 30
  4068.3    49.4  4129.6    48.9  4209.6    45.2  4269.6    37.2    4300    29.8
  4329.6    22.6  4389.6    11.1  4399.6    11.3  4469.6    18.6  4539.6    16.5
  4569.6    17.7  4629.6    23.2  4669.6    31.4  4705.2    36.6  4725.2    34.7
  4795.2    22.2  4922.4   21.35  4931.7   16.35  4951.3    8.75  4978.6    -.05
  5006.9   -1.59  5021.3    -.73  5041.9   12.84  5062.4   19.09  5074.7   26.36
  5091.8   42.11  5119.1   49.34  5146.9   54.48  5155.2    53.3  5163.3   54.28
#Mann= 4 ,-1 , 0
  4068.3      .2       0    4300     .15       0  4922.4    .045       0
  5062.4      .2       0
Bank Sta=4922.4,5062.4
XS Rating Curve= 0
Exp/Cntr=.5,.3

Type RM Length L Ch R = 1 ,133772.1,24,24,24
BEGIN DESCRIPTION:
Upstream Section of Bridge/Culvert/Weir
END DESCRIPTION:
XS GIS Cut Line= 6
      3103304.57     13841341.56      3103359.56     13841266.17
        3103555.      13840729.6      3103680.64     13840686.85
      3103969.62     13840594.04      3103915.47     13840190.96
#Sta/Elev= 30
  4078.7   48.28  4187.6   49.28  4257.6   48.08  4337.6   39.38  4385.9   28.27
  4437.6   15.68  4467.6   16.08  4497.6   14.08  4567.6   18.08  4647.6   26.38
  4763.7   29.02  4878.9   28.18  4897.6   24.51  4902.2   25.03  4908.8   21.59
  4948.5   16.71  4969.5    2.14  5002.5    -.79  5030.6    2.07  5051.4   14.18
  5074.3   16.36  5098.8    29.7  5110.8   32.25  5223.6   31.06  5230.6   32.87
  5244.3   37.88  5274.3   41.58    5346   46.18    5496   49.58    5586   49.78
#Mann= 5 ,-1 , 0
  4078.7      .2       0  4385.9     .15       0  4948.5    .045       0
  5051.4     .15       0  5230.6      .2       0
#XS Ineff= 2 , 0
            4952    14.6    5110            31.1
Permanent Ineff=
       F       F
Bank Sta=4948.5,5051.4
XS Rating Curve= 0
Exp/Cntr=.5,.3

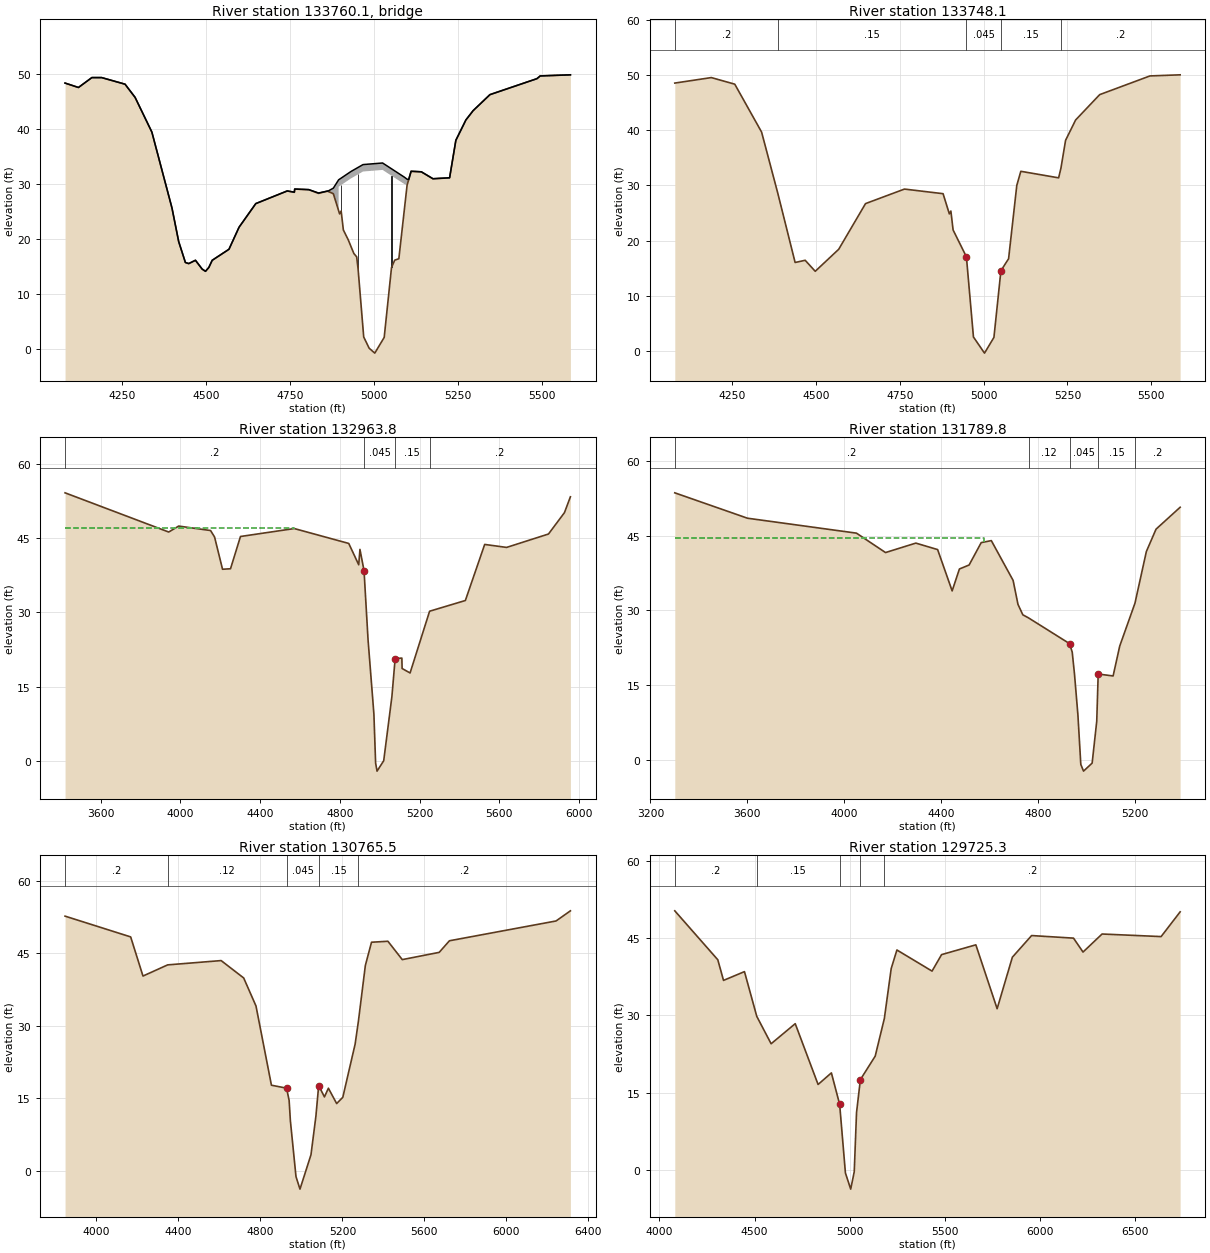
Type RM Length L Ch R = 3 ,133760.1,,,
BEGIN DESCRIPTION:
FOOTBRIDGE AT END OF WESTCOTT
Structure ID: W00-49A
END DESCRIPTION:
Bridge Culvert--1,0,-1,-1, 0
Deck Dist Width WeirC Skew NumUp NumDn MinLoCord MaxHiCord MaxSubmerge Is_Ogee
10,4,2.6,0, 47, 47, , , .95, 0, 1,1,,
  4078.7  4118.7  4158.7  4187.6  4257.6  4287.6  4337.6  4397.6  4417.6  4437.6
  4447.6  4467.6  4487.6  4497.6  4507.6  4517.6  4567.6  4597.6  4647.6  4741.4
  4762.6  4763.7  4805.7  4834.7  4861.4  4864.4  4878.9 4894.51  4894.6  4931.3
  4967.4  5025.8  5090.1  5098.8  5103.7  5110.8  5141.4  5175.9  5225.4  5225.7
  5244.3  5274.3    5296    5346    5486    5496    5586
    48.3    47.5    49.3    49.3    48.1    45.7    39.4    25.6    19.5    15.7
    15.5    16.1    14.5    14.1    14.8    16.1    18.1    22.1    26.4    28.7
   28.48   29.05   28.94   28.33   28.68   28.72   29.21   30.71   30.72   32.23
   33.49   33.78   31.23   30.84   30.77   32.28   32.18   30.92   31.09    31.1
    37.9    41.6    43.3    46.2    49.1    49.6    49.8
    48.3    47.5    49.3    49.3    48.1    45.7    39.4    25.6    19.5    15.7
    15.5    16.1    14.5    14.1    14.8    16.1    18.1    22.1    26.4    28.7
   28.45   29.04   28.93   28.26   28.66   28.58    28.2   25.14   29.46   30.97
   32.23   32.52   29.97   29.72   30.76   32.27   32.17   30.91   31.09    31.1
    37.9    41.6    43.3    46.2    49.1    49.6    49.8
  4078.7  4118.7  4158.7  4187.6  4257.6  4287.6  4337.6  4397.6  4417.6  4437.6
  4447.6  4467.6  4487.6  4497.6  4507.6  4517.6  4567.6  4597.6  4647.6  4741.4
  4762.6  4763.7  4805.7  4834.7  4861.4  4864.4  4878.9 4894.51  4894.6  4931.3
  4967.4  5025.8  5090.1  5098.8  5103.7  5110.8  5141.4  5175.9  5225.4  5225.7
  5244.3  5274.3    5296    5346    5486    5496    5586
   48.63   47.83   49.63   49.63   48.43   46.03   39.73   25.93   19.83   16.03
   15.83   16.43   14.83   14.43   15.13   16.43   18.43   22.43   26.73   29.03
   28.78   29.37   29.26   28.59   28.99   28.91   29.21   30.71   30.72   32.23
   33.49   33.78   31.23   30.84   31.09    32.6    32.5   31.24   31.42   31.43
   38.23   41.93   43.63   46.53   49.43   49.93   50.13
   48.63   47.83   49.63   49.63   48.43   46.03   39.73   25.93   19.83   16.03
   15.83   16.43   14.83   14.43   15.13   16.43   18.43   22.43   26.73   29.03
   28.78   29.37   29.26   28.59   28.99   28.91   28.53   25.47   29.79    31.3
   32.56   32.85    30.3   30.05   31.09    32.6    32.5   31.24   31.42   31.43
   38.23   41.93   43.63   46.53   49.43   49.93   50.13
Pier Skew, UpSta & Num, DnSta & Num=  ,4902.2, 2 ,4902.2, 2 , 0 , 0 , 0 ,,
       2       2
   23.53   30.81
       2       2
   23.86   31.14
Pier Skew, UpSta & Num, DnSta & Num=  ,4952.7, 2 ,4952.7, 2 , 0 , 0 , 0 ,,
       2       2
    12.8   32.75
       2       2
   13.13   33.08
Pier Skew, UpSta & Num, DnSta & Num=  ,5052.6, 2 ,5052.6, 2 , 0 , 0 , 0 ,,
       2       2
    13.3   32.52
       2       2
   13.63   32.85
Abutment Skew #Up #Dn= , 2 , 2
  4894.4  4908.8
   29.46   21.61
  4894.4  4908.8
   29.79   21.94
Abutment Skew #Up #Dn= , 2 , 2
  5074.3 5104.29
   16.38   30.84
  5074.3 5104.29
   16.71   31.17
BR Coef= 1 , 1 , 0 ,1.25, 0 ,,,.8,0,2,0,
WSPro=,,,, 1 ,,,, 0 ,,,, 0 ,,,,-1 ,-1 ,-1 , 0 , 0 , 0 , 0 , 0
BR U #Sta/Elev= 88
  4078.7    48.3  4118.7    47.5  4158.7    49.3  4187.6    49.3  4257.6    48.1
  4287.6    45.7  4337.6    39.4  4385.9   28.29  4397.6    25.6  4417.6    19.5
  4437.6    15.7  4447.6    15.5  4467.6    16.1  4487.6    14.5  4497.6    14.1
  4507.6    14.8  4517.6    16.1  4567.6    18.1  4597.6    22.1  4647.6    26.4
  4741.4    28.7  4762.5   28.45  4762.6   28.45  4763.7   29.04  4805.7   28.93
  4811.7   28.79  4829.5   28.38  4834.7   28.26  4861.4   28.66  4864.4   28.58
  4878.9    28.2    4879   28.18 4879.09   28.16  4879.2   28.14 4879.31   28.12
  4894.4   25.16 4894.51   25.14  4894.6   25.12  4895.2      25  4897.6   24.53
  4902.2   25.05  4908.7   21.66  4908.8   21.61  4923.5    19.8  4931.3   18.64
  4940.2   17.32  4948.5   16.73  4952.7   14.54  4967.4    3.71  4969.5    2.16
  4985.8     .12  5002.5    -.77  5019.2     .93  5025.8     1.6  5030.6    2.09
  5051.4    14.2  5052.6   14.82  5062.1   16.13  5074.2   16.38  5074.3   16.38
  5079.7   19.32  5090.1   24.99  5098.8   29.72  5103.7   30.76 5103.79   30.78
  5103.9    30.8 5104.01   30.83 5104.09   30.84  5104.2   30.87  5104.3   30.89
  5108.7   31.82  5110.8   32.27  5111.4   32.27  5141.4   32.17    5143   32.11
    5173   31.02  5175.9   30.91  5223.6   31.08  5225.4   31.09  5225.7    31.1
  5230.6   32.89  5244.3    37.9  5274.3    41.6    5296    43.3    5346    46.2
    5486    49.1    5496    49.6    5586    49.8
BR U #Mann= 5
  4078.7      .2  4385.9     .15  4948.5    .045  5051.4     .15  5230.6      .2
BR U Banks=4948.5,5051.4
BR D #Sta/Elev= 88
  4078.7   48.63  4118.7   47.83  4158.7   49.63  4187.6   49.63  4257.6   48.43
  4287.6   46.03  4337.6   39.73  4385.9   28.62  4397.6   25.93  4417.6   19.83
  4437.6   16.03  4447.6   15.83  4467.6   16.43  4487.6   14.83  4497.6   14.43
  4507.6   15.13  4517.6   16.43  4567.6   18.43  4597.6   22.43  4647.6   26.73
  4741.4   29.03  4762.5   28.78  4762.6   28.78  4763.7   29.37  4805.7   29.26
  4811.7   29.12  4829.5   28.71  4834.7   28.59  4861.4   28.99  4864.4   28.91
  4878.9   28.53    4879   28.51 4879.09   28.49  4879.2   28.47 4879.31   28.45
  4894.4   25.49 4894.51   25.47  4894.6   25.45  4895.2   25.33  4897.6   24.86
  4902.2   25.38  4908.7   21.99  4908.8   21.94  4923.5   20.13  4931.3   18.97
  4940.2   17.65  4948.5   17.06  4952.7   14.87  4967.4    4.04  4969.5    2.49
  4985.8     .45  5002.5    -.44  5019.2    1.26  5025.8    1.93  5030.6    2.42
  5051.4   14.53  5052.6   15.15  5062.1   16.46  5074.2   16.71  5074.3   16.71
  5079.7   19.65  5090.1   25.32  5098.8   30.05  5103.7   31.09 5103.79   31.11
  5103.9   31.13 5104.01   31.16 5104.09   31.17  5104.2    31.2  5104.3   31.22
  5108.7   32.15  5110.8    32.6  5111.4    32.6  5141.4    32.5    5143   32.44
    5173   31.35  5175.9   31.24  5223.6   31.41  5225.4   31.42  5225.7   31.43
  5230.6   33.22  5244.3   38.23  5274.3   41.93    5296   43.63    5346   46.53
    5486   49.43    5496   49.93    5586   50.13
BR D #Mann= 5
  4078.7      .2  4385.9     .15  4948.5    .045  5051.4     .15  5230.6      .2
BR D Banks=4948.5,5051.4
BC Design=,, 0 ,, 0 ,,,,,,
BC HTab HWMax=49.78

Type RM Length L Ch R = 1 ,133748.1,784.3,784.3,784.3
BEGIN DESCRIPTION:
Downstream Section of Bridge/Culvert/Weir
END DESCRIPTION:
XS GIS Cut Line= 6
      3103313.98     13841363.64      3103368.96     13841288.25
       3103564.4     13840751.68      3103690.04     13840708.93
      3103979.02     13840616.12      3103924.87     13840213.04
#Sta/Elev= 30
  4078.7   48.61  4187.6   49.61  4257.6   48.41  4337.6   39.71  4385.9    28.6
  4437.6   16.01  4467.6   16.41  4497.6   14.41  4567.6   18.41  4647.6   26.71
  4763.7   29.35  4878.9   28.51  4897.6   24.84  4902.2   25.36  4908.8   21.92
  4948.5   17.04  4969.5    2.47  5002.5    -.46  5030.6     2.4  5051.4   14.51
  5074.3   16.69  5098.8   30.03  5110.8   32.58  5223.6   31.39  5230.6    33.2
  5244.3   38.21  5274.3   41.91    5346   46.51    5496   49.91    5586   50.11
#Mann= 5 ,-1 , 0
  4078.7      .2       0  4385.9     .15       0  4948.5    .045       0
  5051.4     .15       0  5230.6      .2       0
#XS Ineff= 2 , 0
            4952    14.6    5110            31.1
Permanent Ineff=
       F       F
Bank Sta=4948.5,5051.4
XS Rating Curve= 0
Exp/Cntr=.5,.3

Type RM Length L Ch R = 1 ,132963.8,665.5,1174,1390.7
BEGIN DESCRIPTION:
Cross Section 132963.8
END DESCRIPTION:
XS GIS Cut Line= 6
      3104606.64     13842352.61      3104586.59     13841029.57
      3104397.37     13840840.35      3104259.76     13840728.53
      3104113.54      13840436.1      3103922.43     13840039.72
#Sta/Elev= 30
  3421.8    54.1  3941.8    46.2  3991.8    47.4  4151.8    46.5  4171.8    45.2
  4211.8    38.7  4251.8    38.8  4301.8    45.3  4571.8    46.9    4845    43.9
    4895    39.6  4901.1    42.7  4921.6   38.43  4941.8   24.48  4971.1    9.53
  4979.7    -.36  4986.9   -1.98  5020.3     .11  5061.3   13.01  5077.7    20.7
  5111.4    20.8  5112.6    18.7  5152.6    17.8  5250.5   30.24  5429.9    32.4
  5526.9    43.7  5636.9    43.1  5846.9    45.8  5926.9    50.1  5956.9    53.3
#Mann= 4 ,-1 , 0
  3421.8      .2       0  4921.6    .045       0  5077.7     .15       0
  5250.5      .2       0
#XS Ineff= 2 , 0
            4570    47.1
Permanent Ineff=
       F       F
Bank Sta=4921.6,5077.7
XS Rating Curve= 0
Exp/Cntr=.3,.1

Type RM Length L Ch R = 1 ,131789.8,1084.3,1024.3,899.5
BEGIN DESCRIPTION:
Cross Section 131789.8
END DESCRIPTION:
XS GIS Cut Line= 5
      3104715.64     13842325.27      3104689.81      13841330.6
      3104836.02     13841089.77      3105429.49     13840539.31
      3105429.49      13840539.3
#Sta/Elev= 30
  3300.5    53.6  3600.5    48.5  4050.5    45.5  4170.5    41.6  4295.5    43.5
  4385.5    42.2  4445.5    33.9  4475.5    38.3  4515.5    39.1  4565.5    43.6
  4607.2      44  4697.2      36  4717.2    31.2  4737.2    29.1  4760.9   28.47
  4930.3    23.3  4941.2   21.59  4950.4   17.27  4964.7    8.97  4976.6    -.96
  4987.9   -2.31  5023.4     -.7  5042.4    7.71  5048.4    17.2    5110   16.81
  5137.2    22.8  5200.2   31.43  5247.2    41.8  5287.2    46.3  5386.7    50.7
#Mann= 5 ,-1 , 0
  3300.5      .2       0  4760.9     .12       0  4930.3    .045       0
  5048.4     .15       0  5200.2      .2       0
#XS Ineff= 2 , 0
            4575    44.5
Permanent Ineff=
       F       F
Bank Sta=4930.3,5048.4
XS Rating Curve= 0
Exp/Cntr=.3,.1

Type RM Length L Ch R = 1 ,130765.5,577.2,1040.2,1150.7
BEGIN DESCRIPTION:
Cross Section 130765.5
END DESCRIPTION:
XS GIS Cut Line= 5
      3105249.36     13842237.73      3105678.92     13841709.04
      3105816.53     13841494.02      3105902.54     13841115.58
       3106054.2     13839985.69
#Sta/Elev= 30
  3847.4    52.7  4167.4    48.4  4227.4    40.3  4347.8   42.61  4608.6    43.5
  4718.6    39.9  4778.6    34.1  4853.9    17.7  4927.7   17.09  4940.2   14.55
  4946.3   10.34  4973.7   -1.22  4993.1   -3.81  5046.8    3.31  5070.7   11.26
  5084.3   17.62  5112.5   15.28  5131.7   17.08    5172    13.9    5202    15.2
    5262    26.2  5277.6    30.8    5312    42.5    5342    47.3    5422    47.5
    5492    43.7    5672    45.2    5722    47.6    6242    51.7    6312    53.8
#Mann= 5 ,-1 , 0
  3847.4      .2       0  4347.8     .12       0  4927.7    .045       0
  5084.3     .15       0  5277.6      .2       0
Bank Sta=4927.7,5084.3
XS Rating Curve= 0
Exp/Cntr=.3,.1

Type RM Length L Ch R = 1 ,129725.3,1216.8,562.1,272.3
BEGIN DESCRIPTION:
Cross Section 129725.3
END DESCRIPTION:
XS GIS Cut Line= 6
      3105478.96     13842299.49      3105990.27     13842002.34
      3106458.17     13841926.65      3106719.64     13841458.76
      3106877.89     13841238.57      3106999.67     13840468.17
#Sta/Elev= 30
  4080.7    50.3  4306.6    40.8  4336.6    36.8  4446.6    38.5  4511.2   29.82
  4586.6    24.5  4713.2    28.4  4833.2    16.6  4903.1   18.85  4946.5   12.74
  4976.8    -.58  5004.5   -3.71  5023.1    -.33  5035.1   11.14  5055.3   17.54
  5133.2    22.1  5181.2    29.4  5217.2    39.1  5247.2    42.7  5431.7    38.6
  5481.7    41.8  5661.7    43.7  5773.5    31.3  5853.5    41.3  5954.6    45.5
  6174.6      45  6224.6    42.3  6324.6    45.8  6634.6    45.3  6734.6    50.1
#Mann= 5 ,-1 , 0
  4080.7      .2       0  4511.2     .15       0  4946.5    .045       0
  5055.3     .15       0  5181.2      .2       0
Bank Sta=4946.5,5055.3
XS Rating Curve= 0
Exp/Cntr=.3,.1

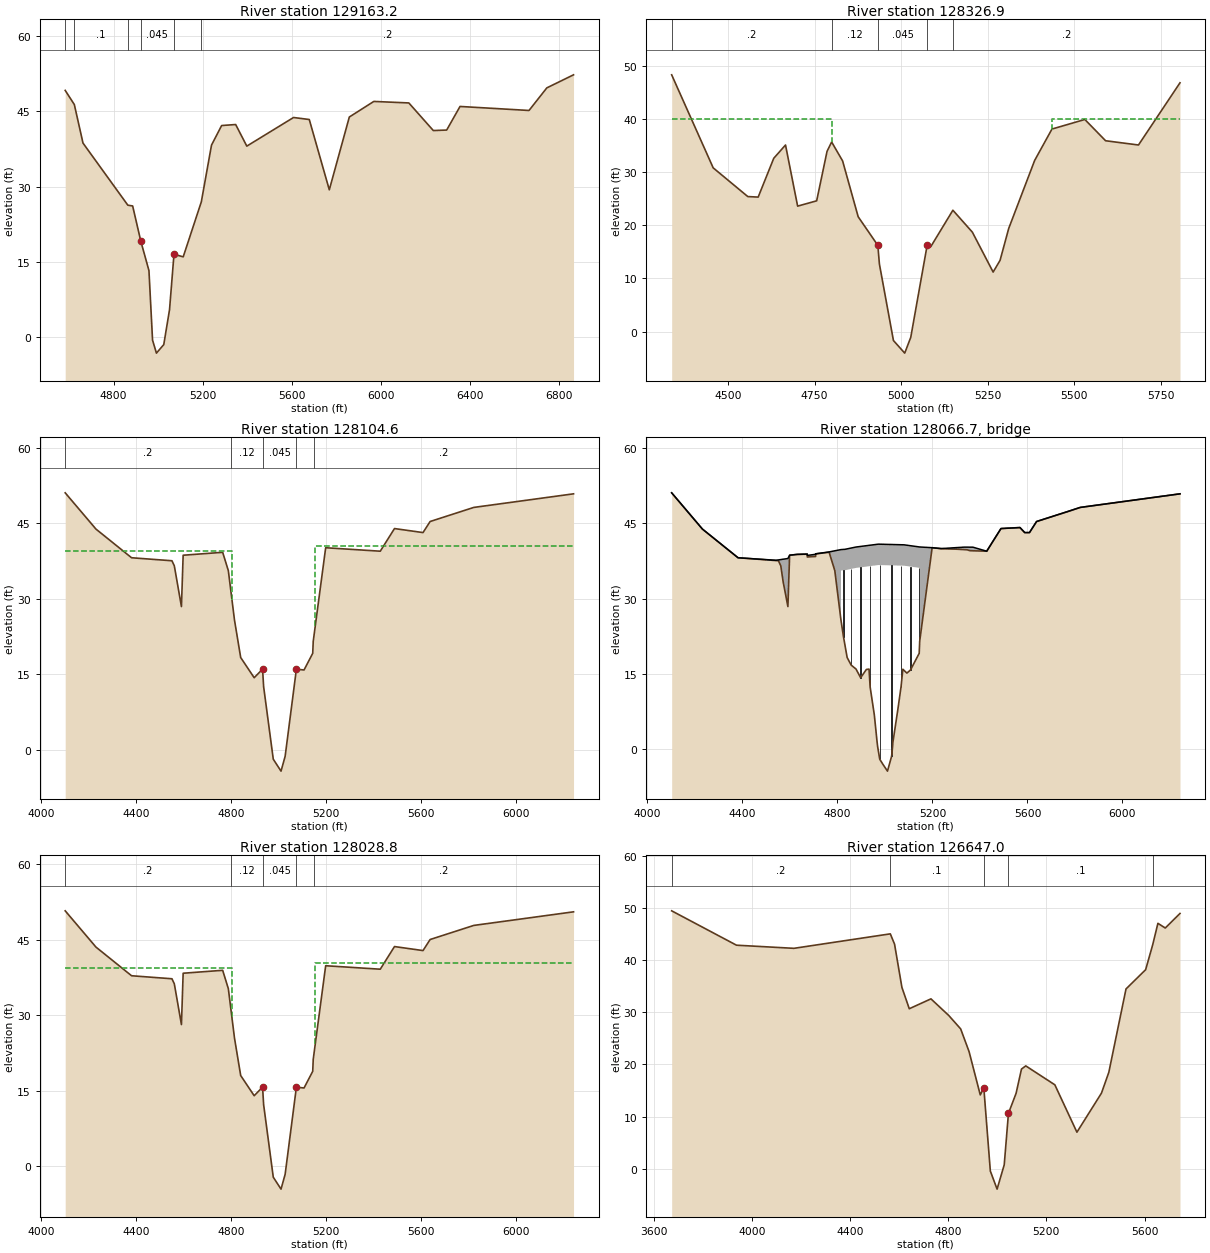
Type RM Length L Ch R = 1 ,129163.2,745.9,836.3,942.8
BEGIN DESCRIPTION:
Cross Section 129163.2
END DESCRIPTION:
XS GIS Cut Line= 6
      3106815.96     13842497.69      3106795.32     13842291.33
       3106588.9     13841885.36      3106747.16      13841513.8
      3106939.82     13841224.81      3107064.32      13840363.7
#Sta/Elev= 30
  4582.3    49.2  4623.3   46.38  4662.3    38.7  4863.7   26.34  4885.4   26.18
    4922   19.17  4958.6   13.31  4974.8    -.55  4992.2   -3.13  5025.2   -1.43
  5051.1    5.53  5071.1   16.56  5112.6   16.05    5194   27.01  5239.7    38.3
  5285.2    42.2  5348.3    42.4  5398.3    38.1  5608.3    43.8    5679    43.4
    5769    29.4    5859    43.9    5969      47  6126.4    46.7  6236.4    41.2
  6296.4    41.3  6356.4      46  6666.4    45.2  6746.4    49.7  6866.4    52.3
#Mann= 6 ,-1 , 0
  4582.3      .2       0  4623.3      .1       0  4863.7      .2       0
    4922    .045       0  5071.1     .15       0    5194      .2       0
Bank Sta=4922,5071.1
XS Rating Curve= 0
Exp/Cntr=.3,.1

Type RM Length L Ch R = 1 ,128326.9,147.7,222.3,267.8
BEGIN DESCRIPTION:
Cross Section 128326.9 - Interpolated
END DESCRIPTION:
XS GIS Cut Line= 3
      3107363.09     13842372.77      3107460.25     13842058.42
      3107405.04     13840919.78
#Sta/Elev= 30
  4337.1    48.3  4457.1    30.8  4557.1    25.4  4587.1    25.3  4632.1    32.6
  4666.1    35.1  4701.1    23.6  4756.1    24.6  4786.1    33.9  4799.4   35.67
  4831.1    32.1  4876.1    21.6  4932.9   16.22  4937.4   12.72    4978   -1.68
  5010.6   -4.05    5028   -1.09  5075.3    16.2  5086.1      16  5149.8   22.83
  5206.1    18.7  5266.1    11.2  5286.1    13.4  5311.1    19.4  5386.1    32.2
  5436.1    38.1  5531.1    39.9  5591.1    35.9  5686.1    35.1  5806.1    46.8
#Mann= 5 ,-1 , 0
  4337.1      .2       0  4799.4     .12       0  4932.9    .045       0
  5075.3     .12       0  5149.8      .2       0
#XS Ineff= 2 , 0
            4800      40    5435              40
Permanent Ineff=
       F       F
Bank Sta=4932.9,5075.3
XS Rating Curve= 0
Exp/Cntr=.5,.3

Type RM Length L Ch R = 1 ,128104.6,75.8,75.8,75.8
BEGIN DESCRIPTION:
Upstream Section of Bridge/Culvert/Weir
END DESCRIPTION:
XS GIS Cut Line= 5
      3107529.53     13842467.73      3107682.19     13841792.85
      3107771.64     13841324.96      3107847.33     13840884.59
      3108044.15     13840397.69
#Sta/Elev= 30
  4101.9   51.01  4231.3   43.81  4381.3   38.11  4551.3   37.51  4561.3   36.51
  4591.3   28.41  4598.5   38.61  4764.9   39.19  4788.8   35.54  4799.4   31.52
  4814.7   25.72  4840.8   18.28  4897.6   14.27  4932.9   15.98  4937.4   12.48
    4978   -1.92  5010.6   -4.29    5028   -1.33  5075.3   15.96  5107.5   15.81
  5144.1   19.12  5146.2    21.5  5149.8   22.78  5198.6    40.1  5428.4   39.41
  5488.4   43.91  5608.4   43.11  5638.4   45.31  5822.2   48.11  6242.2   50.81
#Mann= 5 ,-1 , 0
  4101.9      .2       0  4799.4     .12       0  4932.9    .045       0
  5075.3     .12       0  5149.8      .2       0
#XS Ineff= 2 , 0
            4805    39.5    5155            40.5
Permanent Ineff=
       F       F
Bank Sta=4932.9,5075.3
XS Rating Curve= 0
Exp/Cntr=.5,.3

Type RM Length L Ch R = 3 ,128066.7,,,
BEGIN DESCRIPTION:
SHEPHERD DRIVE
Structure ID: WOO-49
END DESCRIPTION:
Bridge Culvert--1,0,-1,-1, 0
Deck Dist Width WeirC Skew NumUp NumDn MinLoCord MaxHiCord MaxSubmerge Is_Ogee
10,55.8,2.6,0, 39, 39, , , .95, 0, 1,1,,
  4101.9  4231.3  4381.3  4541.2  4551.3  4561.3  4571.3  4591.3  4598.5  4630.4
  4672.8    4673    4708  4708.3  4764.9  4788.8  4814.7  4814.8    4832    4878
  4971.9  5080.3 5145.99  5146.1  5146.3  5198.6  5235.9    5334  5346.3  5358.4
  5370.2  5428.4  5488.4  5568.4  5588.4  5608.4  5638.4  5822.2  6242.2
      51    43.8    38.1    37.6   37.67   37.74   37.81   37.95   38.61   38.77
   38.83   38.56   38.79   38.88   39.26   39.48   39.72   39.72   39.78   40.23
    40.8   40.67   40.24   40.24   40.24    40.1   39.92   40.21   40.21    40.2
    40.2    39.4    43.9    44.1    43.1    43.1    45.3    48.1    50.8
      51    43.8    38.1   37.54    37.5    36.5    33.3    28.4    38.6   38.76
   38.82   38.25   38.35   38.87   39.18   35.53   25.71   35.57   35.63   36.08
   36.65   36.52   36.09   21.38   21.53   40.09   39.91   39.71   39.67    39.5
   39.48    39.4    43.9    44.1    43.1    43.1    45.3    48.1    50.8
  4101.9  4231.3  4381.3  4541.2  4551.3  4561.3  4571.3  4591.3  4598.5  4630.4
  4672.8    4673    4708  4708.3  4764.9  4788.8  4814.7  4814.8    4832    4878
  4971.9  5080.3 5145.99  5146.1  5146.3  5198.6  5235.9    5334  5346.3  5358.4
  5370.2  5428.4  5488.4  5568.4  5588.4  5608.4  5638.4  5822.2  6242.2
      51    43.8    38.1    37.6   37.67   37.74   37.81   37.95   38.61   38.77
   38.83   38.56   38.79   38.88   39.26   39.48   39.72   39.72   39.78   40.23
    40.8   40.67   40.24   40.24   40.24    40.1   39.92   40.21   40.21    40.2
    40.2    39.4    43.9    44.1    43.1    43.1    45.3    48.1    50.8
   50.79   43.59   37.89   37.33   37.29   36.29   33.09   28.19   38.39   38.55
   38.61   38.04   38.14   38.66   38.97   35.32    25.5   35.36   35.42   35.87
   36.44   36.31   35.88   21.17   21.32   39.88    39.7    39.5   39.46   39.29
   39.27   39.19   43.69   43.89   42.89   42.89   45.09   47.89   50.59
Pier Skew, UpSta & Num, DnSta & Num=  ,4825.3, 2 ,4825.3, 2 , 0 , 0 , 0 ,,
       2       2
   21.14   36.61
       2       2
   20.93    36.4
Pier Skew, UpSta & Num, DnSta & Num=  ,4857.9, 2 ,4857.9, 2 , 0 , 0 , 0 ,,
       2       2
   15.72    36.9
       2       2
   15.51   36.69
Pier Skew, UpSta & Num, DnSta & Num=  ,4897.6, 2 ,4897.6, 2 , 0 , 0 , 0 ,,
       2       2
   13.33   37.21
       2       2
   13.12      37
Pier Skew, UpSta & Num, DnSta & Num=  ,4937.4, 2 ,4937.4, 2 , 0 , 0 , 0 ,,
       2       2
   11.15   37.45
       2       2
   10.94   37.24
Pier Skew, UpSta & Num, DnSta & Num=  ,4978, 2 ,4978, 2 , 0 , 0 , 0 ,,
       2       2
   -3.01   37.64
       2       2
   -3.22   37.43
Pier Skew, UpSta & Num, DnSta & Num=  ,5028, 2 ,5028, 2 , 0 , 0 , 0 ,,
       2       2
   -2.51   37.58
       2       2
   -2.72   37.37
Pier Skew, UpSta & Num, DnSta & Num=  ,5067.8, 2 ,5067.8, 2 , 0 , 0 , 0 ,,
       2       2
   11.16   37.53
       2       2
   10.95   37.32
Pier Skew, UpSta & Num, DnSta & Num=  ,5107.5, 2 ,5107.5, 2 , 0 , 0 , 0 ,,
       2       2
   14.76   37.35
       2       2
   14.55   37.14
Pier Skew, UpSta & Num, DnSta & Num=  ,5144.1, 2 ,5144.1, 2 , 0 , 0 , 0 ,,
       2       2
   18.02    37.1
       2       2
   17.81   36.89
BR Coef= 1 , 1 , 0 ,1.25, 0 ,,,.8,0,2,0,
WSPro=,,,, 1 ,,,, 0 ,,,, 0 ,,,,-1 ,-1 ,-1 , 0 , 0 , 0 , 0 , 0
BR U #Sta/Elev= 84
  4101.9      51  4231.3    43.8  4381.3    38.1  4541.2   37.54  4551.3    37.5
  4561.3    36.5  4571.3    33.3  4591.3    28.4  4598.5    38.6  4598.6    38.6
  4606.6   38.64  4630.4   38.76  4667.3   38.81  4672.8   38.82    4673   38.25
    4708   38.35  4708.3   38.87  4731.6      39  4764.9   39.18 4786.39    35.9
  4786.5   35.88 4786.61   35.86  4788.8   35.53  4799.4   31.51  4814.5   25.79
 4814.61   25.74  4814.7   25.71  4814.8   25.68  4814.9   25.65  4825.3   22.41
    4832   20.62  4840.8   18.27  4857.9   16.76  4875.1    16.1    4878   15.99
  4897.6   14.26  4921.7    15.9  4932.9   15.97  4937.4   12.47  4955.2    6.86
  4966.7    1.54  4969.2     .55  4971.9    -.21    4978   -1.93    4991   -2.92
  5010.6    -4.3    5028   -1.34  5032.2     .65  5033.4    1.44  5054.3    7.97
  5067.8    12.5  5075.3   15.95  5080.3   15.72  5092.3   15.18  5107.5    15.8
  5144.1   19.11  5145.8   21.04 5145.87   21.12 5145.99   21.25  5146.1   21.38
  5146.2   21.49  5146.3   21.53  5149.8   22.77  5198.6   40.09 5199.99   40.08
  5200.1   40.08 5200.21   40.08  5200.3   40.08  5235.9   39.91  5267.6   39.84
  5299.3   39.81    5334   39.71  5346.3   39.67  5358.4    39.5  5370.2   39.48
  5428.4    39.4  5488.4    43.9  5568.4    44.1  5588.4    43.1  5608.4    43.1
  5638.4    45.3  5772.2    47.3  5822.2    48.1  6242.2    50.8
BR U #Mann= 5
  4101.9      .2  4799.4     .12  4932.9    .045  5075.3     .12  5149.8      .2
BR U Banks=4932.9,5075.3
BR D #Sta/Elev= 84
  4101.9   50.79  4231.3   43.59  4381.3   37.89  4541.2   37.33  4551.3   37.29
  4561.3   36.29  4571.3   33.09  4591.3   28.19  4598.5   38.39  4598.6   38.39
  4606.6   38.43  4630.4   38.55  4667.3    38.6  4672.8   38.61    4673   38.04
    4708   38.14  4708.3   38.66  4731.6   38.79  4764.9   38.97 4786.39   35.69
  4786.5   35.67 4786.61   35.65  4788.8   35.32  4799.4    31.3  4814.5   25.58
 4814.61   25.53  4814.7    25.5  4814.8   25.47  4814.9   25.44  4825.3    22.2
    4832   20.41  4840.8   18.06  4857.9   16.55  4875.1   15.89    4878   15.78
  4897.6   14.05  4921.7   15.69  4932.9   15.76  4937.4   12.26  4955.2    6.65
  4966.7    1.33  4969.2     .34  4971.9    -.42    4978   -2.14    4991   -3.13
  5010.6   -4.51    5028   -1.55  5032.2     .44  5033.4    1.23  5054.3    7.76
  5067.8   12.29  5075.3   15.74  5080.3   15.51  5092.3   14.97  5107.5   15.59
  5144.1    18.9  5145.8   20.83 5145.87   20.91 5145.99   21.04  5146.1   21.17
  5146.2   21.28  5146.3   21.32  5149.8   22.56  5198.6   39.88 5199.99   39.87
  5200.1   39.87 5200.21   39.87  5200.3   39.87  5235.9    39.7  5267.6   39.63
  5299.3    39.6    5334    39.5  5346.3   39.46  5358.4   39.29  5370.2   39.27
  5428.4   39.19  5488.4   43.69  5568.4   43.89  5588.4   42.89  5608.4   42.89
  5638.4   45.09  5772.2   47.09  5822.2   47.89  6242.2   50.59
BR D #Mann= 5
  4101.9      .2  4799.4     .12  4932.9    .045  5075.3     .12  5149.8      .2
BR D Banks=4932.9,5075.3
BC Design=,, 0 ,, 0 ,,,,,,
BC HTab HWMax=51.01

Type RM Length L Ch R = 1 ,128028.8,1381.8,1381.8,1381.8
BEGIN DESCRIPTION:
Downstream Section of Bridge/Culvert/Weir
END DESCRIPTION:
XS GIS Cut Line= 5
      3107599.86     13842439.45      3107752.51     13841764.57
      3107841.96     13841296.68      3107917.65     13840856.31
      3108114.48      13840369.4
#Sta/Elev= 30
  4101.9   50.79  4231.3   43.59  4381.3   37.89  4551.3   37.29  4561.3   36.29
  4591.3   28.19  4598.5   38.39  4764.9   38.97  4788.8   35.32  4799.4    31.3
  4814.7    25.5  4840.8   18.06  4897.6   14.05  4932.9   15.76  4937.4   12.26
    4978   -2.14  5010.6   -4.51    5028   -1.55  5075.3   15.74  5107.5   15.59
  5144.1    18.9  5146.2   21.28  5149.8   22.56  5198.6   39.88  5428.4   39.19
  5488.4   43.69  5608.4   42.89  5638.4   45.09  5822.2   47.89  6242.2   50.59
#Mann= 5 ,-1 , 0
  4101.9      .2       0  4799.4     .12       0  4932.9    .045       0
  5075.3     .12       0  5149.8      .2       0
#XS Ineff= 2 , 0
            4805    39.5    5155            40.5
Permanent Ineff=
       F       F
Bank Sta=4932.9,5075.3
XS Rating Curve= 0
Exp/Cntr=.5,.3

Type RM Length L Ch R = 1 ,126647.0,1157.1,1270.1,1451.7
BEGIN DESCRIPTION:
Cross Section 126647.0
END DESCRIPTION:
XS GIS Cut Line= 6
      3109081.17     13843051.99      3109079.74     13843037.89
      3109031.58     13842556.24      3109079.74     13842040.18
       3109024.7     13841558.53      3109105.31     13840994.27
#Sta/Elev= 30
  3673.2    49.5  3937.4    42.9  4171.4    42.3  4564.1   45.08  4581.4    43.1
  4611.4    34.8  4641.4    30.7  4729.7    32.6  4802.6   29.39  4850.8   26.83
  4885.1   22.46  4930.7   14.16  4945.1   15.52  4971.7    -.46  4999.2   -3.93
  5028.3     .74  5045.5   10.62  5076.6   14.46  5098.6   19.12    5116   19.73
  5234.5    16.1  5324.5       7  5424.5    14.5  5454.5    18.5  5524.5    34.5
  5604.5    38.2  5633.2   42.97  5654.5    47.1  5684.5    46.2  5744.5      49
#Mann= 5 ,-1 , 0
  3673.2      .2       0  4564.1      .1       0  4945.1    .045       0
  5045.5      .1       0  5633.2      .2       0
Bank Sta=4945.1,5045.5
XS Rating Curve= 0
Exp/Cntr=.3,.1