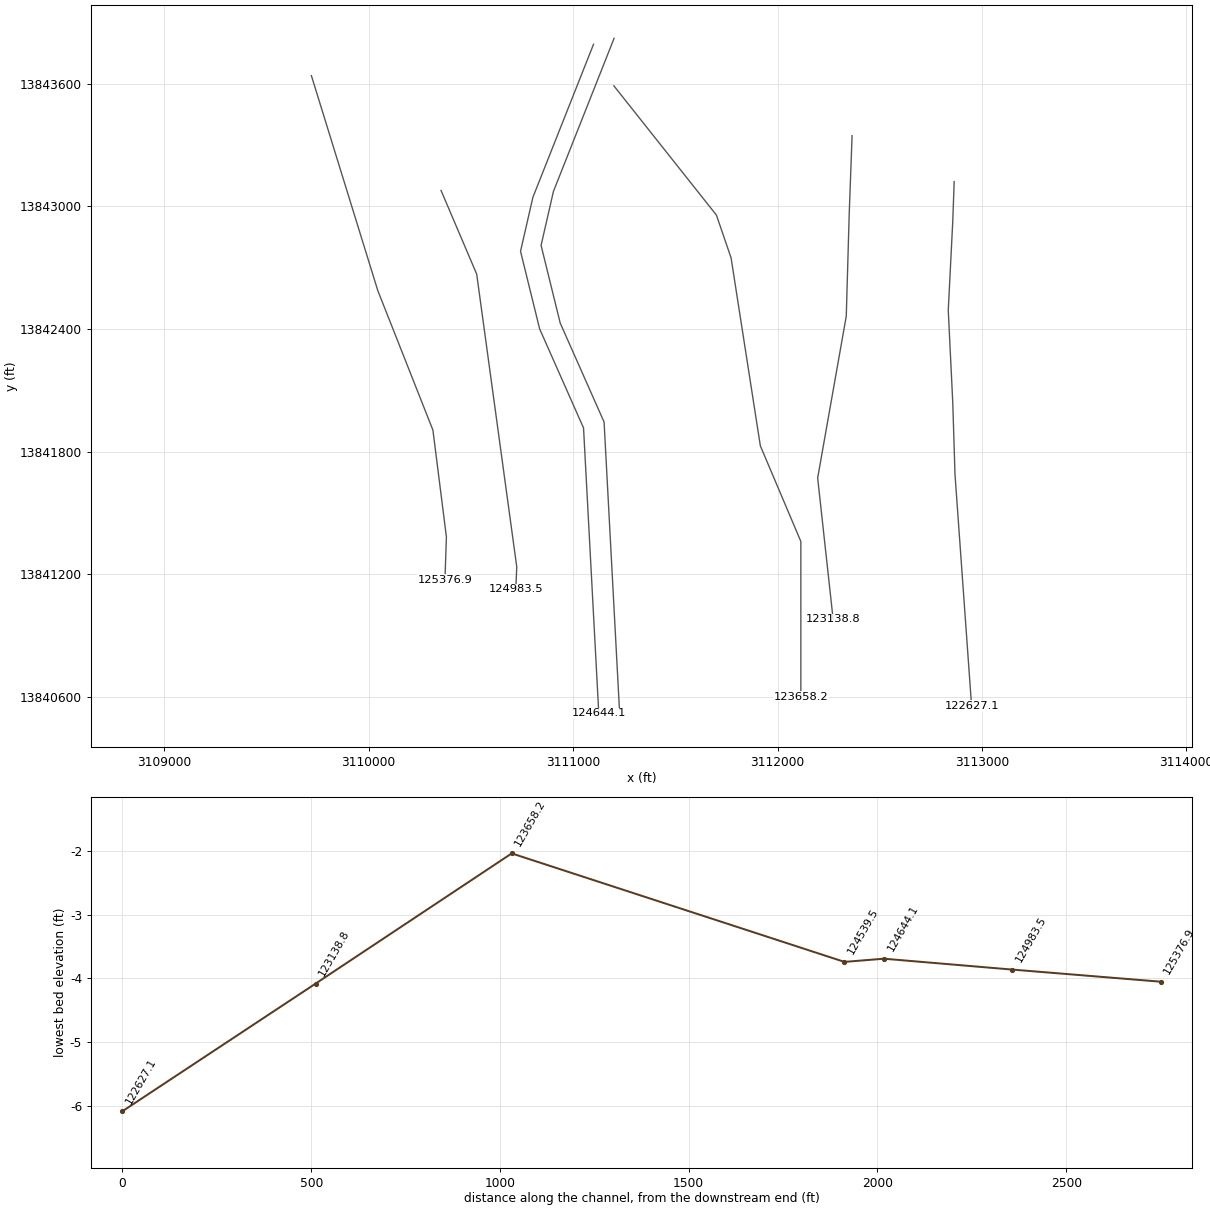
HEC-RAS study W100-00-00.prj: W100-00-00

--- W100-00-00.g01 (geometry) --- (continued)

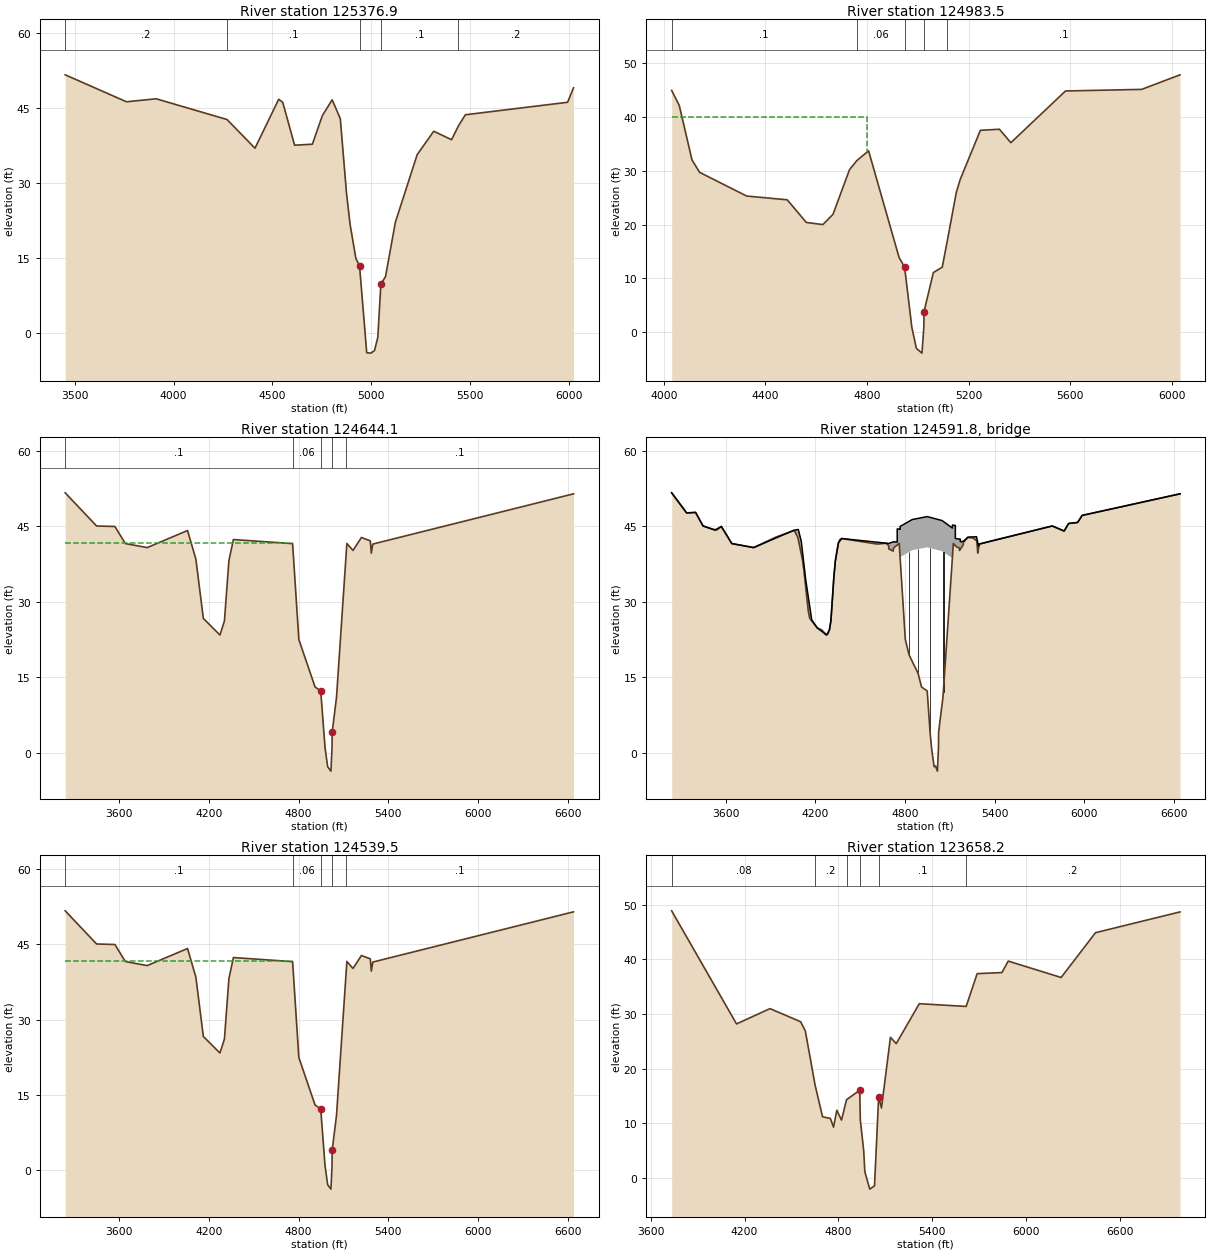
Type RM Length L Ch R = 1 ,125376.9,424.2,393.4,344.1
BEGIN DESCRIPTION:
Cross Section 125376.9
END DESCRIPTION:
XS GIS Cut Line= 5
      3109719.66     13843639.91      3110044.43     13842588.58
      3110314.15     13841906.01      3110380.21     13841383.07
      3110373.06     13841173.17
#Sta/Elev= 30
  3451.7    51.7  3761.7    46.3  3911.7    46.9  4270.1   42.75  4411.7      37
  4531.7    46.8  4552.1    46.2  4612.1    37.6  4702.1    37.8  4752.1    43.5
  4802.1    46.7  4843.4   42.91  4874.8   27.94  4892.9   21.73  4922.3   14.88
  4940.6   13.44    4977   -3.97  4997.5   -4.05  5016.2   -3.55    5033     -.9
  5048.5    9.75  5072.1    11.3  5122.1    22.2  5232.1    35.7    5316    40.4
    5406    38.7  5441.1   41.49    5476    43.7  5993.1    46.2  6023.1    49.1
#Mann= 5 ,-1 , 0
  3451.7      .2       0  4270.1      .1       0  4940.6    .045       0
  5048.5      .1       0  5441.1      .2       0
Bank Sta=4940.6,5048.5
XS Rating Curve= 0
Exp/Cntr=.3,.1

Type RM Length L Ch R = 1 ,124983.5,257.5,339.4,413.7
BEGIN DESCRIPTION:
Cross Section 124983.5 - Interpolated
END DESCRIPTION:
XS GIS Cut Line= 4
      3110353.91     13843078.26      3110528.34     13842669.03
      3110724.34     13841236.75      3110719.73     13841126.83
#Sta/Elev= 30
  4031.2    44.9  4061.2    42.1  4111.2      32  4141.2    29.7  4326.2    25.3
  4486.1    24.6  4561.1    20.4  4626.1      20  4666.1    21.9  4731.1    30.2
  4759.6   31.86  4806.1    33.7  4926.1    13.9  4947.9    12.1  4976.4     .92
  4994.3   -2.99  5016.2   -3.86  5023.5     .89  5024.4    3.85  5061.1    11.1
  5096.1    12.1  5116.2   17.06  5151.1    25.9  5166.1    28.3  5246.1    37.5
  5321.1    37.7  5366.1    35.2  5581.1    44.8  5881.1    45.1  6031.7    47.8
#Mann= 5 ,-1 , 0
  4031.2      .1       0  4759.6     .06       0  4947.9    .045       0
  5024.4     .06       0  5116.2      .1       0
#XS Ineff= 2 , 0
            4800      40
Permanent Ineff=
       F       F
Bank Sta=4947.9,5024.4
XS Rating Curve= 0
Exp/Cntr=.5,.3

Type RM Length L Ch R = 1 ,124644.1,104.6,104.6,104.6
BEGIN DESCRIPTION:
Upstream Section of Bridge/Culvert/Weir
END DESCRIPTION:
XS GIS Cut Line= 6
      3111100.02     13843793.37      3110803.36     13843044.73
      3110742.81     13842780.51      3110836.38     13842400.69
      3111051.06     13841916.29      3111125.65     13840519.98
#Sta/Elev= 30
  3237.8    51.7  3447.8    45.1  3570.3      45  3640.3    41.6  3786.6    40.8
  4056.6    44.2  4112.3    38.5  4162.3    26.7  4273.4    23.4  4303.4    26.2
  4333.4    38.2  4363.4    42.4  4759.6   41.59  4801.4   22.51  4909.9   13.06
  4947.9   12.27  4976.4    1.09  4994.3   -2.82  5016.2   -3.69  5023.5    1.06
  5024.4    4.02  5053.5   11.01  5116.2    38.7  5122.8   41.62  5163.9   40.23
    5220   42.81  5279.6   42.14  5286.4    39.7  5296.4    41.5  6639.7    51.5
#Mann= 5 ,-1 , 0
  3237.8      .1       0  4759.6     .06       0  4947.9    .045       0
  5024.4     .06       0  5116.2      .1       0
#XS Ineff= 2 , 0
            4755    41.8    5130            41.3
Permanent Ineff=
       F       F
Bank Sta=4947.9,5024.4
XS Rating Curve= 0
Exp/Cntr=.5,.3

Type RM Length L Ch R = 3 ,124591.8,,,
BEGIN DESCRIPTION:
WAUGH DRIVE
Structure ID: W00-47
END DESCRIPTION:
Bridge Culvert--1,0,-1,-1, 0
Deck Dist Width WeirC Skew NumUp NumDn MinLoCord MaxHiCord MaxSubmerge Is_Ogee
10,84.6,2.6,0, 60, 60, , , .95, 0, 1,1,,
  3237.8  3337.8  3397.8  3447.8  3527.8  3570.3  3640.3  3786.6  4056.6  4085.3
  4105.3  4122.3  4135.3  4152.3  4162.3  4175.3  4212.3  4273.4  4293.4  4303.4
  4323.4  4333.4  4353.4  4375.6  4671.8  4690.2    4691  4720.3  4721.8 4747.19
  4747.3  4760.7  4766.5  4767.1  4848.1  4947.9  5047.8  5116.2  5116.9  5122.8
  5136.2 5136.31  5163.3  5163.9  5169.3  5169.6  5188.8  5189.8    5220  5277.9
  5279.7  5286.4  5291.4  5296.4  5784.5  5864.5  5894.5  5954.5  5984.5  6639.7
    51.7    47.7    47.8    45.1    44.3      45    41.6    40.8   44.26    44.4
      42   37.64    34.3   30.94   28.97    26.4   24.81   23.41   24.41   26.21
   35.01   38.21   41.71   42.61   41.68   41.62   41.63   41.94   41.95   41.92
   44.52   44.46   44.43   45.02   46.39   46.97   46.18   44.69   45.28   45.26
   45.21   42.61    42.5    42.5   42.48   41.97   42.04   42.04   42.88   42.96
   42.71   41.79    41.1    41.5    45.1    44.1    45.6    45.8    47.2    51.5
    51.7    47.7    47.8    45.1    44.3      45    41.6    40.8    44.2   42.37
    39.5    36.4    32.8    28.1    26.7   26.21    24.8    23.4    24.4    26.2
      35    38.2    41.7    42.6   41.67   41.19   40.52    40.1   40.62   41.31
   41.31   41.61   38.89   38.91   40.28   40.86   40.07    38.7   39.01   41.62
   41.19   41.19   40.73   40.23   40.46   40.48   41.31   41.84   42.81   42.18
   42.13    39.7    40.6    41.5    45.1    44.1    45.6    45.8    47.2    51.5
  3237.8  3337.8  3397.8  3447.8  3527.8  3570.3  3640.3  3786.6  4056.6  4085.3
  4105.3  4122.3  4135.3  4152.3  4162.3  4175.3  4212.3  4273.4  4293.4  4303.4
  4323.4  4333.4  4353.4  4375.6  4671.8  4690.2    4691  4720.3  4721.8 4747.19
  4747.3  4760.7  4766.5  4767.1  4848.1  4947.9  5047.8  5116.2  5116.9  5122.8
  5136.2 5136.31  5163.3  5163.9  5169.3  5169.6  5188.8  5189.8    5220  5277.9
  5279.7  5286.4  5291.4  5296.4  5784.5  5864.5  5894.5  5954.5  5984.5  6639.7
    51.7    47.7    47.8    45.1    44.3      45    41.6    40.8   44.26    44.4
      42   37.64    34.3   30.94   28.97    26.4   24.81   23.41   24.41   26.21
   35.01   38.21   41.71   42.61   41.68   41.62   41.63   41.94   41.95   41.92
   44.52   44.46   44.43   45.02   46.39   46.97   46.18   44.69   45.28   45.26
   45.21   42.61    42.5    42.5   42.48   41.97   42.04   42.04   42.88   42.96
   42.71   41.79    41.1    41.5    45.1    44.1    45.6    45.8    47.2    51.5
   51.63   47.63   47.73   45.03   44.23   44.93   41.53   40.73   44.13    42.3
   39.43   36.33   32.73   28.03   26.63   26.14   24.73   23.33   24.33   26.13
   34.93   38.13   41.63   42.53    41.6   41.12   40.45   40.03   40.55   41.24
   41.24   41.54   38.82   38.84   40.21   40.79      40   38.63   38.94   41.55
   41.12   41.12   40.66   40.16   40.39   40.41   41.24   41.77   42.74   42.11
   42.06   39.63   40.53   41.43   45.03   44.03   45.53   45.73   47.13   51.43
Pier Skew, UpSta & Num, DnSta & Num=  ,4826.6, 2 ,4826.6, 2 , 0 , 0 , 0 ,,
     3.5     3.5
   18.36   40.95
     3.5     3.5
   18.29   40.88
Pier Skew, UpSta & Num, DnSta & Num=  ,4887, 2 ,4887, 2 , 0 , 0 , 0 ,,
     3.5     3.5
   14.57   41.51
     3.5     3.5
    14.5   41.44
Pier Skew, UpSta & Num, DnSta & Num=  ,4967, 2 ,4967, 2 , 0 , 0 , 0 ,,
     3.5     3.5
    2.54   41.72
     3.5     3.5
    2.47   41.65
Pier Skew, UpSta & Num, DnSta & Num=  ,5055.8, 2 ,5055.8, 2 , 0 , 0 , 0 ,,
     3.5     3.5
   10.28   40.94
     3.5     3.5
   10.21   40.87
Abutment Skew #Up #Dn= , 2 , 2
  4766.5  4801.4
   38.79   22.51
  4766.5  4801.4
   38.72   22.44
Abutment Skew #Up #Dn= , 2 , 2
  5053.5 5116.69
   11.01   38.83
  5053.5 5116.69
   10.94   38.76
BR Coef= 1 , 1 , 0 ,1.25, 0 ,,,.8,0,2,1,
WSPro=,,,, 1 ,,,, 0 ,,,, 0 ,,,,-1 ,-1 ,-1 , 0 , 0 , 0 , 0 , 0
BR U #Sta/Elev= 121
  3237.8    51.7  3337.8    47.7  3397.8    47.8  3447.8    45.1  3527.8    44.3
  3530.3    44.4  3540.3    44.3  3570.3      45  3640.3    41.6  3786.6    40.8
  3795.3   40.92  3867.8   41.94  3936.6    42.9  4045.3   44.08  4056.6    44.2
  4062.3      44  4082.3    42.8  4085.3   42.37  4105.3    39.5  4112.3    38.5
  4122.3    36.4  4135.3    32.8  4152.3    28.1  4162.3    26.7  4175.3   26.21
  4195.3   25.45  4212.3    24.8  4225.3   24.63  4243.4    24.4  4273.4    23.4
  4283.4    23.6  4293.4    24.4  4303.4    26.2  4323.4      35  4333.4    38.2
  4335.3   38.53  4353.4    41.7  4363.4    42.4  4375.6    42.6  4448.6   42.26
  4598.6   41.57  4614.6    41.5  4669.2   41.66  4671.7   41.67  4671.8   41.67
  4690.2   41.19    4691   40.52  4698.2   40.42  4720.3    40.1  4721.8   40.62
  4727.2   40.81  4731.7   40.96 4747.19   41.31  4747.3   41.31 4747.41   41.31
  4759.6   41.59  4760.7   41.61  4766.5   38.89 4766.61   38.84  4766.7   38.79
  4767.1   38.61  4767.2   38.56  4801.3   22.56  4801.4   22.51  4826.6   19.47
  4848.1   18.12  4856.5   17.59    4887   15.78  4909.9   13.06  4947.9   12.27
  4948.6   11.97    4967     4.1  4976.4    1.09  4983.7     -.6  4994.3   -2.82
  5003.6   -2.67  5016.2   -3.69  5023.5    1.06  5024.4    4.02    5035    6.68
  5047.8    9.68  5053.4   10.99  5053.5   11.01  5055.8   12.12  5093.4    28.6
  5116.2    38.7 5116.49   38.83  5116.6   38.87  5116.7   38.92  5116.9   39.01
  5122.8   41.62 5136.09    41.2  5136.2   41.19 5136.31   41.19  5144.1   40.94
  5163.3   40.73  5163.9   40.23  5169.3   40.46  5169.6   40.48  5188.8   41.31
  5189.8   41.84  5198.3   42.11    5199   42.14    5220   42.81  5228.2   42.79
  5252.6   42.74  5256.7   42.65  5277.9   42.18  5279.6   42.14  5279.7   42.13
  5286.4    39.7  5291.4    40.6  5296.4    41.5  5374.5    42.1  5784.5    45.1
  5864.5    44.1  5894.5    45.6  5954.5    45.8  5984.5    47.2  6029.7    47.5
  6639.7    51.5
BR U #Mann= 5
  3237.8      .1  4759.6     .06  4947.9    .045  5024.4     .06  5116.2      .1
BR U Banks=4947.9,5024.4
BR D #Sta/Elev= 121
  3237.8   51.63  3337.8   47.63  3397.8   47.73  3447.8   45.03  3527.8   44.23
  3530.3   44.33  3540.3   44.23  3570.3   44.93  3640.3   41.53  3786.6   40.73
  3795.3   40.85  3867.8   41.87  3936.6   42.83  4045.3   44.01  4056.6   44.13
  4062.3   43.93  4082.3   42.73  4085.3    42.3  4105.3   39.43  4112.3   38.43
  4122.3   36.33  4135.3   32.73  4152.3   28.03  4162.3   26.63  4175.3   26.14
  4195.3   25.38  4212.3   24.73  4225.3   24.56  4243.4   24.33  4273.4   23.33
  4283.4   23.53  4293.4   24.33  4303.4   26.13  4323.4   34.93  4333.4   38.13
  4335.3   38.46  4353.4   41.63  4363.4   42.33  4375.6   42.53  4448.6   42.19
  4598.6    41.5  4614.6   41.43  4669.2   41.59  4671.7    41.6  4671.8    41.6
  4690.2   41.12    4691   40.45  4698.2   40.35  4720.3   40.03  4721.8   40.55
  4727.2   40.74  4731.7   40.89 4747.19   41.24  4747.3   41.24 4747.41   41.24
  4759.6   41.52  4760.7   41.54  4766.5   38.82 4766.61   38.77  4766.7   38.72
  4767.1   38.54  4767.2   38.49  4801.3   22.49  4801.4   22.44  4826.6    19.4
  4848.1   18.05  4856.5   17.52    4887   15.71  4909.9   12.99  4947.9    12.2
  4948.6    11.9    4967    4.03  4976.4    1.02  4983.7    -.67  4994.3   -2.89
  5003.6   -2.74  5016.2   -3.76  5023.5     .99  5024.4    3.95    5035    6.61
  5047.8    9.61  5053.4   10.92  5053.5   10.94  5055.8   12.05  5093.4   28.53
  5116.2   38.63 5116.49   38.76  5116.6    38.8  5116.7   38.85  5116.9   38.94
  5122.8   41.55 5136.09   41.13  5136.2   41.12 5136.31   41.12  5144.1   40.87
  5163.3   40.66  5163.9   40.16  5169.3   40.39  5169.6   40.41  5188.8   41.24
  5189.8   41.77  5198.3   42.04    5199   42.07    5220   42.74  5228.2   42.72
  5252.6   42.67  5256.7   42.58  5277.9   42.11  5279.6   42.07  5279.7   42.06
  5286.4   39.63  5291.4   40.53  5296.4   41.43  5374.5   42.03  5784.5   45.03
  5864.5   44.03  5894.5   45.53  5954.5   45.73  5984.5   47.13  6029.7   47.43
  6639.7   51.43
BR D #Mann= 5
  3237.8      .1  4759.6     .06  4947.9    .045  5024.4     .06  5116.2      .1
BR D Banks=4947.9,5024.4
BC Design=,, 0 ,, 0 ,,,,,,
BC HTab HWMax=51.7

Type RM Length L Ch R = 1 ,124539.5,881.3,881.3,881.3
BEGIN DESCRIPTION:
Downstream Section of Bridge/Culvert/Weir
END DESCRIPTION:
XS GIS Cut Line= 6
      3111200.52     13843822.36      3110903.86     13843073.71
      3110843.31     13842809.49      3110936.88     13842429.67
      3111151.56     13841945.27      3111226.15     13840548.96
#Sta/Elev= 30
  3237.8   51.65  3447.8   45.05  3570.3   44.95  3640.3   41.55  3786.6   40.75
  4056.6   44.15  4112.3   38.45  4162.3   26.65  4273.4   23.35  4303.4   26.15
  4333.4   38.15  4363.4   42.35  4759.6   41.54  4801.4   22.46  4909.9   13.01
  4947.9   12.22  4976.4    1.04  4994.3   -2.87  5016.2   -3.74  5023.5    1.01
  5024.4    3.97  5053.5   10.96  5116.2   38.65  5122.8   41.57  5163.9   40.18
    5220   42.76  5279.6   42.09  5286.4   39.65  5296.4   41.45  6639.7   51.45
#Mann= 5 ,-1 , 0
  3237.8      .1       0  4759.6     .06       0  4947.9    .045       0
  5024.4     .06       0  5116.2      .1       0
#XS Ineff= 2 , 0
            4755    41.7    5130            41.3
Permanent Ineff=
       F       F
Bank Sta=4947.9,5024.4
XS Rating Curve= 0
Exp/Cntr=.5,.3

Type RM Length L Ch R = 1 ,123658.2,626.1,519.4,379.9
BEGIN DESCRIPTION:
Cross Section 123658.2
END DESCRIPTION:
XS GIS Cut Line= 6
      3111199.42     13843590.11      3111701.32     13842957.39
      3111772.88     13842748.21        3111916.     13841828.94
      3112114.16     13841361.05      3112114.16     13840601.01
#Sta/Elev= 30
  3734.2    48.9  4148.8    28.2  4362.8      31  4558.8    28.6  4588.8    26.9
  4651.1      17  4698.8    11.2  4748.8    10.9  4768.8     9.3  4789.9    12.4
  4819.9    10.6    4852   14.33  4936.3   16.06  4940.1   10.66    4962    4.92
    4969    1.15  5000.7   -2.04    5031   -1.43  5057.4    14.9  5075.5   12.82
  5132.7   25.74  5169.9    24.6  5317.2    31.9  5616.7    31.4  5687.2    37.4
  5845.6    37.6  5885.6    39.7  6223.8    36.7  6443.8    44.9  6983.8    48.7
#Mann= 6 ,-1 , 0
  3734.2     .08       0  4651.1      .2       0    4852     .08       0
  4936.3    .045       0  5057.4      .1       0  5616.7      .2       0
Bank Sta=4936.3,5057.4
XS Rating Curve= 0
Exp/Cntr=.3,.1

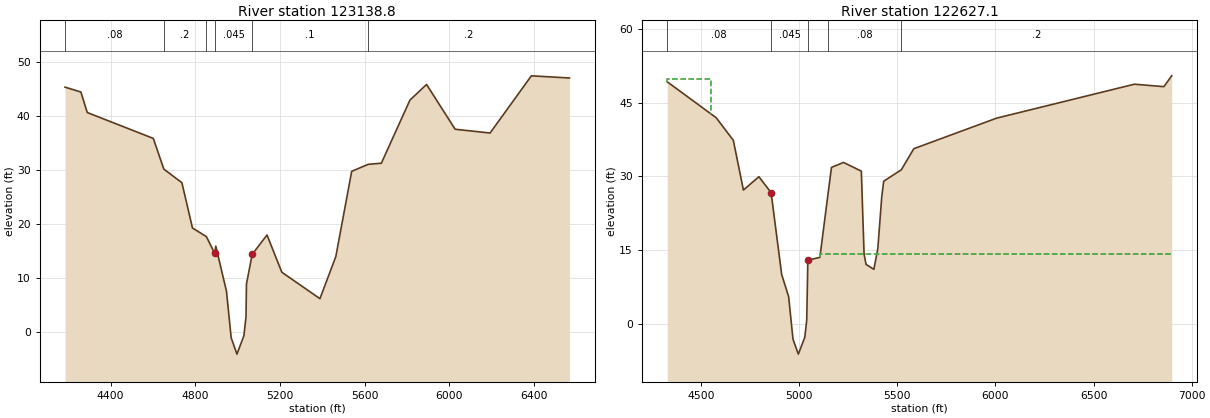
Type RM Length L Ch R = 1 ,123138.8,508.6,511.7,629.2
BEGIN DESCRIPTION:
Cross Section 123138.8 - Interpolated
END DESCRIPTION:
XS GIS Cut Line= 5
      3112364.85     13843346.16       3112350.8     13842964.53
      3112336.33     13842462.78      3112196.42     13841671.56
      3112272.04     13840980.62
#Sta/Elev= 30
  4184.4    45.4  4259.4    44.5  4289.4    40.7  4601.3    35.9  4651.1   30.21
  4736.3    27.7  4786.3    19.3    4852    17.7  4891.3    14.6  4896.5   15.93
  4946.9    7.58  4969.2   -1.06  4996.3   -4.08  5029.1    -.68  5039.1    2.82
  5041.3     8.9  5068.3    14.4  5138.3      18  5208.3    11.1  5388.3     6.2
  5463.3      14  5538.3    29.8  5616.7    31.1  5678.3    31.3  5813.3      43
  5891.8    45.9  6026.8    37.6  6191.8    36.9  6386.8    47.5  6566.8    47.1
#Mann= 6 ,-1 , 0
  4184.4     .08       0  4651.1      .2       0    4852     .08       0
  4891.3    .045       0  5068.3      .1       0  5616.7      .2       0
Bank Sta=4891.3,5068.3
XS Rating Curve= 0
Exp/Cntr=.5,.3

Type RM Length L Ch R = 1 ,122627.1,110,110,110
BEGIN DESCRIPTION:
Upstream Section of Bridge/Culvert/Weir
END DESCRIPTION:
XS GIS Cut Line= 6
      3112864.28     13843121.34      3112857.33      13842926.8
      3112835.32     13842491.94      3112857.33     13842040.56
      3112868.34     13841688.26       3112949.5     13840555.74
#Sta/Elev= 30
  4328.5   49.22  4577.6   41.94  4665.2   37.34  4716.5   27.24  4795.4   29.95
  4857.7   26.71  4911.3   10.13  4946.9    5.58  4969.2   -3.06  4996.3   -6.08
  5029.1   -2.68  5039.1     .82  5044.8   12.98  5106.1   13.58  5146.3   26.05
  5165.2   31.84  5226.6   32.85  5317.3   31.08  5331.2   14.24  5341.2   12.14
  5381.2   11.14  5401.2   15.34  5421.2   25.84  5431.2   29.04  5521.2   31.37
  5584.6   35.64  6006.1   41.84  6708.4   48.74  6858.4   48.24  6898.4   50.44
#Mann= 5 ,-1 , 0
  4328.5     .08       0  4857.7    .045       0  5044.8     .06       0
  5146.3     .08       0  5521.2      .2       0
#XS Ineff= 2 , 0
            4550    49.7    5106            14.3
Permanent Ineff=
       F       F
Bank Sta=4857.7,5044.8
XS Rating Curve= 0
Exp/Cntr=.5,.3