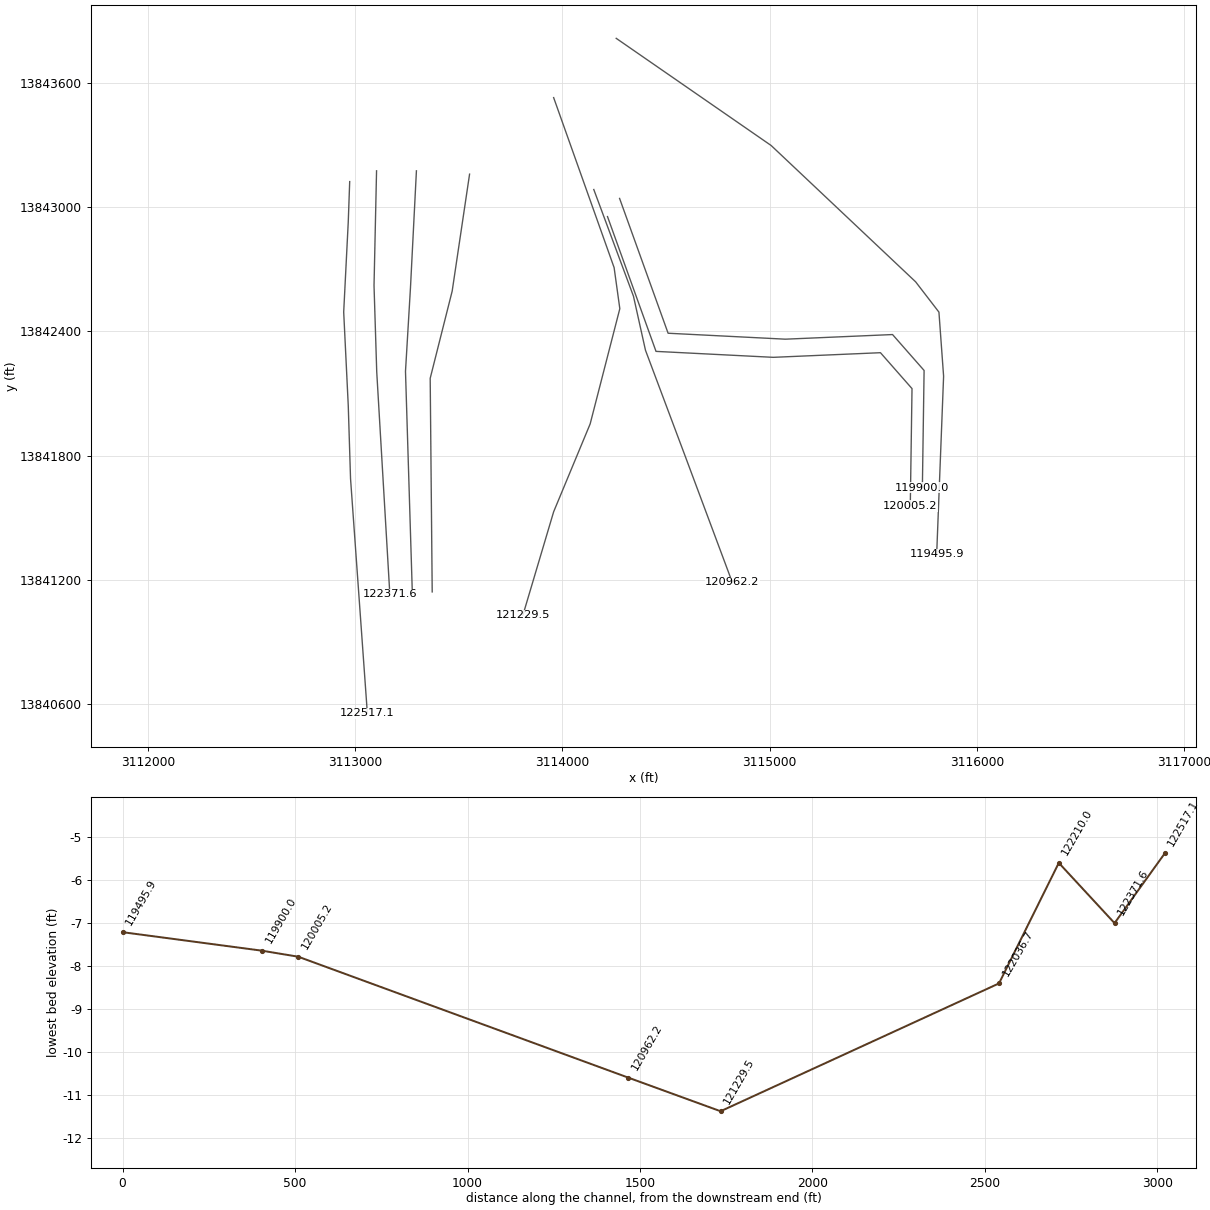
HEC-RAS study W100-00-00.prj: W100-00-00

--- W100-00-00.g01 (geometry) --- (continued)

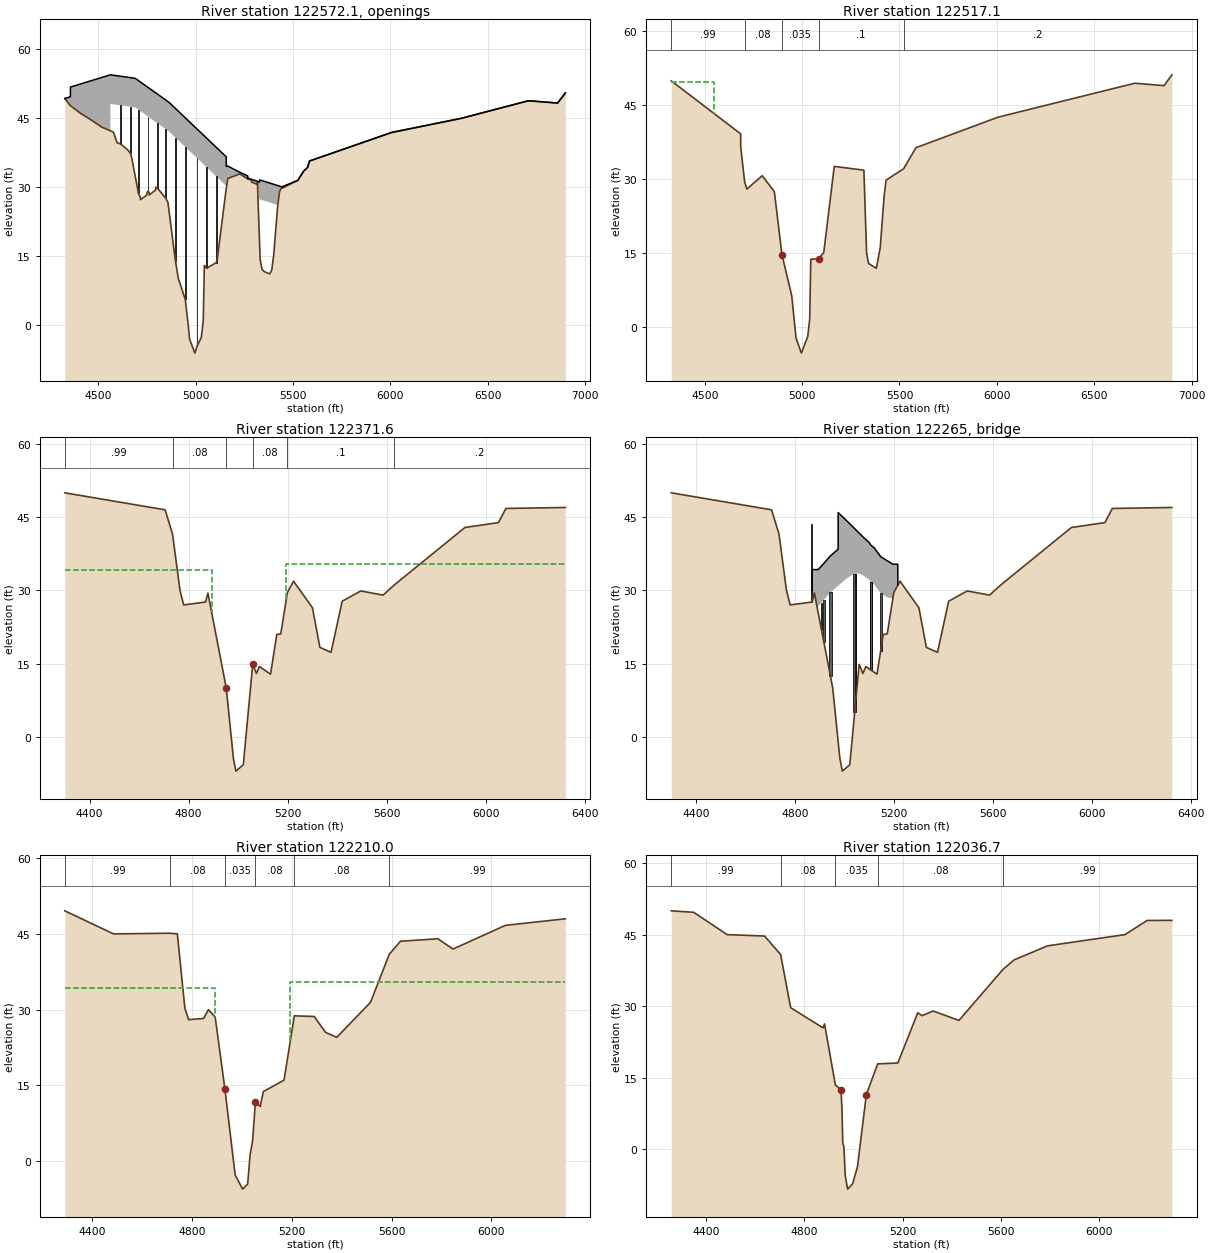
Type RM Length L Ch R = 4 ,122572.1,,,
BEGIN DESCRIPTION:
MONTROSE COURT
Structure ID: WOO-45&46
END DESCRIPTION:
Bridge Culvert--1,0,-1,-1, 0
Deck Dist Width WeirC Skew NumUp NumDn MinLoCord MaxHiCord MaxSubmerge Is_Ogee
10,90,2.6,0, 40, 37, , , .95, 0, 1,1,,
  4328.5 4357.29  4357.4  4411.2  4461.3  4517.6 4562.41  4562.5    4690  4862.4
  5157.2 5157.31 5157.49  5157.6  5161.9  5165.2  5226.6  5267.5  5267.9    5271
  5286.4  5286.9  5316.8  5317.3  5328.4  5329.4  5421.2  5431.2  5441.2  5442.4
  5444.6  5524.6  5554.6  5574.6  5584.6  6006.1  6366.1  6708.4  6858.4  6898.4
   49.18   49.57   51.67   52.37   53.02   53.75   54.33   54.33   53.57   48.39
   36.52   34.42   34.41   34.42   34.58   34.51   33.17   32.37   31.87   31.83
   31.62   31.62   31.22   31.21   31.06   31.51   30.28   30.15   30.02      30
   30.03   31.41   33.41   34.21   35.61   41.81    44.9    48.7    48.2    50.4
   49.18   47.64   47.64    45.9   44.59   42.98   42.17      48   47.24   42.06
   30.19   30.19   30.18   29.63   30.86    31.8   32.81   31.72   31.71   31.63
   31.54   31.04   30.53   31.04   26.83   27.28   26.05      29    29.8   29.76
    29.7    31.4    33.4    34.2    35.6    41.8    44.9    48.7    48.2    50.4
  4328.5 4357.29  4357.4  4411.2  4461.3  4517.6 4562.41  4562.5    4690  4862.4
  5157.2 5157.31 5157.49  5157.6  5161.9  5165.2  5226.6    5271  5286.4  5286.9
  5316.8  5317.3  5328.4  5329.4  5421.2  5431.2  5441.2  5444.6  5524.6  5554.6
  5574.6  5584.6  6006.1  6366.1  6708.4  6858.4  6898.4
   49.97   49.57   51.67   52.37   53.02   53.75   54.33   54.33   53.57   48.39
   36.52   34.42   34.41   34.42   34.58   34.51    33.6   32.42   32.33   31.83
   31.32   31.83   31.06   31.51   30.28   30.15   30.59   30.49   32.19   34.19
   34.99   36.39   42.59   45.69   49.49   48.99   51.19
   49.97   48.43   48.43   46.69   45.38   43.77   42.96   48.79   48.03   42.85
   30.98   30.98   30.97   30.42   31.65   32.59    33.6   32.42   32.33   31.83
   31.32   31.83   27.62   28.07   26.84   29.79   30.59   30.49   32.19   34.19
   34.99   36.39   42.59   45.69   49.49   48.99   51.19
Pier Skew, UpSta & Num, DnSta & Num=  ,4614.7, 2 ,4614.7, 2 , 0 , 0 , 0 ,,
       3       3
   38.26    48.7
       3       3
   39.05   49.49
Pier Skew, UpSta & Num, DnSta & Num=  ,4665.2, 2 ,4665.2, 2 , 0 , 0 , 0 ,,
       3       3
   36.09    48.4
       3       3
   36.88   49.19
Pier Skew, UpSta & Num, DnSta & Num=  ,4705.4, 2 ,4705.4, 2 , 0 , 0 , 0 ,,
       3       3
   27.55   47.82
       3       3
   28.34   48.61
Pier Skew, UpSta & Num, DnSta & Num=  ,4755.3, 2 ,4755.3, 2 , 0 , 0 , 0 ,,
       3       3
   27.95   46.32
       3       3
   28.74   47.11
Pier Skew, UpSta & Num, DnSta & Num=  ,4805.2, 2 ,4805.2, 2 , 0 , 0 , 0 ,,
       3       3
   28.59   44.82
       3       3
   29.38   45.61
Pier Skew, UpSta & Num, DnSta & Num=  ,4846.4, 2 ,4846.4, 2 , 0 , 0 , 0 ,,
       3       3
   26.42   43.59
       3       3
   27.21   44.38
Pier Skew, UpSta & Num, DnSta & Num=  ,4896.5, 2 ,4896.5, 2 , 0 , 0 , 0 ,,
       3       3
    12.5   41.75
       3       3
   13.29   42.54
Pier Skew, UpSta & Num, DnSta & Num=  ,4946.9, 2 ,4946.9, 2 , 0 , 0 , 0 ,,
       3       3
    3.99   39.71
       3       3
    4.78    40.5
Pier Skew, UpSta & Num, DnSta & Num=  ,5007.1, 2 ,5007.1, 2 , 0 , 0 , 0 ,,
       3       3
   -5.85   37.29
       3       3
   -5.06   38.08
Pier Skew, UpSta & Num, DnSta & Num=  ,5056.2, 2 ,5056.2, 2 , 0 , 0 , 0 ,,
       3       3
   11.35   35.31
       3       3
   12.14    36.1
Pier Skew, UpSta & Num, DnSta & Num=  ,5106.1, 2 ,5106.1, 2 , 0 , 0 , 0 ,,
       3       3
    12.5    33.3
       3       3
   13.29   34.09
Abutment Skew #Up #Dn= , 2 , 2
  4562.3  4577.7
      48   41.89
  4562.3  4577.7
   48.79   42.68
Abutment Skew #Up #Dn= , 2 , 2
  5111.4 5157.69
   14.35   30.18
  5111.4 5157.69
   15.14   30.97
Abutment Skew #Up #Dn= , 2 , 2
  5302.3  5312.5
   30.77    30.6
  5302.3  5312.5
   31.56   31.39
Abutment Skew #Up #Dn= , 2 , 2
  5442.5 5452.59
   29.76   29.87
  5442.5 5452.59
   30.55   30.66
BR Coef= 1 , 1 , 0 ,1.25, 0 ,,,.8,0,2,0,
WSPro=,,,, 1 ,,,, 0 ,,,, 0 ,,,,-1 ,-1 ,-1 , 0 , 0 , 0 , 0 , 0
BR Coef= 1 , 1 , 0 ,1.25, 0 ,,,.8,0,2,0,
WSPro=,,,, 1 ,,,, 0 ,,,, 0 ,,,,-1 ,-1 ,-1 , 0 , 0 , 0 , 0 , 0
BC Mult= 3 ,3328.5,5254.2,3328.5,5254.2
BC Mult= 3 ,5205.9,7898.4,5205.9,7898.4
BR U #Sta/Elev= 103
  4328.5   49.18  4328.6   49.17  4356.1   47.68 4357.29   47.64  4357.4   47.64
 4357.51   47.63  4411.2    45.9  4461.3   44.59  4517.6   42.98  4562.2   42.18
  4562.3   42.18 4562.41   42.17  4562.5   42.17  4577.6    41.9  4577.7   41.89
  4596.8   39.61  4614.7   39.31  4651.1   38.06  4665.2    37.3  4671.3   36.43
    4690   32.31    4704   29.22  4705.4   28.68    4716   27.74  4716.5    27.2
  4749.8   28.22  4750.2   28.82  4755.3   29.01  4761.3   28.81  4761.7   28.23
    4795   29.33  4795.4   29.91  4805.2   29.67  4846.4   27.54  4857.7   26.67
  4862.4   25.12  4896.5   13.89  4911.3   10.09  4946.9    5.54  4960.8     .48
  4969.2    -3.1  4996.3   -6.12  5007.1   -4.65  5029.1   -2.72  5039.1     .78
  5044.8   12.94  5056.2   12.31  5084.8   13.02  5106.1   13.54  5111.3   14.32
  5111.4   14.35  5146.3   26.01  5154.5   28.75  5155.4   29.01 5157.09   29.49
  5157.2   29.52 5157.31   29.55  5157.4   29.58 5157.49    29.6  5157.6   29.63
  5161.9   30.86  5165.2    31.8  5225.7    32.8  5226.6   32.81  5267.5   31.72
  5267.9   31.71    5271   31.63  5278.5   31.62  5286.4   31.54  5286.9   31.04
 5302.41   30.78  5302.5   30.77  5312.5    30.6  5316.8   30.53  5317.3   31.04
  5328.4   17.59  5329.4   16.38  5331.2    14.2  5341.2    12.1  5351.2    11.6
  5381.2    11.1  5391.2      12  5401.2    15.3  5421.2    25.8  5431.2      29
  5441.2    29.8  5442.4   29.76  5442.5   29.76  5444.6    29.7 5452.39   29.87
  5452.5   29.87  5521.2   31.33  5524.6    31.4  5554.6    33.4  5574.6    34.2
  5584.6    35.6  5762.9   38.22  6006.1    41.8    6039   42.08  6366.1    44.9
  6708.4    48.7  6858.4    48.2  6898.4    50.4
BR U #Mann= 5
  4328.5     .08  4857.7    .045  5044.8     .06  5146.3     .08  5521.2      .2
BR U Banks=4857.7,5044.8
BR D #Sta/Elev= 103
  4328.5   49.97  4328.6   49.96  4356.1   48.47 4357.29   48.43  4357.4   48.43
 4357.51   48.42  4411.2   46.69  4461.3   45.38  4517.6   43.77  4562.2   42.97
  4562.3   42.97 4562.41   42.96  4562.5   42.96  4577.6   42.69  4577.7   42.68
  4596.8    40.4  4614.7    40.1  4651.1   38.85  4665.2   38.09  4671.3   37.22
    4690    33.1    4704   30.01  4705.4   29.47    4716   28.53  4716.5   27.99
  4749.8   29.01  4750.2   29.61  4755.3    29.8  4761.3    29.6  4761.7   29.02
    4795   30.12  4795.4    30.7  4805.2   30.46  4846.4   28.33  4857.7   27.46
  4862.4   25.91  4896.5   14.68  4911.3   10.88  4946.9    6.33  4960.8    1.27
  4969.2   -2.31  4996.3   -5.33  5007.1   -3.86  5029.1   -1.93  5039.1    1.57
  5044.8   13.73  5056.2    13.1  5084.8   13.81  5106.1   14.33  5111.3   15.11
  5111.4   15.14  5146.3    26.8  5154.5   29.54  5155.4    29.8 5157.09   30.28
  5157.2   30.31 5157.31   30.34  5157.4   30.37 5157.49   30.39  5157.6   30.42
  5161.9   31.65  5165.2   32.59  5225.7   33.59  5226.6    33.6  5267.5   32.51
  5267.9    32.5    5271   32.42  5278.5   32.41  5286.4   32.33  5286.9   31.83
 5302.41   31.57  5302.5   31.56  5312.5   31.39  5316.8   31.32  5317.3   31.83
  5328.4   18.38  5329.4   17.17  5331.2   14.99  5341.2   12.89  5351.2   12.39
  5381.2   11.89  5391.2   12.79  5401.2   16.09  5421.2   26.59  5431.2   29.79
  5441.2   30.59  5442.4   30.55  5442.5   30.55  5444.6   30.49 5452.39   30.66
  5452.5   30.66  5521.2   32.12  5524.6   32.19  5554.6   34.19  5574.6   34.99
  5584.6   36.39  5762.9   39.01  6006.1   42.59    6039   42.87  6366.1   45.69
  6708.4   49.49  6858.4   48.99  6898.4   51.19
BR D #Mann= 5
  4328.5     .08  4857.7    .045  5044.8     .06  5146.3     .08  5521.2      .2
BR D Banks=4857.7,5044.8
BC Design=,, 0 ,, 0 ,,,,,,
BC HTab HWMax=50.44

Type RM Length L Ch R = 1 ,122517.1,145.5,145.5,145.5
BEGIN DESCRIPTION:
Downstream Section of Bridge/Culvert/Weir
Rosemont Bridge LOMR by BJE Engineering
by Burton L. Johnson, P.E.
March1, 2011
channel "n" value modified to reflect vegetation management measures
END DESCRIPTION:
XS GIS Cut Line= 6
      3112974.28     13843121.95      3112967.33     13842927.42
      3112945.32     13842492.56      3112967.33     13842041.18
      3112978.34     13841688.88      3113059.49     13840556.35
#Sta/Elev= 30
  4328.5   49.92 4684.71   39.15 4685.08   36.49    4705   29.42  4716.5   27.94
  4795.4   30.65  4857.7   27.41  4896.5   14.63  4946.9    6.28  4969.2   -2.36
  4996.3   -5.38  5029.1   -1.98  5039.1    1.52  5044.8   13.68  5084.8   13.76
  5111.3   15.06  5165.2   32.54  5317.3   31.78  5331.2   14.94  5341.2   12.84
  5381.2   11.84  5401.2   16.04  5421.2   26.54  5431.2   29.74  5521.2   32.07
  5584.6   36.34  6006.1   42.54  6708.4   49.44  6858.4   48.94  6898.4   51.14
#Mann= 5 ,-1 , 0
  4328.5     .99       0    4705     .08       0  4896.5    .035       0
  5084.8      .1       0  5521.2      .2       0
#XS Ineff= 2 , 0
            4550    49.7    5106            14.3
Permanent Ineff=
       F       F
Bank Sta=4896.5,5084.8
XS Rating Curve= 0
Exp/Cntr=.5,.3

Type RM Length L Ch R = 1 ,122371.6,161.6,161.6,161.6
BEGIN DESCRIPTION:
Rosemont Bridge LOMR by BJE Engineering
by Burton L. Johnson, P.E.
March1, 2011
New cross section (see description in corrected effective)
Section Upstream of Rosemont Bridge
Bridge modeled from As-Builts
channel "n" value modified to reflect vegetation management measures
END DESCRIPTION:
XS GIS Cut Line= 4
  3113103.85247813843173.9020996 3113091.644287113842620.2062988
 3113104.707885713842203.9924927 3113167.965698213841130.2924805
#Sta/Elev= 30
    4300      50  4705.1   46.52 4735.11 41.5498 4765.11   30.06 4780.12   27.04
 4868.84   27.64    4878   29.48    4952   10.07    4981    -4.4    4991      -7
    5021    -5.7    5059   14.87    5074      13    5086   14.42    5131   12.86
 5156.22   20.98 5172.39   21.11    5199   29.59    5224    31.9  5300.3   26.46
 5330.35   18.35 5375.43   17.33 5420.51    27.8 5495.64    29.9  5585.8   29.05
 5630.87   31.13 5916.37    42.9  6051.6    43.9 6081.65    46.8 6322.07      47
#Mann= 6 ,-1 , 0
    4300     .99       0 4735.11     .08       0    4952    .035       0
    5059     .08       0    5199      .1       0 5630.87      .2       0
#XS Ineff= 2 , 0
            4893   34.28    5195           35.37
Permanent Ineff=
       F       F
Bank Sta=4952,5059
XS Rating Curve= 0
Exp/Cntr=.5,.3

Type RM Length L Ch R = 3 ,122265  ,,,
BEGIN DESCRIPTION:
Proposed Rosemont Bridge
Pedestrian Bridge Analysis by BJE Engineering
by Burton Johnson, P.E., March 1, 2011
Added Proposed Bridge Configuration from Construction Plans
Notes:
1.  Prop Bridge is a steel structure 7.5' tall.  It is a truss and will allow flow through.  However, model assumes full depth is blocked.
2.  Bridge includes a ramp down to left bank trail and main structure above BFE over Memorial Drive.  Only modeled the ramp, since the high bridge is well above BFE.
END DESCRIPTION:
Bridge Culvert--1,0,-1,-1, 0
Deck Dist Width WeirC Skew NumUp NumDn MinLoCord MaxHiCord MaxSubmerge Is_Ogee
102,10,2.6,0, 25, 25, , , .98, 0, 3,3,,
    4869    4869    4893    4903    4916    4942    4974    4974    5000    5010
    5020    5030    5044    5050    5060    5070    5080    5090    5100    5106
    5120    5146    5195    5215    5215
      30   34.28   34.28    34.8   35.53   37.05   38.45   45.95    44.7    44.2
    43.7    43.2    42.5    42.2    41.7    41.2    40.7   40.25    39.8    39.3
    38.7   36.92   35.37   35.37    31.2
                   26.78    27.3   28.03   29.55   30.95   30.95    32.1    32.5
   32.85    33.2   33.43   33.45   33.45    33.2   32.95    32.5   32.25    31.8
    31.2   29.42   27.87
    4869    4869    4893    4903    4916    4942    4974    4974    5000    5010
    5020    5030    5044    5050    5060    5070    5080    5090    5100    5106
    5120    5146    5195    5215    5215
      30   34.28   34.28    34.8   35.53   37.05   38.45   45.95    44.7    44.2
    43.7    43.2    42.5    42.2    41.7    41.2    40.7   40.25    39.8    39.3
    38.7   36.92   35.37   35.37    31.2
                   26.78    27.3   28.03   29.55   30.95   30.95    32.1    32.5
   32.85    33.2   33.43   33.45   33.45    33.2   32.95    32.5   32.25    31.8
    31.2   29.42   27.87
Pier Skew, UpSta & Num, DnSta & Num=  ,4867, 3 ,4867, 3 , 0 , 0 , 0 ,,
    4.98       3       3
      26   39.03   43.68
    4.98       3       3
      26   39.03   43.68
Pier Skew, UpSta & Num, DnSta & Num=  ,4907, 3 ,4907, 3 , 3 , 3 , 0 ,,
    5.33       3    4.97
      16   37.24   41.89
    5.33       3    4.97
      16   37.24   41.89
Pier Skew, UpSta & Num, DnSta & Num=  ,4916, 3 ,4916, 3 , 3 , 3 , 0 ,,
    4.69       3    6.05
       4   23.38   28.03
    4.69       3    6.05
       4   23.38   28.03
Pier Skew, UpSta & Num, DnSta & Num=  ,4942, 3 ,4942, 3 , 0 , 0 , 0 ,,
    5.65       3       3
     7.5    24.9   29.55
    5.65       3       3
     7.5    24.9   29.55
Pier Skew, UpSta & Num, DnSta & Num=  ,4943, 3 ,4943, 3 , 3 , 3 , 0 ,,
    6.38       3   10.08
       9   35.29   39.94
    6.38       3   10.08
       9   35.29   39.94
Pier Skew, UpSta & Num, DnSta & Num=  ,5041, 3 ,5041, 3 , 3 , 3 , 0 ,,
    6.21       3   10.58
    13.5   30.42   35.07
    6.21       3   10.58
    13.5   30.42   35.07
Pier Skew, UpSta & Num, DnSta & Num=  ,5044, 3 ,5044, 3 , 0 , 0 , 0 ,,
    5.73       3       3
      13   28.78   33.43
    5.73       3       3
      13   28.78   33.43
Pier Skew, UpSta & Num, DnSta & Num=  ,5106, 3 ,5106, 3 , 3 , 3 , 0 ,,
    5.63       3    9.63
       5    27.3   31.95
    5.63       3    9.63
       5    27.3   31.95
Pier Skew, UpSta & Num, DnSta & Num=  ,5106, 3 ,5106, 3 , 0 , 0 , 0 ,,
    5.65       3       3
       9   27.15    31.8
    5.65       3       3
       9   27.15    31.8
Pier Skew, UpSta & Num, DnSta & Num=  ,5146, 3 ,5146, 3 , 3 , 3 , 0 ,,
    4.88       3       7
      14   22.84   29.42
    4.88       3       7
      14   22.84   29.42
BR Coef= 1 , 1 , 0 ,, 0 ,,,.8,-1,.6,0,
WSPro=,,,, 1 ,,,, 0 ,,,, 0 ,,,,-1 ,-1 ,-1 , 0 , 0 , 0 , 0 , 0
BC Design=,, 0 ,, 0 ,,,,,,
BC HTab HWMax=50

Type RM Length L Ch R = 1 ,122210.0,173.3,173.3,173.3
BEGIN DESCRIPTION:
Rosemont Bridge LOMR by BJE Engineering
by Burton L. Johnson, P.E.
March1, 2011
New cross section (see description in corrected effective)
Section Downstream of Rosemont Bridge
channel "n" value modified to reflect vegetation management measures
END DESCRIPTION:
XS GIS Cut Line= 4
 3113296.192077613843173.9020996 3113267.466125513842609.6088867
 3113243.454528813842206.6320801 3113276.156677313841146.3209229
#Sta/Elev= 30
    4292   49.58 4487.25      45 4712.43   45.14 4742.58      45 4772.62   30.32
 4787.64      28 4847.72   28.24    4867   29.98    4894   28.52    4933   14.24
    4974    -2.8    5004    -5.6    5024    -4.6    5034     1.3    5044       4
    5055   11.72    5074   10.79    5087   13.75 5169.65   16.01    5211   28.76
 5290.73   28.63 5335.75   25.49 5380.77    24.5 5515.84   31.43 5590.87   40.95
 5635.89   43.55 5785.96   44.04 5845.99      42 6056.09    46.7  6296.2      48
#Mann= 6 ,-1 , 0
    4292     .99       0 4712.43     .08       0    4933    .035       0
    5055     .08       0    5211     .08       0 5590.87     .99       0
#XS Ineff= 2 , 0
            4893   34.28    5195           35.37
Permanent Ineff=
       F       F
Bank Sta=4933,5055
XS Rating Curve= 0
Exp/Cntr=.3,.1

Type RM Length L Ch R = 1 ,122036.7,807.2,807.2,807.2
BEGIN DESCRIPTION:
Rosemont Bridge LOMR by BJE Engineering
by Burton L. Johnson, P.E.
March1, 2011
New cross section (see description in corrected effective)
channel "n" value modified to reflect vegetation management measures
END DESCRIPTION:
XS GIS Cut Line= 4
 3113552.645080613843157.8739014 3113468.683471713842593.5631104
 3113362.630493213842172.8519287 3113372.326721213841142.3137207
#Sta/Elev= 30
    4260      50 4350.99   49.69 4487.48      45 4639.13   44.71 4704.57   40.83
 4745.28   29.67 4876.93   25.44    4883   26.28    4927   13.46    4950    12.5
    4954     8.2    4957     1.3    4962      .4    4967    -5.5    4977    -8.4
    4997    -7.3    5017    -3.7    5053   11.44    5099   17.88    5181   18.07
    5262   28.61  5279.4      28  5324.4   28.98  5429.4      27 5609.41   37.76
 5654.41   39.72 5789.42   42.65 6104.43   45.01 6194.43   47.98 6294.98      48
#Mann= 5 ,-1 , 0
    4260     .99       0 4704.57     .08       0    4927    .035       0
    5099     .08       0 5609.41     .99       0
Bank Sta=4950,5053
XS Rating Curve= 0
Exp/Cntr=.3,.1

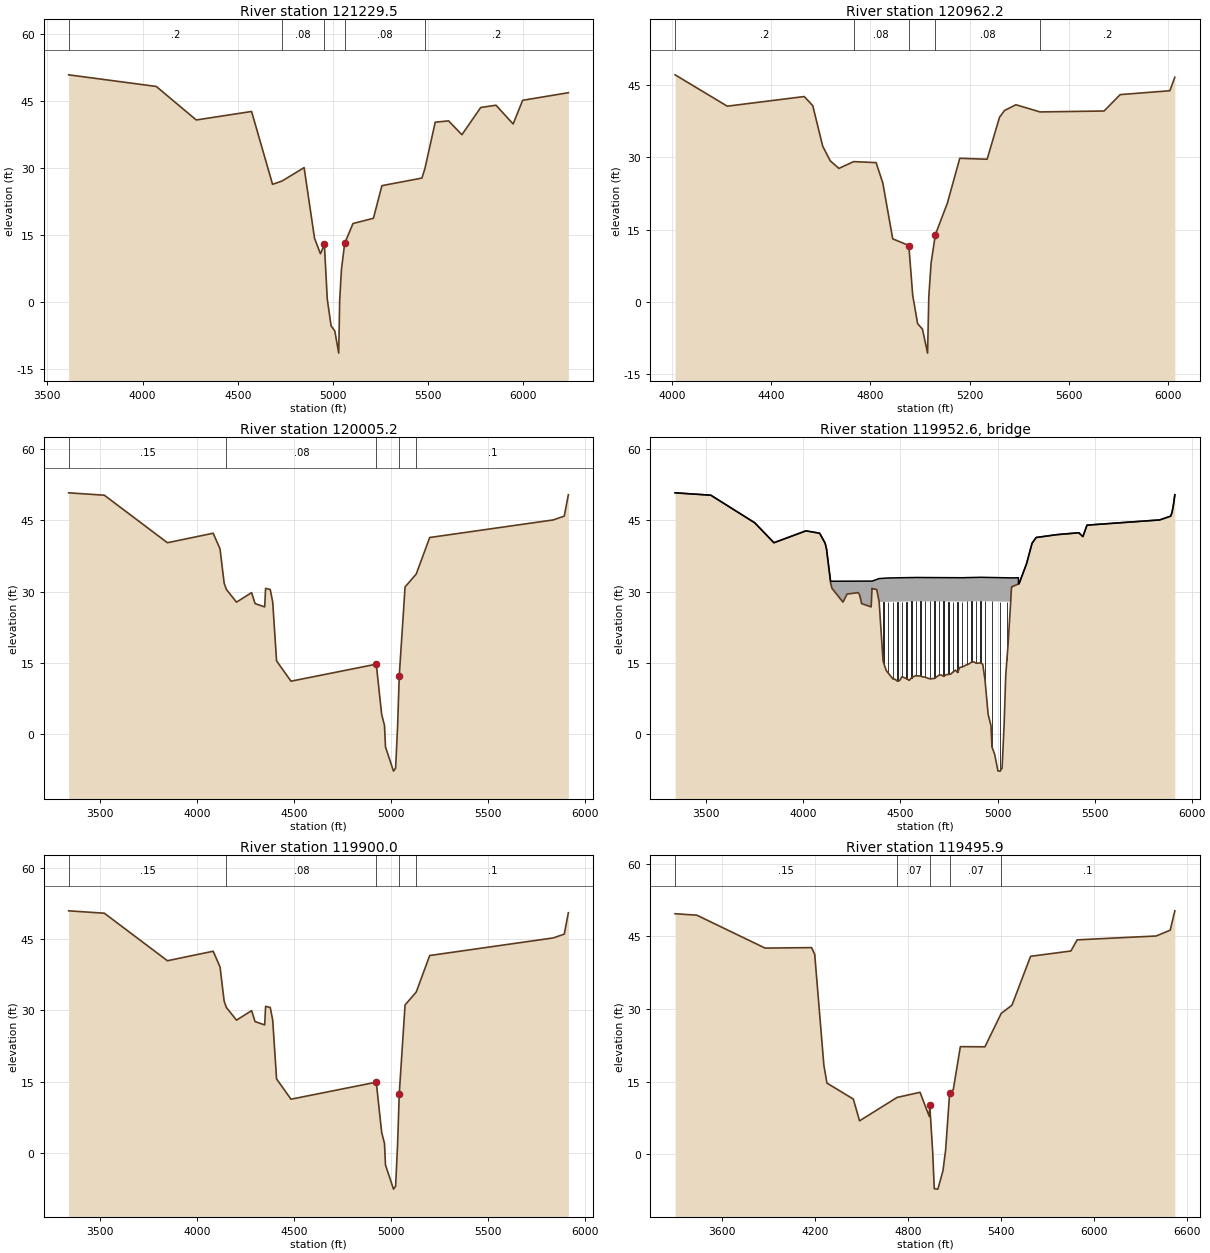
Type RM Length L Ch R = 1 ,121229.5,192.5,267.3,435.8
BEGIN DESCRIPTION:
Cross Section 121229.5
END DESCRIPTION:
XS GIS Cut Line= 6
      3113958.21     13843527.12      3114249.96     13842706.93
      3114277.48     13842508.76      3114134.36      13841952.8
      3113958.21     13841528.94      3113810.04     13841030.55
#Sta/Elev= 30
    3612    50.9    4072    48.3    4282    40.8  4572.5    42.7  4682.6    26.4
  4732.5   27.14  4848.3   30.14  4903.1   14.32  4934.1   10.86  4954.7   12.94
    4970     .68  4989.9   -5.25  5009.5   -6.41    5030  -11.37    5035     .37
  5044.3    7.36  5061.4   13.19    5105   17.63  5212.2    18.8  5256.8    26.1
  5466.8    27.8  5482.7   29.95  5536.8    40.3  5606.8    40.6  5676.8    37.5
  5775.8    43.6  5855.8    44.1  5945.8    39.9  5995.8    45.2  6235.8    46.9
#Mann= 5 ,-1 , 0
    3612      .2       0  4732.5     .08       0  4954.7    .045       0
  5061.4     .08       0  5482.7      .2       0
Bank Sta=4954.7,5061.4
XS Rating Curve= 0
Exp/Cntr=.3,.1

Type RM Length L Ch R = 1 ,120962.2,488.7,957,1144
BEGIN DESCRIPTION:
Cross Section 120962.2 - Interpolated
END DESCRIPTION:
XS GIS Cut Line= 5
      3114151.88     13843083.75      3114343.33     13842568.92
      3114401.22     13842308.39      3114589.38     13841806.64
      3114820.14     13841188.22
#Sta/Elev= 30
  4013.5    47.1  4223.5    40.6  4533.5    42.6  4567.8    40.7  4607.8    32.3
  4637.8    29.3  4672.8    27.7  4732.5   29.11  4822.8    28.9  4849.7    24.7
  4889.7    13.1  4954.6   11.72    4970    1.46  4989.9   -4.47  5009.5   -5.63
    5030  -10.59    5035    1.15  5044.3    8.14  5061.4   13.97  5109.7    20.5
  5159.7    29.8  5269.7    29.6  5319.7    38.3  5339.7    39.7  5385.6    40.9
  5482.7   39.41  5740.6    39.6  5805.6      43  6005.6    43.8  6025.6    46.6
#Mann= 5 ,-1 , 0
  4013.5      .2       0  4732.5     .08       0  4954.6    .045       0
  5061.4     .08       0  5482.7      .2       0
Bank Sta=4954.6,5061.4
XS Rating Curve= 0
Exp/Cntr=.5,.3

Type RM Length L Ch R = 1 ,120005.2,105.2,105.2,105.2
BEGIN DESCRIPTION:
Upstream Section of Bridge/Culvert/Weir
END DESCRIPTION:
XS GIS Cut Line= 6
      3114218.07     13842953.14      3114452.11     13842302.79
      3115018.12     13842274.08      3115534.94     13842296.42
      3115687.18     13842123.18      3115678.83     13841556.87
#Sta/Elev= 30
 3339.04   50.77 3522.86   50.27 3848.08   40.27 4083.59   42.27 4118.94   38.97
 4140.15   31.77  4151.5   30.45 4203.78   27.77 4281.55   29.77 4299.43   27.47
 4348.92   26.77 4353.66   30.68 4377.63   30.42 4390.21   27.82 4410.19   15.41
 4484.43   11.14 4923.79   14.72 4951.71    4.14 4966.21    1.81 4971.23   -2.68
 5012.66   -7.78 5023.47   -7.15 5033.79    1.77 5042.28    12.3 5072.13   30.97
  5129.7   33.69 5199.16   41.37 5835.67   45.07 5892.23   45.87 5913.44   50.37
#Mann= 5 ,-1 , 0
 3339.04     .15       0  4151.5     .08       0 4923.79    .045       0
 5042.28    .055       0  5129.7      .1       0
#XS Ineff= 2 , 0
            4130      32    5105              32
Permanent Ineff=
       F       F
Bank Sta=4923.79,5042.28
XS Rating Curve= 0
Exp/Cntr=.5,.3

Type RM Length L Ch R = 3 ,119952.6,,,
BEGIN DESCRIPTION:
MEMORIAL DRIVE - Skewed 45 Degrees
Structure ID: WOO-43
END DESCRIPTION:
Bridge Culvert--1,0,-1,-1, 0
Deck Dist Width WeirC Skew NumUp NumDn MinLoCord MaxHiCord MaxSubmerge Is_Ogee
10,85.2,2.6,0, 43, 43, , , .95, 0, 1,1,,
 3339.04 3522.86  3749.1 3848.08 4012.89 4083.59 4111.87 4118.94 4140.15 4147.22
 4203.78 4224.99 4281.55 4288.62 4295.69 4299.43 4348.92 4353.66 4354.65 4377.63
 4390.21 4412.98 4436.95 4579.24 4817.95 4912.33 5067.73 5072.13 5107.65 5107.75
 5110.93 5149.67 5177.95 5199.16 5305.42 5418.54 5439.75 5460.96 5835.67 5892.23
  5899.3 5906.37 5913.44
    50.8    50.3    44.5    40.3    42.8    42.3   40.21   39.01    32.2    32.2
   32.21   32.21   32.22   32.22   32.22   32.22   32.23   32.23   32.23   32.58
   32.76   32.82   32.89   32.99   32.94   33.03   32.91    32.9   32.94   31.63
   31.68    35.9    40.2    41.4      42    42.4    41.6      44    45.1    45.9
    46.7    48.3    50.4
    50.8    50.3    44.5    40.3    42.8    42.3    40.2      39    31.8    30.7
    27.8    29.5    29.8    29.4    28.3    27.5    26.8   30.71   30.63   30.45
   27.85    27.8   27.87   27.97   27.92   28.01   27.89      31   31.61   31.62
   31.67    35.9    40.2    41.4      42    42.4    41.6      44    45.1    45.9
    46.7    48.3    50.4
 3339.04 3522.86  3749.1 3848.08 4012.89 4083.59 4111.87 4118.94 4140.15 4147.22
 4203.78 4224.99 4281.55 4288.62 4295.69 4299.43 4348.92 4353.66 4354.65 4377.63
 4390.21 4412.98 4436.95 4579.24 4817.95 4912.33 5067.73 5072.13 5107.65 5107.75
 5110.93 5149.67 5177.95 5199.16 5305.42 5418.54 5439.75 5460.96 5835.67 5892.23
  5899.3 5906.37 5913.44
    50.9    50.4    44.6    40.4    42.9    42.4    40.3    39.1    32.2    32.2
   32.21   32.21   32.22   32.22   32.22   32.22   32.23   32.23   32.23   32.58
   32.76   32.82   32.89   32.99   32.94   33.03   32.91    32.9   32.94   31.72
   31.77      36    40.3    41.5    42.1    42.5    41.7    44.1    45.2      46
    46.8    48.4    50.5
    50.9    50.4    44.6    40.4    42.9    42.4    40.3    39.1    31.9    30.8
    27.9    29.6    29.9    29.5    28.4    27.6    26.9   30.81   30.73   30.55
   27.95    27.9   27.97   28.07   28.02   28.11   27.99    31.1   31.71   31.72
   31.77      36    40.3    41.5    42.1    42.5    41.7    44.1    45.2      46
    46.8    48.4    50.5
Pier Skew, UpSta & Num, DnSta & Num=  ,4413, 2 ,4413, 2 , 0 , 0 , 0 ,,
     2.5     2.5
   13.91    28.8
     2.5     2.5
   14.01    28.9
Pier Skew, UpSta & Num, DnSta & Num=  ,4436.9, 2 ,4436.9, 2 , 0 , 0 , 0 ,,
     2.5     2.5
   11.81   28.87
     2.5     2.5
   11.91   28.97
Pier Skew, UpSta & Num, DnSta & Num=  ,4460.7, 2 ,4460.7, 2 , 0 , 0 , 0 ,,
     2.5     2.5
   10.66   28.89
     2.5     2.5
   10.76   28.99
Pier Skew, UpSta & Num, DnSta & Num=  ,4484.5, 2 ,4484.5, 2 , 0 , 0 , 0 ,,
     2.5     2.5
   10.19   28.91
     2.5     2.5
   10.29   29.01
Pier Skew, UpSta & Num, DnSta & Num=  ,4508.2, 2 ,4508.2, 2 , 0 , 0 , 0 ,,
     2.5     2.5
   11.05   28.91
     2.5     2.5
   11.15   29.01
Pier Skew, UpSta & Num, DnSta & Num=  ,4531.9, 2 ,4531.9, 2 , 0 , 0 , 0 ,,
     2.5     2.5
   10.68   28.92
     2.5     2.5
   10.78   29.02
Pier Skew, UpSta & Num, DnSta & Num=  ,4555.7, 2 ,4555.7, 2 , 0 , 0 , 0 ,,
     2.5     2.5
   10.78   28.95
     2.5     2.5
   10.88   29.05
Pier Skew, UpSta & Num, DnSta & Num=  ,4579.3, 2 ,4579.3, 2 , 0 , 0 , 0 ,,
     2.5     2.5
   11.34   28.97
     2.5     2.5
   11.44   29.07
Pier Skew, UpSta & Num, DnSta & Num=  ,4603.7, 2 ,4603.7, 2 , 0 , 0 , 0 ,,
     2.5     2.5
   11.25   28.96
     2.5     2.5
   11.35   29.06
Pier Skew, UpSta & Num, DnSta & Num=  ,4627.5, 2 ,4627.5, 2 , 0 , 0 , 0 ,,
     2.5     2.5
   11.01   28.96
     2.5     2.5
   11.11   29.06
Pier Skew, UpSta & Num, DnSta & Num=  ,4651.1, 2 ,4651.1, 2 , 0 , 0 , 0 ,,
     2.5     2.5
   10.69   28.95
     2.5     2.5
   10.79   29.05
Pier Skew, UpSta & Num, DnSta & Num=  ,4675.1, 2 ,4675.1, 2 , 0 , 0 , 0 ,,
     2.5     2.5
   10.75   28.94
     2.5     2.5
   10.85   29.04
Pier Skew, UpSta & Num, DnSta & Num=  ,4698.7, 2 ,4698.7, 2 , 0 , 0 , 0 ,,
     2.5     2.5
    11.4   28.96
     2.5     2.5
    11.5   29.06
Pier Skew, UpSta & Num, DnSta & Num=  ,4722.6, 2 ,4722.6, 2 , 0 , 0 , 0 ,,
     2.5     2.5
   11.22   28.98
     2.5     2.5
   11.32   29.08
Pier Skew, UpSta & Num, DnSta & Num=  ,4746.5, 2 ,4746.5, 2 , 0 , 0 , 0 ,,
     2.5     2.5
   11.58   28.97
     2.5     2.5
   11.68   29.07
Pier Skew, UpSta & Num, DnSta & Num=  ,4771.5, 2 ,4771.5, 2 , 0 , 0 , 0 ,,
     2.5     2.5
   12.09   28.96
     2.5     2.5
   12.19   29.06
Pier Skew, UpSta & Num, DnSta & Num=  ,4794.1, 2 ,4794.1, 2 , 0 , 0 , 0 ,,
     2.5     2.5
   12.06   28.94
     2.5     2.5
   12.16   29.04
Pier Skew, UpSta & Num, DnSta & Num=  ,4817.9, 2 ,4817.9, 2 , 0 , 0 , 0 ,,
     2.5     2.5
   13.16   28.92
     2.5     2.5
   13.26   29.02
Pier Skew, UpSta & Num, DnSta & Num=  ,4841.9, 2 ,4841.9, 2 , 0 , 0 , 0 ,,
     2.5     2.5
   13.65   28.96
     2.5     2.5
   13.75   29.06
Pier Skew, UpSta & Num, DnSta & Num=  ,4865.5, 2 ,4865.5, 2 , 0 , 0 , 0 ,,
     2.5     2.5
   14.13   28.99
     2.5     2.5
   14.23   29.09
Pier Skew, UpSta & Num, DnSta & Num=  ,4889.5, 2 ,4889.5, 2 , 0 , 0 , 0 ,,
     2.5     2.5
   13.95      29
     2.5     2.5
   14.05    29.1
Pier Skew, UpSta & Num, DnSta & Num=  ,4912.3, 2 ,4912.3, 2 , 0 , 0 , 0 ,,
     2.5     2.5
   13.99   29.01
     2.5     2.5
   14.09   29.11
Pier Skew, UpSta & Num, DnSta & Num=  ,4935.5, 2 ,4935.5, 2 , 0 , 0 , 0 ,,
     2.5     2.5
    9.87   28.99
     2.5     2.5
    9.97   29.09
Pier Skew, UpSta & Num, DnSta & Num=  ,4971.2, 2 ,4971.2, 2 , 0 , 0 , 0 ,,
     2.5     2.5
   -3.79   28.97
     2.5     2.5
   -3.69   29.07
Pier Skew, UpSta & Num, DnSta & Num=  ,5012.7, 2 ,5012.7, 2 , 0 , 0 , 0 ,,
     2.5     2.5
   -8.75   28.96
     2.5     2.5
   -8.65   29.06
Pier Skew, UpSta & Num, DnSta & Num=  ,5048.1, 2 ,5048.1, 2 , 0 , 0 , 0 ,,
     2.5     2.5
   13.88   28.95
     2.5     2.5
   13.98   29.05
Abutment Skew #Up #Dn= , 2 , 2
  4389.8 4410.29
   27.89   15.43
  4389.8 4410.29
   27.99   15.53
Abutment Skew #Up #Dn= , 2 , 2
  5053.8 5072.53
   18.61      31
  5053.8 5072.53
   18.71    31.1
BR Coef= 1 , 1 , 0 ,1.25, 0 ,,,.8,0,2,0,
WSPro=,,,, 1 ,,,, 0 ,,,, 0 ,,,,-1 ,-1 ,-1 , 0 , 0 , 0 , 0 , 0
BR U #Sta/Elev= 127
 3339.04    50.8 3522.86    50.3  3749.1    44.5 3848.08    40.3 4012.89    42.8
 4083.59    42.3 4106.36   40.61 4106.46    40.6 4106.57   40.59 4111.87    40.2
 4118.94      39 4140.15    31.8 4147.22    30.7  4151.5   30.48 4203.78    27.8
 4224.99    29.5 4281.55    29.8 4288.62    29.4 4295.69    28.3 4299.43    27.5
 4348.92    26.8 4353.66   30.71 4353.94   30.64 4354.65   30.63 4359.32    30.6
 4377.63   30.45 4389.73   27.95  4389.8   27.93 4389.91   27.91    4390   27.89
 4390.21   27.85 4410.19   15.44 4410.29   15.43 4412.98   15.06 4426.76   13.41
 4436.95   12.87 4437.23   12.86  4448.4    12.3  4460.7   11.67 4472.51   11.56
 4484.43   11.17 4484.53   11.17 4496.55   11.35 4508.21   12.13 4521.36   11.88
  4531.8   11.71  4531.9   11.71 4545.12   11.34 4555.72   11.84 4568.45   12.14
 4579.24   12.36 4579.34   12.36 4590.15   12.27 4603.66   12.27  4614.4   12.07
 4626.99   12.03 4627.48   12.03 4637.17   11.84  4651.1   11.69 4664.46    11.7
 4674.92   11.76 4675.13   11.76 4698.75   12.44 4709.99   12.48 4722.43    12.2
 4722.57    12.2 4735.44   12.53 4746.54   12.59 4758.84   12.66 4771.36   13.13
  4771.5   13.14 4783.45    13.5 4794.12      13 4804.94   14.05 4817.66   14.17
 4817.95   14.17 4829.47   14.37 4841.91   14.68 4853.51   14.82 4865.25   15.16
 4865.53   15.17 4877.97   15.24 4889.57   14.95 4899.96   14.97 4912.05   15.02
 4912.33   15.02 4923.79   14.75 4935.52   11.43 4951.71    4.17 4966.21    1.84
  4970.8   -2.27 4971.23   -2.65 4985.29   -4.21 5002.26   -7.72 5012.66   -7.75
 5023.47   -7.12 5033.79     1.8 5042.28   12.33 5047.79   15.37 5048.22   15.61
  5053.7   18.54  5053.8   18.61 5067.73    27.8 5072.13      31 5072.27      31
 5072.33      31 5072.44   31.01 5072.54   31.01 5107.54   31.61 5107.65   31.61
 5107.75   31.62 5110.43   31.66 5110.93   31.67  5129.7   33.72 5131.36    33.9
 5149.67    35.9 5177.95    40.2 5199.16    41.4 5305.42      42 5418.54    42.4
 5439.75    41.6 5460.96      44 5835.67    45.1 5892.23    45.9  5899.3    46.7
 5906.37    48.3 5913.44    50.4
BR U #Mann= 5
 3339.04     .15  4151.5     .08 4923.79    .045 5042.28    .055  5129.7      .1
BR U Banks=4923.79,5042.28
BR D #Sta/Elev= 127
 3339.04    50.9 3522.86    50.4  3749.1    44.6 3848.08    40.4 4012.89    42.9
 4083.59    42.4 4106.36   40.71 4106.46    40.7 4106.57   40.69 4111.87    40.3
 4118.94    39.1 4140.15    31.9 4147.22    30.8  4151.5   30.58 4203.78    27.9
 4224.99    29.6 4281.55    29.9 4288.62    29.5 4295.69    28.4 4299.43    27.6
 4348.92    26.9 4353.66   30.81 4353.94   30.74 4354.65   30.73 4359.32    30.7
 4377.63   30.55 4389.73   28.05  4389.8   28.03 4389.91   28.01    4390   27.99
 4390.21   27.95 4410.19   15.54 4410.29   15.53 4412.98   15.16 4426.76   13.51
 4436.95   12.97 4437.23   12.96  4448.4    12.4  4460.7   11.77 4472.51   11.66
 4484.43   11.27 4484.53   11.27 4496.55   11.45 4508.21   12.23 4521.36   11.98
  4531.8   11.81  4531.9   11.81 4545.12   11.44 4555.72   11.94 4568.45   12.24
 4579.24   12.46 4579.34   12.46 4590.15   12.37 4603.66   12.37  4614.4   12.17
 4626.99   12.13 4627.48   12.13 4637.17   11.94  4651.1   11.79 4664.46    11.8
 4674.92   11.86 4675.13   11.86 4698.75   12.54 4709.99   12.58 4722.43    12.3
 4722.57    12.3 4735.44   12.63 4746.54   12.69 4758.84   12.76 4771.36   13.23
  4771.5   13.24 4783.45    13.6 4794.12    13.1 4804.94   14.15 4817.66   14.27
 4817.95   14.27 4829.47   14.47 4841.91   14.78 4853.51   14.92 4865.25   15.26
 4865.53   15.27 4877.97   15.34 4889.57   15.05 4899.96   15.07 4912.05   15.12
 4912.33   15.12 4923.79   14.85 4935.52   11.53 4951.71    4.27 4966.21    1.94
  4970.8   -2.17 4971.23   -2.55 4985.29   -4.11 5002.26   -7.62 5012.66   -7.65
 5023.47   -7.02 5033.79     1.9 5042.28   12.43 5047.79   15.47 5048.22   15.71
  5053.7   18.64  5053.8   18.71 5067.73    27.9 5072.13    31.1 5072.27    31.1
 5072.33    31.1 5072.44   31.11 5072.54   31.11 5107.54   31.71 5107.65   31.71
 5107.75   31.72 5110.43   31.76 5110.93   31.77  5129.7   33.82 5131.36      34
 5149.67      36 5177.95    40.3 5199.16    41.5 5305.42    42.1 5418.54    42.5
 5439.75    41.7 5460.96    44.1 5835.67    45.2 5892.23      46  5899.3    46.8
 5906.37    48.4 5913.44    50.5
BR D #Mann= 5
 3339.04     .15  4151.5     .08 4923.79    .045 5042.28    .055  5129.7      .1
BR D Banks=4923.79,5042.28
BC Design=,, 0 ,, 0 ,,,,,,
BC HTab HWMax=50.77

Type RM Length L Ch R = 1 ,119900.0,404.1,404.1,404.1
BEGIN DESCRIPTION:
Downstream Section of Bridge/Culvert/Weir
END DESCRIPTION:
XS GIS Cut Line= 6
      3114276.37     13843040.71      3114510.41     13842390.37
      3115076.42     13842361.66      3115593.24       13842384.
      3115745.48     13842210.76      3115737.12     13841644.44
#Sta/Elev= 30
 3339.04   50.91 3522.86   50.41 3848.08   40.41 4083.59   42.41 4118.94   39.11
 4140.15   31.91  4151.5   30.59 4203.78   27.91 4281.55   29.91 4299.43   27.61
 4348.92   26.91 4353.66   30.82 4377.63   30.56 4390.21   27.96 4410.19   15.55
 4484.43   11.28 4923.79   14.86 4951.71    4.28 4966.21    1.95 4971.23   -2.54
 5012.66   -7.64 5023.47   -7.01 5033.79    1.91 5042.28   12.44 5072.13   31.11
  5129.7   33.83 5199.16   41.51 5835.67   45.21 5892.23   46.01 5913.44   50.51
#Mann= 5 ,-1 , 0
 3339.04     .15       0  4151.5     .08       0 4923.79    .045       0
 5042.28    .055       0  5129.7      .1       0
#XS Ineff= 2 , 0
            4130      32    5105              32
Permanent Ineff=
       F       F
Bank Sta=4923.79,5042.28
XS Rating Curve= 0
Exp/Cntr=.5,.3

Type RM Length L Ch R = 1 ,119495.9,1598.9,828.2,317.1
BEGIN DESCRIPTION:
Cross Section 119495.9
END DESCRIPTION:
XS GIS Cut Line= 6
       3114260.1     13843813.09      3115007.68     13843295.97
      3115704.67     13842638.32      3115817.09     13842492.18
      3115839.58     13842183.03      3115806.14     13841323.67
#Sta/Elev= 30
  3297.5    49.7  3437.5    49.4  3877.5    42.6  4177.5    42.7  4197.5    41.3
  4256.5    18.4  4276.5    14.7  4446.5    11.4  4486.5     6.9  4728.4   11.74
  4876.5    12.8  4936.2     7.8    4939   10.23  4958.6     .17  4968.2   -7.12
  4991.3   -7.21  5024.2   -3.43  5041.4     .85  5067.2   12.58    5091   13.39
  5136.5   22.23  5294.8    22.2  5399.8    29.1  5469.2    30.8  5589.2    40.9
  5849.2      42  5889.2    44.3  6399.2    45.1  6489.2    46.3  6519.2    50.3
#Mann= 5 ,-1 , 0
  3297.5     .15       0  4728.4     .07       0    4939    .045       0
  5067.2     .07       0  5399.8      .1       0
Bank Sta=4939,5067.2
XS Rating Curve= 0
Exp/Cntr=.3,.1