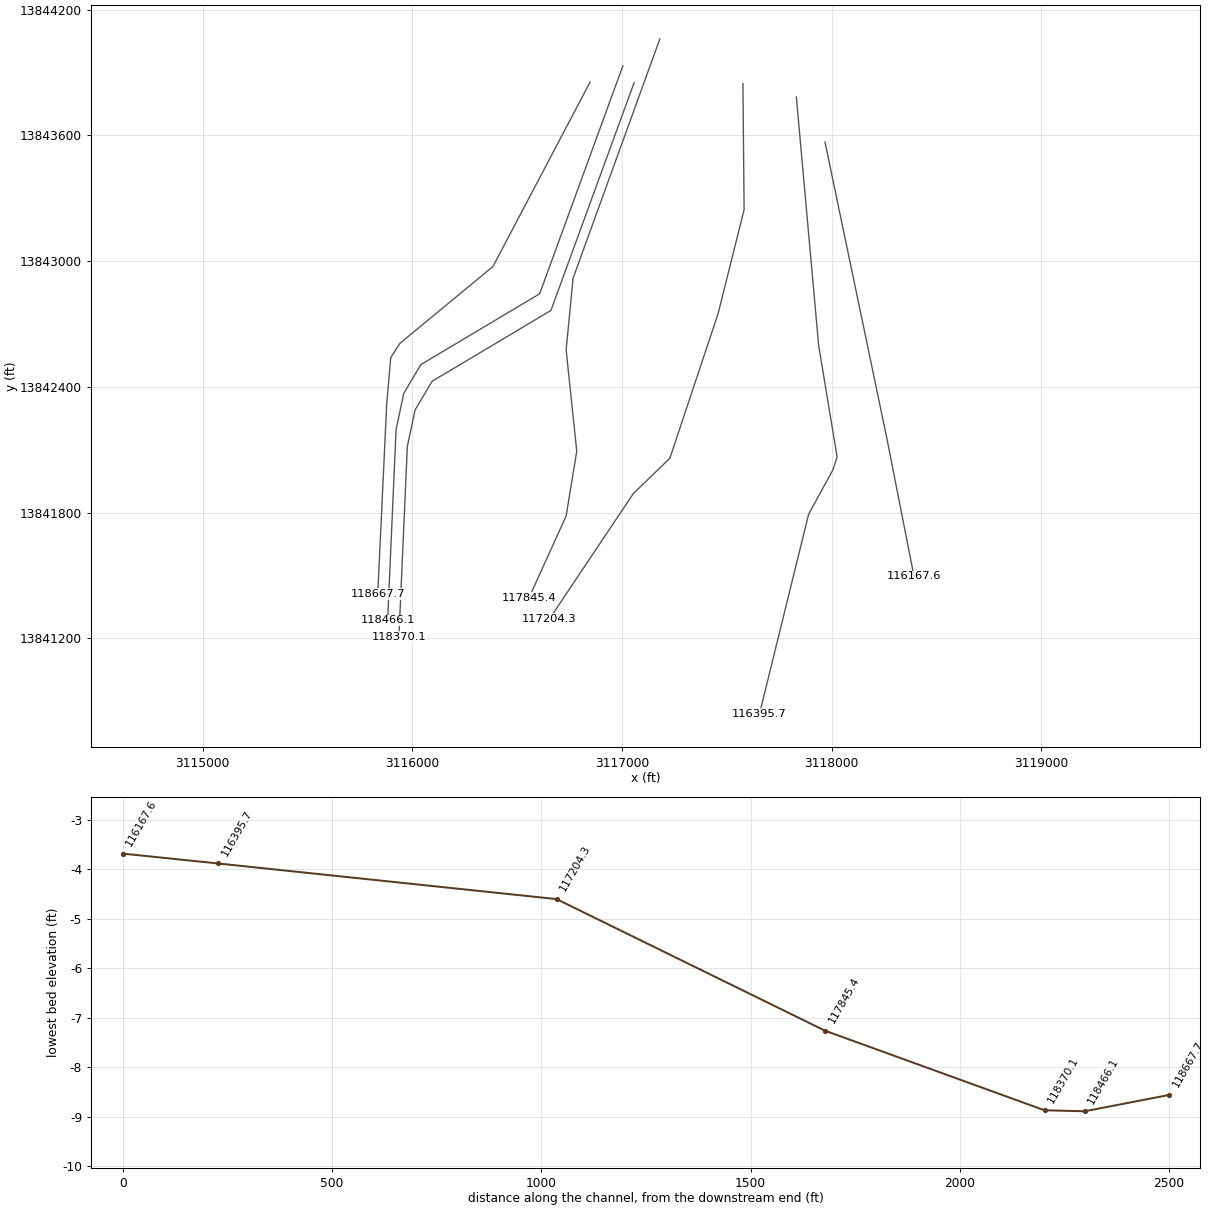
HEC-RAS study W100-00-00.prj: W100-00-00

--- W100-00-00.g01 (geometry) --- (continued)

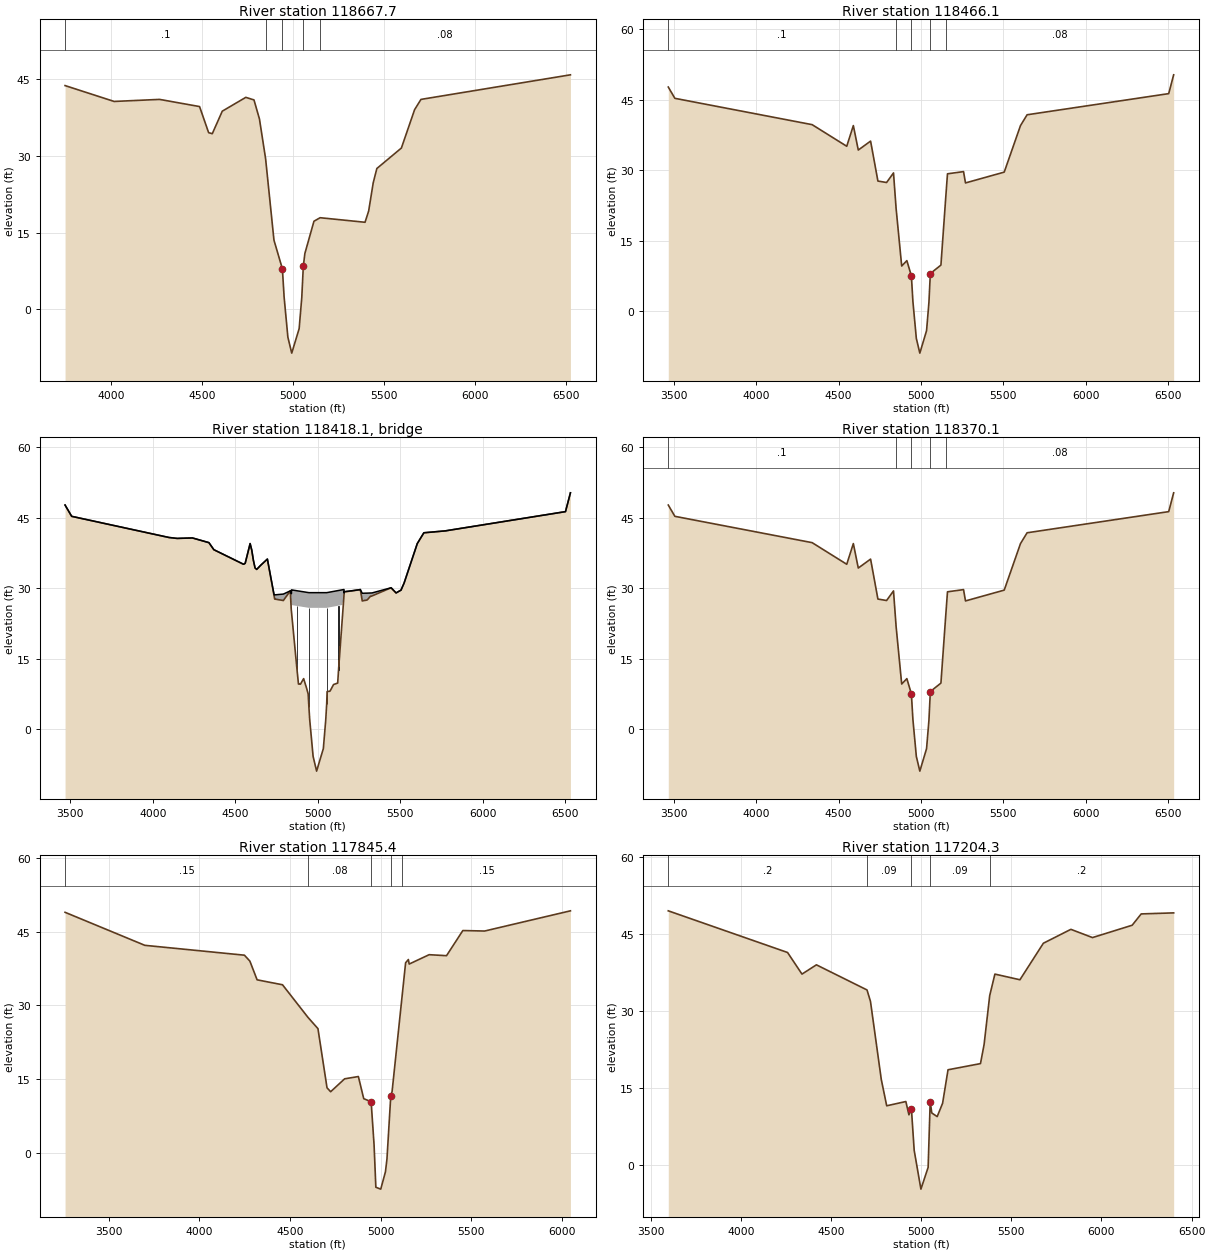
Type RM Length L Ch R = 1 ,118667.7,193.3,201.6,127.4
BEGIN DESCRIPTION:
Cross Section 118667.7 - Interpolated
END DESCRIPTION:
XS GIS Cut Line= 6
      3116847.38     13843854.09       3116384.1     13842974.18
      3115940.24     13842607.51      3115896.82     13842539.97
      3115877.52     13842318.04      3115834.77     13841411.76
#Sta/Elev= 30
  3746.2    43.7  4016.2    40.6  4266.2      41  4486.2    39.6  4536.2    34.5
  4556.2    34.3  4611.2    38.7  4740.6    41.4  4785.6    40.9  4815.6    37.2
  4849.4   29.47  4895.6    13.5    4942    7.89  4951.4     2.4  4972.1   -5.43
  4993.3   -8.56  5034.1   -3.78  5048.6     2.3    5057    8.37  5065.6    10.9
  5115.6    17.2  5149.4   17.89  5396.6      17  5416.6    19.2  5441.6    24.7
  5461.6    27.5  5596.6    31.5  5669.4      39  5704.4      41  6526.7    45.8
#Mann= 5 ,-1 , 0
  3746.2      .1       0  4849.4     .12       0    4942    .045       0
    5057    .125       0  5149.4     .08       0
Bank Sta=4942,5057
XS Rating Curve= 0
Exp/Cntr=.5,.3

Type RM Length L Ch R = 1 ,118466.1,96,96,96
BEGIN DESCRIPTION:
Upstream Section of Bridge/Culvert/Weir
END DESCRIPTION:
XS GIS Cut Line= 6
      3117004.07     13843932.14      3116607.02     13842844.15
      3116040.36     13842506.24      3115959.02     13842369.19
       3115922.2     13842196.15      3115881.97     13841286.51
#Sta/Elev= 30
  3467.5   47.72  3507.5   45.32    4340   39.72    4550   35.12    4590   39.52
    4620   34.32  4694.7   36.22    4739   27.72  4791.7   27.41  4833.6   29.45
  4849.4   21.88  4883.3    9.64  4914.6   10.79    4942    7.56  4951.4    2.07
  4972.1   -5.76  4993.3   -8.89  5034.1   -4.11  5048.6    1.97    5057    8.04
  5121.2    9.84  5149.4    23.7    5161   29.26  5258.5   29.73  5270.2   27.32
  5505.2   29.62  5603.9   39.52  5643.9   41.82  6502.9   46.32  6532.9   50.32
#Mann= 5 ,-1 , 0
  3467.5      .1       0  4849.4     .12       0    4942    .045       0
    5057    .125       0  5149.4     .08       0
#XS Ineff= 2 , 0
            4830    28.7    5170            28.9
Permanent Ineff=
       F       F
Bank Sta=4942,5057
XS Rating Curve= 0
Exp/Cntr=.5,.3

Type RM Length L Ch R = 3 ,118418.1,,,
BEGIN DESCRIPTION:
MEMORIAL DRIVE
Structure ID: WOO-42
END DESCRIPTION:
Bridge Culvert--1,0,-1,-1, 0
Deck Dist Width WeirC Skew NumUp NumDn MinLoCord MaxHiCord MaxSubmerge Is_Ogee
10,76,2.6,0, 45, 45, , , .95, 0, 1,1,,
  3467.5  3507.5  4097.5  4147.5    4240    4340    4370    4550    4560    4590
    4600    4610    4620    4630  4654.7  4694.7  4735.7    4739  4791.7  4833.6
  4839.4  4840.6  4840.7 4840.81  4840.9  4946.5  5054.6  5149.4  5159.5    5160
    5161  5258.5  5270.2  5300.2  5320.2  5329.4  5445.2  5475.2  5505.2  5523.9
  5603.9  5643.9  5772.9  6502.9  6532.9
    47.7    45.3    40.8    40.6    40.7    39.7    38.2    35.1    35.3    39.5
    38.1   35.91   34.31   34.01   34.91   36.21   28.58   28.59   28.76   29.44
   28.85   28.85   29.65   29.65   29.65   29.06   29.06   29.67   29.73   29.02
   29.25   29.72   28.93   28.96   28.99      29    30.1      29    29.6    31.1
    39.5    41.8    42.2    46.3    50.3
    47.7    45.3    40.8    40.6    40.7    39.7    38.2    35.1    35.3    39.5
    38.1    35.9    34.3      34    34.9    36.2   28.33    27.7   27.39   29.43
   25.53   25.09   25.05   25.01   26.42   25.83   25.83   26.44   28.52   28.76
   29.24   29.71    27.3    27.5    28.3   28.36    30.1      29    29.6    31.1
    39.5    41.8    42.2    46.3    50.3
  3467.5  3507.5  4097.5  4147.5    4240    4340    4370    4550    4560    4590
    4600    4610    4620    4630  4654.7  4694.7  4735.7    4739  4791.7  4833.6
  4839.4  4840.6  4840.7 4840.81  4840.9  4946.5  5054.6  5149.4  5159.5    5160
    5161  5258.5  5270.2  5300.2  5320.2  5329.4  5445.2  5475.2  5505.2  5523.9
  5603.9  5643.9  5772.9  6502.9  6532.9
   47.71   45.31   40.81   40.61   40.71   39.71   38.21   35.11   35.31   39.51
   38.11   35.91   34.31   34.01   34.91   36.21   28.58   28.59   28.76   29.44
   28.85   28.85   29.65   29.65   29.65   29.06   29.06   29.67   29.73   29.02
   29.25   29.72   28.93   28.96   28.99      29   30.11   29.01   29.61   31.11
   39.51   41.81   42.21   46.31   50.31
   47.71   45.31   40.81   40.61   40.71   39.71   38.21   35.11   35.31   39.51
   38.11   35.91   34.31   34.01   34.91   36.21   28.34   27.71    27.4   29.44
   25.54    25.1   25.06   25.02   26.43   25.84   25.84   26.45   28.53   28.77
   29.25   29.72   27.31   27.51   28.31   28.37   30.11   29.01   29.61   31.11
   39.51   41.81   42.21   46.31   50.31
Pier Skew, UpSta & Num, DnSta & Num=  ,4874.7, 2 ,4874.7, 2 , 0 , 0 , 0 ,,
       2       2
   11.24   27.24
       2       2
   11.25   27.25
Pier Skew, UpSta & Num, DnSta & Num=  ,4946.6, 2 ,4946.6, 2 , 0 , 0 , 0 ,,
       2       2
    3.18   26.84
       2       2
    3.19   26.85
Pier Skew, UpSta & Num, DnSta & Num=  ,5054.5, 2 ,5054.5, 2 , 0 , 0 , 0 ,,
       2       2
    3.82   26.84
       2       2
    3.83   26.85
Pier Skew, UpSta & Num, DnSta & Num=  ,5126.5, 2 ,5126.5, 2 , 0 , 0 , 0 ,,
       2       2
   11.16    27.3
       2       2
   11.17   27.31
Abutment Skew #Up #Dn= , 2 , 2
  4840.7  4883.4
   26.42    9.62
  4840.7  4883.4
   26.43    9.63
Abutment Skew #Up #Dn= , 2 , 2
  5121.3 5159.59
    9.87   28.47
  5121.3 5159.59
    9.88   28.48
BR Coef= 1 , 1 , 0 ,1.25, 0 ,,,.8,0,2,0,
WSPro=,,,, 1 ,,,, 0 ,,,, 0 ,,,,-1 ,-1 ,-1 , 0 , 0 , 0 , 0 , 0
BR U #Sta/Elev= 82
  3467.5    47.7  3507.5    45.3  4097.5    40.8  4147.5    40.6    4240    40.7
    4340    39.7    4370    38.2    4550    35.1    4560    35.3    4590    39.5
    4600    38.1  4605.4   36.91    4610    35.9    4620    34.3    4630      34
  4654.7    34.9  4694.7    36.2  4735.7   28.33 4737.09   28.07  4737.2   28.05
 4737.31   28.02    4739    27.7  4739.1    27.7  4784.2   27.43  4791.7   27.39
  4833.6   29.43  4839.4   25.53  4840.6   25.09  4840.7   25.05 4840.81   25.01
  4840.9   24.98  4849.4   21.86  4874.7   12.58  4883.3    9.62  4883.4    9.62
  4895.3    9.59  4914.6   10.77  4932.1    8.79    4942    7.54  4946.5     4.8
  4946.6    4.74  4951.4    2.05  4972.1   -5.78  4993.3   -8.91  5016.2   -6.21
  5034.1   -4.13  5048.6    1.95  5054.5    5.41  5054.6    5.51    5057    8.02
  5074.5     8.1  5096.3    9.52  5121.2    9.82  5121.3    9.87  5126.5   12.71
  5149.4   23.68 5159.39   28.47  5159.5   28.52  5159.6   28.57    5160   28.76
    5161   29.24  5195.2   29.38  5214.2   29.46  5255.8   29.69 5255.89    29.7
    5256    29.7 5256.11    29.7  5258.5   29.71  5270.2    27.3  5300.2    27.5
  5320.2    28.3  5325.2    28.3  5329.4   28.36  5445.2    30.1  5475.2      29
  5505.2    29.6  5523.9    31.1  5603.9    39.5  5643.9    41.8  5772.9    42.2
  6502.9    46.3  6532.9    50.3
BR U #Mann= 5
  3467.5      .1  4849.4     .12    4942    .045    5057    .125  5149.4     .08
BR U Banks=4942,5057
BR D #Sta/Elev= 82
  3467.5   47.71  3507.5   45.31  4097.5   40.81  4147.5   40.61    4240   40.71
    4340   39.71    4370   38.21    4550   35.11    4560   35.31    4590   39.51
    4600   38.11  4605.4   36.92    4610   35.91    4620   34.31    4630   34.01
  4654.7   34.91  4694.7   36.21  4735.7   28.34 4737.09   28.08  4737.2   28.06
 4737.31   28.03    4739   27.71  4739.1   27.71  4784.2   27.44  4791.7    27.4
  4833.6   29.44  4839.4   25.54  4840.6    25.1  4840.7   25.06 4840.81   25.02
  4840.9   24.99  4849.4   21.87  4874.7   12.59  4883.3    9.63  4883.4    9.63
  4895.3     9.6  4914.6   10.78  4932.1     8.8    4942    7.55  4946.5    4.81
  4946.6    4.75  4951.4    2.06  4972.1   -5.77  4993.3    -8.9  5016.2    -6.2
  5034.1   -4.12  5048.6    1.96  5054.5    5.42  5054.6    5.52    5057    8.03
  5074.5    8.11  5096.3    9.53  5121.2    9.83  5121.3    9.88  5126.5   12.72
  5149.4   23.69 5159.39   28.48  5159.5   28.53  5159.6   28.58    5160   28.77
    5161   29.25  5195.2   29.39  5214.2   29.47  5255.8    29.7 5255.89   29.71
    5256   29.71 5256.11   29.71  5258.5   29.72  5270.2   27.31  5300.2   27.51
  5320.2   28.31  5325.2   28.31  5329.4   28.37  5445.2   30.11  5475.2   29.01
  5505.2   29.61  5523.9   31.11  5603.9   39.51  5643.9   41.81  5772.9   42.21
  6502.9   46.31  6532.9   50.31
BR D #Mann= 5
  3467.5      .1  4849.4     .12    4942    .045    5057    .125  5149.4     .08
BR D Banks=4942,5057
BC Design=,, 0 ,, 0 ,,,,,,
BC HTab HWMax=50.32

Type RM Length L Ch R = 1 ,118370.1,524.7,524.7,524.7
BEGIN DESCRIPTION:
Downstream Section of Bridge/Culvert/Weir
END DESCRIPTION:
XS GIS Cut Line= 6
      3117057.87     13843852.64      3116660.82     13842764.65
      3116094.16     13842426.74      3116012.82     13842289.69
        3115976.     13842116.65      3115935.77       13841207.
#Sta/Elev= 30
  3467.5   47.74  3507.5   45.34    4340   39.74    4550   35.14    4590   39.54
    4620   34.34  4694.7   36.24    4739   27.74  4791.7   27.43  4833.6   29.47
  4849.4    21.9  4883.3    9.66  4914.6   10.81    4942    7.58  4951.4    2.09
  4972.1   -5.74  4993.3   -8.87  5034.1   -4.09  5048.6    1.99    5057    8.06
  5121.2    9.86  5149.4   23.72    5161   29.28  5258.5   29.75  5270.2   27.34
  5505.2   29.64  5603.9   39.54  5643.9   41.84  6502.9   46.34  6532.9   50.34
#Mann= 5 ,-1 , 0
  3467.5      .1       0  4849.4     .12       0    4942    .045       0
    5057    .125       0  5149.4     .08       0
#XS Ineff= 2 , 0
            4830    28.7    5170            28.9
Permanent Ineff=
       F       F
Bank Sta=4942,5057
XS Rating Curve= 0
Exp/Cntr=.5,.3

Type RM Length L Ch R = 1 ,117845.4,773.4,641.1,563.1
BEGIN DESCRIPTION:
Cross Section 117845.4
END DESCRIPTION:
XS GIS Cut Line= 6
       3117180.2       13844060.      3116766.47     13842918.54
       3116733.3     13842576.49      3116783.89      13842093.1
       3116733.3     13841783.95      3116555.72      13841392.3
#Sta/Elev= 30
  3260.3    48.9  3700.3    42.2  4249.5    40.2  4279.5      39  4319.5    35.2
  4459.5    34.2  4599.4   27.61    4655    25.3    4705    13.3    4725    12.5
  4802.2   15.12  4877.9   15.58  4907.5   11.09  4948.3   10.47  4964.4    1.76
  4974.3   -6.88  5001.3   -7.26  5027.3   -3.73  5035.6   -1.13  5056.7    11.7
  5063.9   12.56  5120.5   32.39  5138.4   38.66  5153.7   39.32  5158.1    38.4
  5268.1    40.3  5364.1    40.1  5454.1    45.2  5574.1    45.1  6047.4    49.2
#Mann= 5 ,-1 , 0
  3260.3     .15       0  4599.4     .08       0  4948.3    .045       0
  5056.7    .085       0  5120.5     .15       0
Bank Sta=4948.3,5056.7
XS Rating Curve= 0
Exp/Cntr=.3,.1

Type RM Length L Ch R = 1 ,117204.3,719.6,808.6,769.7
BEGIN DESCRIPTION:
Cross Section 117204.3
END DESCRIPTION:
XS GIS Cut Line= 6
      3117576.44     13843846.82      3117582.06     13843245.38
       3117458.4     13842750.74      3117227.94     13842059.37
      3117053.69     13841890.74       3116653.5     13841292.22
#Sta/Elev= 30
  3597.6    49.5  4259.1    41.4  4339.1    37.2  4419.1      39  4699.6   34.12
  4718.9    31.9  4778.9    16.7  4808.9    11.6    4915   12.43  4932.1    9.85
  4945.8   11.06  4961.3    2.94  4998.6    -4.6  5038.6    -.38  5050.1   12.42
  5058.9    10.2  5088.9     9.5  5118.9    12.1  5148.9    18.6  5328.9    19.8
  5348.9    23.5  5380.1   33.02  5408.9    37.2  5547.7    36.1  5677.7    43.2
  5830.2    45.9  5950.2    44.3  6170.2    46.7  6220.2    48.9  6400.2    49.1
#Mann= 5 ,-1 , 0
  3597.6      .2       0  4699.6     .09       0  4945.8    .045       0
  5050.1     .09       0  5380.1      .2       0
Bank Sta=4945.8,5050.1
XS Rating Curve= 0
Exp/Cntr=.3,.1

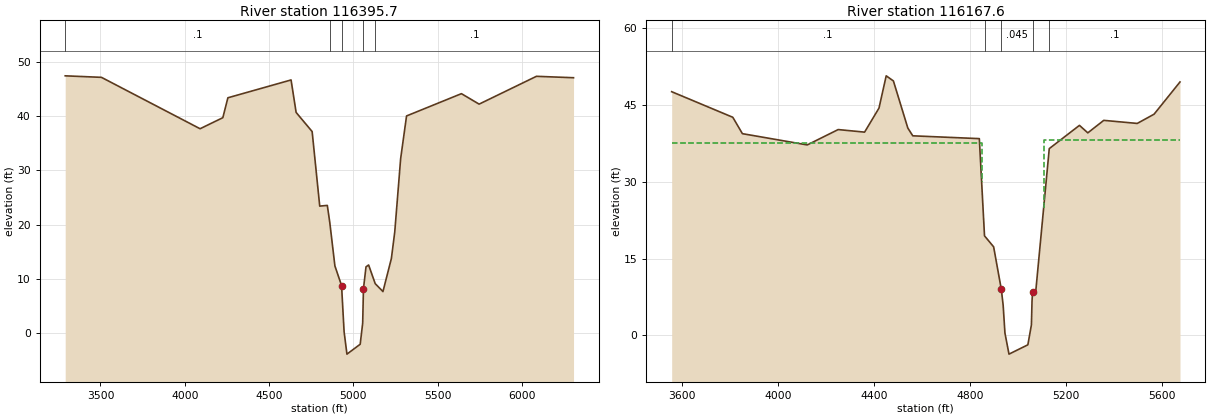
Type RM Length L Ch R = 1 ,116395.7,205.9,228.1,325.6
BEGIN DESCRIPTION:
Cross Section 116395.7 - Interpolated
END DESCRIPTION:
XS GIS Cut Line= 6
      3117831.28     13843782.77      3117937.59     13842597.86
       3118025.8     13842065.58      3118005.29     13842003.35
      3117889.88      13841792.5      3117655.69     13840840.85
#Sta/Elev= 30
  3290.7   47.45  3505.7   47.17  4090.7   37.69  4225.7   39.73  4255.7    43.4
  4630.4   46.69  4660.4    40.7  4755.4   37.17  4800.4   23.42  4845.4   23.55
  4859.9   20.44  4890.4   12.39  4929.9    8.77  4944.9     .26  4961.8   -3.88
  5040.4   -2.06  5055.2    1.85  5059.8     8.2  5074.9   12.22  5090.4   12.56
  5129.5    9.12  5175.4    7.66  5225.4   13.76  5245.4   18.66  5280.4   32.19
  5315.4   40.05  5640.8   44.16  5745.8   42.23  6085.8   47.36  6305.8    47.1
#Mann= 5 ,-1 , 0
  3290.7      .1       0  4859.9     .12       0  4929.9    .045       0
  5059.8    .125       0  5129.5      .1       0
Bank Sta=4929.9,5059.8
XS Rating Curve= 0
Exp/Cntr=.5,.3

Type RM Length L Ch R = 1 ,116167.6,91.4,91.4,91.4
BEGIN DESCRIPTION:
Upstream Section of Bridge/Culvert/Weir
END DESCRIPTION:
XS GIS Cut Line= 3
      3117967.73     13843568.63      3118262.44     13842156.53
      3118392.53     13841495.33
#Sta/Elev= 30
  3557.4   47.59  3811.9   42.59  3851.9   39.39  4121.9   37.19  4250.6   40.19
  4360.6   39.69  4420.6   44.39  4450.6   50.69  4480.6   49.69  4540.6   40.49
  4561.2   38.97  4838.3   38.42  4859.9   19.43  4897.9   17.28  4929.9    8.97
  4937.6    5.83  4944.9     .46  4961.8   -3.68  5040.4   -1.86  5055.2    2.05
  5057.7    6.68  5059.9     8.4  5072.7    8.31  5129.5   36.47  5255.2   41.01
    5290   39.55  5356.4   41.99  5495.8   41.39  5565.8   43.19  5673.8   49.49
#Mann= 5 ,-1 , 0
  3557.4      .1       0  4859.9     .12       0  4929.9    .045       0
  5059.9    .125       0  5129.5      .1       0
#XS Ineff= 2 , 0
            4848    37.5    5106            38.2
Permanent Ineff=
       F       F
Bank Sta=4929.9,5059.9
XS Rating Curve= 0
Exp/Cntr=.5,.3