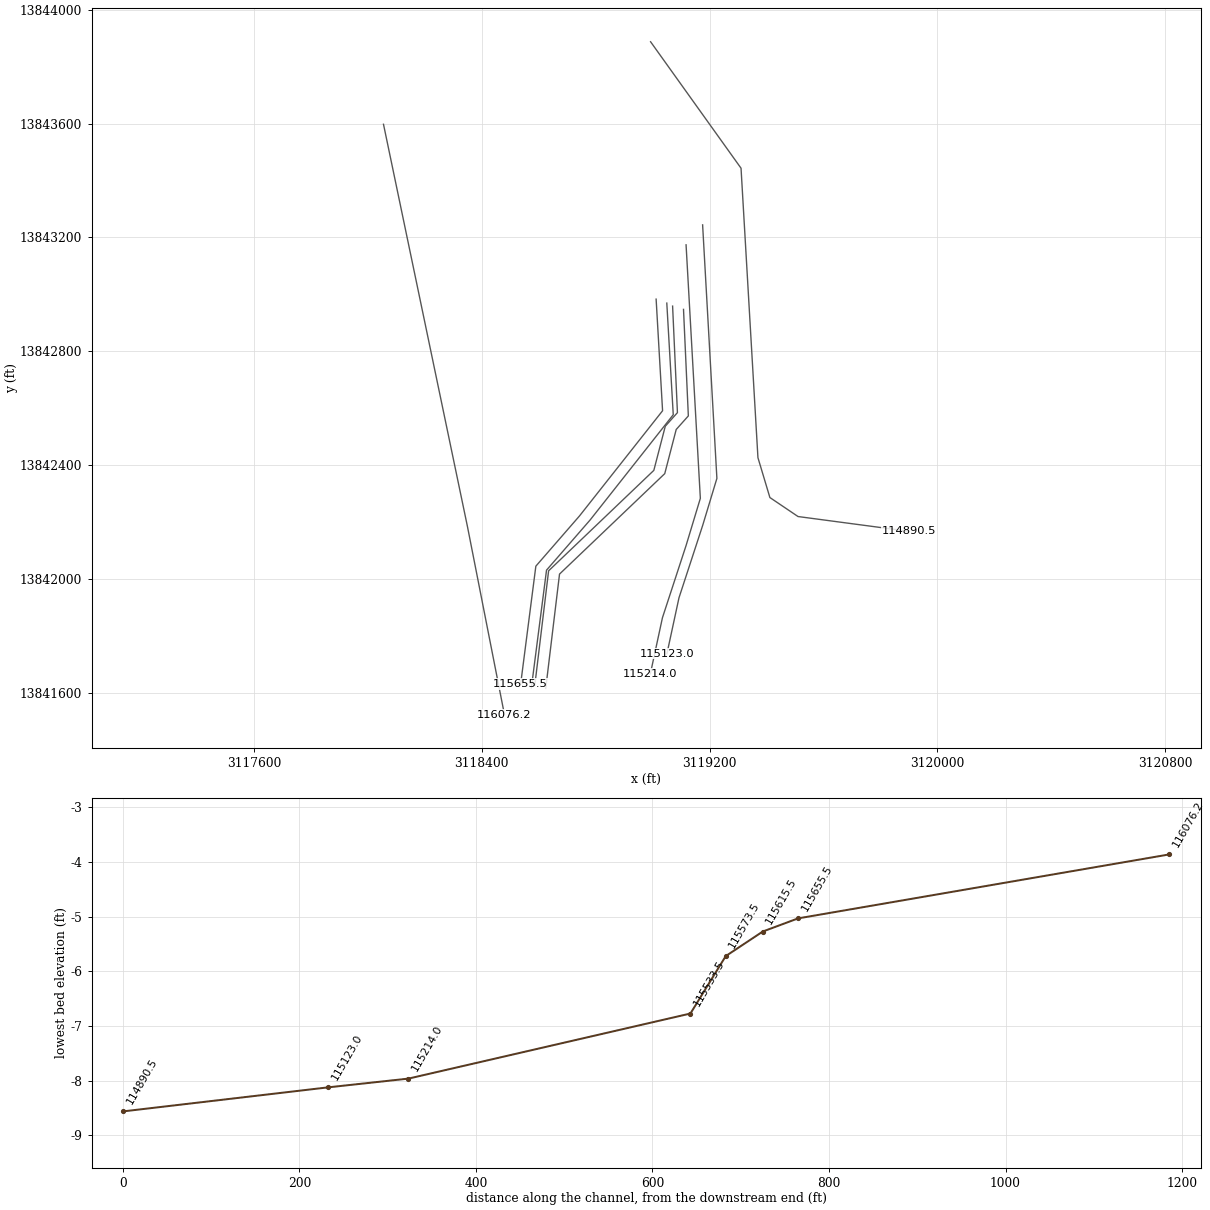
HEC-RAS study W100-00-00.prj: W100-00-00

--- W100-00-00.g01 (geometry) --- (continued)

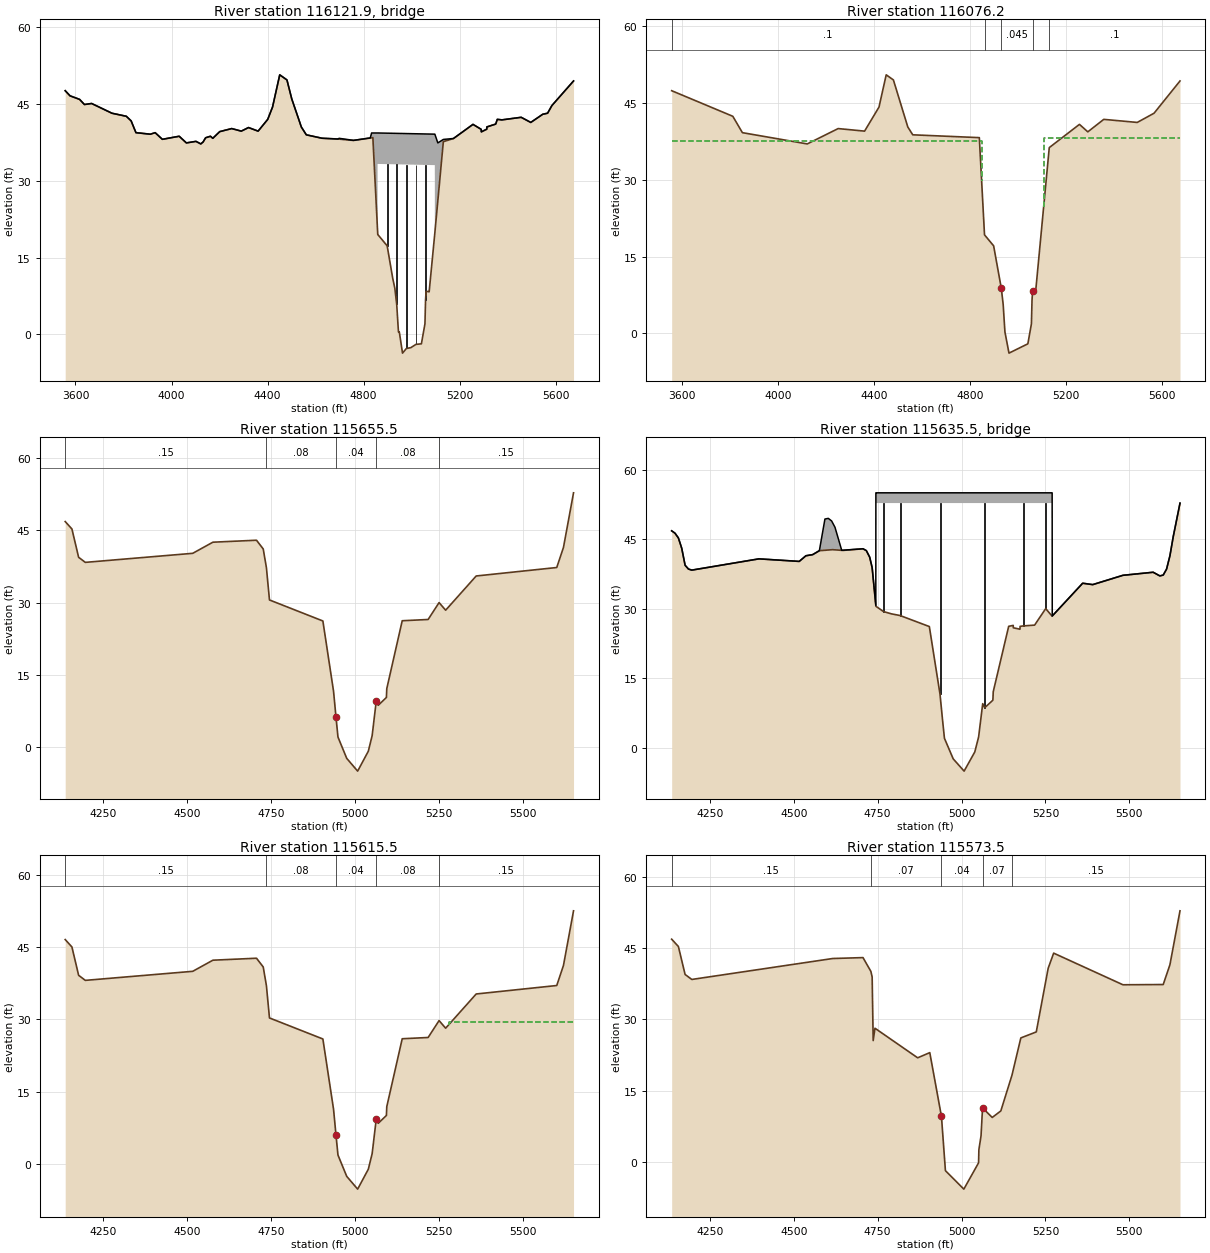
Type RM Length L Ch R = 3 ,116121.9,,,
BEGIN DESCRIPTION:
SABINE AVENUE
Structure ID: W00-41
END DESCRIPTION:
Bridge Culvert--1,0,-1,-1, 0
Deck Dist Width WeirC Skew NumUp NumDn MinLoCord MaxHiCord MaxSubmerge Is_Ogee
10,71.4,2.6,0, 60, 60, , , .95, 0, 1,1,,
  3557.4  3577.4  3617.4  3637.4  3667.4  3751.9  3811.9  3831.9  3851.9  3911.9
  3931.9  3961.9  4031.9  4061.9  4101.9  4121.9  4131.9  4141.9  4161.9  4171.9
  4200.6  4250.6  4290.6  4320.6  4360.6  4400.6  4420.6  4450.6  4480.6  4500.6
  4540.6  4561.2  4626.7  4693.4  4697.5  4757.5  4827.5 4832.99  4838.3 4858.01
  4858.1 5096.29  5096.4  5108.8  5131.8  5173.8  5255.2  5289.4    5290  5312.5
  5312.9  5349.8  5356.4  5375.8  5455.8  5495.8  5545.8  5565.8  5583.8  5673.8
    47.6    46.6    45.9    44.9    45.1    43.2    42.6    41.7    39.4    39.1
    39.4    38.1    38.7    37.4    37.7    37.2    37.6    38.4    38.7    38.3
    39.6    40.2    39.7    40.4    39.7      42    44.4    50.7    49.7      46
    40.5   38.98   38.31   38.16    38.3    37.9   38.37   39.34   39.34   39.34
   39.34   39.11   39.11    37.4   38.08   38.26   41.02   40.05   39.56   40.08
   40.52   41.08      42    41.9    42.4    41.4      43    43.2    44.7    49.5
    47.6    46.6    45.9    44.9    45.1    43.2    42.6    41.7    39.4    39.1
    39.4    38.1    38.7    37.4    37.7    37.2    37.6    38.4    38.7    38.3
    39.6    40.2    39.7    40.4    39.7      42    44.4    50.7    49.7      46
    40.5   38.98   38.31   38.16   38.14   37.88   38.36   38.39   38.43   20.15
   33.29   33.06   19.82   26.06   37.64   38.25   41.02   40.05   39.56   40.08
   40.52   41.08      42    41.9    42.4    41.4      43    43.2    44.7    49.5
  3557.4  3577.4  3617.4  3637.4  3667.4  3751.9  3811.9  3831.9  3851.9  3911.9
  3931.9  3961.9  4031.9  4061.9  4101.9  4121.9  4131.9  4141.9  4161.9  4171.9
  4200.6  4250.6  4290.6  4320.6  4360.6  4400.6  4420.6  4450.6  4480.6  4500.6
  4540.6  4561.2  4626.7  4693.4  4697.5  4757.5  4827.5 4832.99  4838.3 4858.01
  4858.1 5096.29  5096.4  5108.8  5131.8  5173.8  5255.2  5289.4    5290  5312.5
  5312.9  5349.8  5356.4  5375.8  5455.8  5495.8  5545.8  5565.8  5583.8  5673.8
    47.6    46.6    45.9    44.9    45.1    43.2    42.6    41.7    39.4    39.1
    39.4    38.1    38.7    37.4    37.7    37.2    37.6    38.4    38.7    38.3
    39.6    40.2    39.7    40.4    39.7      42    44.4    50.7    49.7      46
    40.5   38.98   38.31   38.16    38.3    37.9   38.37   39.34   39.34   39.34
   39.34   39.11   39.11    37.4   38.08   38.26   41.02   40.05   39.56   40.08
   40.52   41.08      42    41.9    42.4    41.4      43    43.2    44.7    49.5
   47.44   46.44   45.74   44.74   44.94   43.04   42.44   41.54   39.24   38.94
   39.24   37.94   38.54   37.24   37.54   37.04   37.44   38.24   38.54   38.14
   39.44   40.04   39.54   40.24   39.54   41.84   44.24   50.54   49.54   45.84
   40.34   38.82   38.15      38   37.98   37.72    38.2   38.23   38.27   19.99
   33.13    32.9   19.66    25.9   37.48   38.09   40.86   39.89    39.4   39.92
   40.36   40.92   41.84   41.74   42.24   41.24   42.84   43.04   44.54   49.34
Pier Skew, UpSta & Num, DnSta & Num=  ,4898, 2 ,4898, 2 , 0 , 0 , 0 ,,
     2.9     2.9
   15.86   34.25
     2.9     2.9
    15.7   34.09
Pier Skew, UpSta & Num, DnSta & Num=  ,4937.6, 2 ,4937.6, 2 , 0 , 0 , 0 ,,
     2.9     2.9
    3.77   34.22
     2.9     2.9
    3.61   34.06
Pier Skew, UpSta & Num, DnSta & Num=  ,4977.9, 2 ,4977.9, 2 , 0 , 0 , 0 ,,
     2.9     2.9
   -3.84   34.18
     2.9     2.9
      -4   34.02
Pier Skew, UpSta & Num, DnSta & Num=  ,5017.8, 2 ,5017.8, 2 , 0 , 0 , 0 ,,
     2.9     2.9
      -3   34.14
     2.9     2.9
   -3.16   33.98
Pier Skew, UpSta & Num, DnSta & Num=  ,5057.7, 2 ,5057.7, 2 , 0 , 0 , 0 ,,
     2.9     2.9
       3    34.1
     2.9     2.9
    2.84   33.94
Abutment Skew #Up #Dn= , 2 , 2
  4857.9  4921.1
   33.29   10.93
  4857.9  4921.1
   33.13   10.77
Abutment Skew #Up #Dn= , 2 , 2
  5072.7 5096.49
    8.32   33.06
  5072.7 5096.49
    8.16    32.9
BR Coef= 1 , 1 , 0 ,1.25, 0 ,,,.8,0,2,0,
WSPro=,,,, 1 ,,,, 0 ,,,, 0 ,,,,-1 ,-1 ,-1 , 0 , 0 , 0 , 0 , 0
BR U #Sta/Elev= 94
  3557.4    47.6  3577.4    46.6  3617.4    45.9  3637.4    44.9  3667.4    45.1
  3751.9    43.2  3811.9    42.6  3831.9    41.7  3851.9    39.4  3911.9    39.1
  3931.9    39.4  3961.9    38.1  4031.9    38.7  4061.9    37.4  4101.9    37.7
  4121.9    37.2  4131.9    37.6  4141.9    38.4  4161.9    38.7  4171.9    38.3
  4200.6    39.6  4250.6    40.2  4290.6    39.7  4320.6    40.4  4360.6    39.7
  4400.6      42  4420.6    44.4  4450.6    50.7  4480.6    49.7  4500.6      46
  4540.6    40.5  4561.2   38.98  4626.7   38.31  4693.4   38.16  4697.5   38.14
  4757.5   37.88  4787.5   38.08  4807.5   38.22  4827.5   38.36 4832.99   38.39
  4833.1   38.39 4833.21    38.4  4838.3   38.43  4857.9   20.25 4858.01   20.15
  4858.1   20.07  4858.7   19.51  4859.9   19.44  4871.5   18.79  4897.9   17.29
    4921   10.95  4921.1   10.93  4929.9    8.98  4937.6    5.84  4944.9     .47
  4948.4     .47  4961.8   -3.67  4977.9   -2.76    4996   -2.61  4996.1   -2.61
  5017.8   -1.96  5040.4   -1.85  5055.2    2.06  5057.7    6.69  5059.9    8.41
  5072.6    8.32  5072.7    8.32 5095.79   19.52  5095.9   19.57    5096   19.62
 5096.21   19.73 5096.29   19.77  5096.4   19.82  5096.5   19.87  5108.8   26.06
  5128.8   36.13  5129.5   36.48  5131.8   37.64  5173.8   38.25  5185.7   38.65
  5255.2   41.02  5289.4   40.05    5290   39.56  5312.5   40.08  5312.9   40.52
  5349.8   41.08  5356.4      42  5375.8    41.9  5455.8    42.4  5495.8    41.4
  5545.8      43  5565.8    43.2  5583.8    44.7  5673.8    49.5
BR U #Mann= 5
  3557.4      .1  4859.9     .12  4929.9    .045  5059.9    .125  5129.5      .1
BR U Banks=4929.9,5059.9
BR D #Sta/Elev= 94
  3557.4   47.44  3577.4   46.44  3617.4   45.74  3637.4   44.74  3667.4   44.94
  3751.9   43.04  3811.9   42.44  3831.9   41.54  3851.9   39.24  3911.9   38.94
  3931.9   39.24  3961.9   37.94  4031.9   38.54  4061.9   37.24  4101.9   37.54
  4121.9   37.04  4131.9   37.44  4141.9   38.24  4161.9   38.54  4171.9   38.14
  4200.6   39.44  4250.6   40.04  4290.6   39.54  4320.6   40.24  4360.6   39.54
  4400.6   41.84  4420.6   44.24  4450.6   50.54  4480.6   49.54  4500.6   45.84
  4540.6   40.34  4561.2   38.82  4626.7   38.15  4693.4      38  4697.5   37.98
  4757.5   37.72  4787.5   37.92  4807.5   38.06  4827.5    38.2 4832.99   38.23
  4833.1   38.23 4833.21   38.24  4838.3   38.27  4857.9   20.09 4858.01   19.99
  4858.1   19.91  4858.7   19.35  4859.9   19.28  4871.5   18.63  4897.9   17.13
    4921   10.79  4921.1   10.77  4929.9    8.82  4937.6    5.68  4944.9     .31
  4948.4     .31  4961.8   -3.83  4977.9   -2.92    4996   -2.77  4996.1   -2.77
  5017.8   -2.12  5040.4   -2.01  5055.2     1.9  5057.7    6.53  5059.9    8.25
  5072.6    8.16  5072.7    8.16 5095.79   19.36  5095.9   19.41    5096   19.46
 5096.21   19.57 5096.29   19.61  5096.4   19.66  5096.5   19.71  5108.8    25.9
  5128.8   35.97  5129.5   36.32  5131.8   37.48  5173.8   38.09  5185.7   38.49
  5255.2   40.86  5289.4   39.89    5290    39.4  5312.5   39.92  5312.9   40.36
  5349.8   40.92  5356.4   41.84  5375.8   41.74  5455.8   42.24  5495.8   41.24
  5545.8   42.84  5565.8   43.04  5583.8   44.54  5673.8   49.34
BR D #Mann= 5
  3557.4      .1  4859.9     .12  4929.9    .045  5059.9    .125  5129.5      .1
BR D Banks=4929.9,5059.9
BC Design=,, 0 ,, 0 ,,,,,,
BC HTab HWMax=50.69

Type RM Length L Ch R = 1 ,116076.2,420.7,420.7,420.7
BEGIN DESCRIPTION:
Downstream Section of Bridge/Culvert/Weir
END DESCRIPTION:
XS GIS Cut Line= 3
      3118054.53     13843597.27      3118349.24     13842185.17
      3118479.33     13841523.97
#Sta/Elev= 30
  3557.4   47.41  3811.9   42.41  3851.9   39.21  4121.9   37.01  4250.6   40.01
  4360.6   39.51  4420.6   44.21  4450.6   50.51  4480.6   49.51  4540.6   40.31
  4561.2   38.79  4838.3   38.24  4859.9   19.25  4897.9    17.1  4929.9    8.79
  4937.6    5.65  4944.9     .28  4961.8   -3.86  5040.4   -2.04  5055.2    1.87
  5057.7     6.5  5059.9    8.22  5072.7    8.13  5129.5   36.29  5255.2   40.83
    5290   39.37  5356.4   41.81  5495.8   41.21  5565.8   43.01  5673.8   49.31
#Mann= 5 ,-1 , 0
  3557.4      .1       0  4859.9     .12       0  4929.9    .045       0
  5059.9    .125       0  5129.5      .1       0
#XS Ineff= 2 , 0
            4848    37.5    5106            38.2
Permanent Ineff=
       F       F
Bank Sta=4929.9,5059.9
XS Rating Curve= 0
Exp/Cntr=.5,.3

Type RM Length L Ch R = 1 ,115655.5,40,40,40
BEGIN DESCRIPTION:
Upstream Section of Bridge/Culvert/Weir
END DESCRIPTION:
XS GIS Cut Line= 5
      3119011.96     13842983.25      3119034.61     13842591.22
      3118742.73     13842221.67      3118589.57     13842045.42
      3118536.21     13841631.45
#Sta/Elev= 30
  4136.4   46.83  4156.4   45.29  4176.4    39.4  4196.4   38.35  4516.4   40.23
  4576.4   42.54  4706.4   42.95  4726.4   41.13  4735.9   37.24    4745   30.54
  4904.1   26.17  4935.9   11.57  4943.1    6.26  4949.1    2.05  4975.2   -2.38
  5007.7   -5.03  5039.5    -.89  5050.9    2.34  5063.1    9.53  5069.1    8.65
  5093.4   10.28  5094.5   12.11  5140.5   26.22  5217.7   26.48  5250.3   29.99
  5269.9   28.41  5360.9   35.52  5600.9   37.28  5620.9   41.45  5650.9    52.8
#Mann= 5 ,-1 , 0
  4136.4     .15       0  4735.9     .08       0  4943.1     .04       0
  5063.1     .08       0  5250.3     .15       0
#XS Ineff= 2 , 0
            4763      29    5279              29
Permanent Ineff=
       F       F
Bank Sta=4943.1,5063.1
XS Rating Curve= 0
Exp/Cntr=.5,.3

Type RM Length L Ch R = 3 ,115635.5,,,
BEGIN DESCRIPTION:
I 45
Structure ID: WOO-39
END DESCRIPTION:
Bridge Culvert--1,0,-1,-1, 0
Deck Dist Width WeirC Skew NumUp NumDn MinLoCord MaxHiCord MaxSubmerge Is_Ogee
10,20,2.6,0, 39, 39, , , .95, 0, 1,1,,
  4136.4  4146.4  4156.4  4166.4  4176.4  4186.4  4196.4  4396.4  4516.4  4536.4
  4556.4  4576.4    4593    4603    4613    4623    4643  4706.4  4716.4  4726.4
  4733.7  4744.6 4744.71  4744.8  4744.9    4745    5270 5270.19  5270.3  5360.9
  5390.9  5480.9  5570.9  5590.9  5600.9  5610.9  5620.9  5630.9  5650.9
    46.8   46.28   45.26   43.03   39.37   38.55   38.32   40.75    40.2   41.42
   41.66   42.51   49.34   49.49   48.93   47.56    42.6   42.93   42.53   41.11
   38.86   30.75   43.98      55      55      55      55   38.14   28.42   35.49
   35.19    37.2   37.86   37.07   37.25   38.54   41.42   45.59   52.77
    46.8   46.28   45.26   43.03   39.37   38.55   38.32   40.75    40.2   41.42
   41.66   42.51    42.6   42.66   42.71   42.69   42.59   42.92   42.52    41.1
   38.85   30.74   30.66   30.59   30.52   52.79   52.79   35.93   28.41   35.49
   35.19    37.2   37.86   37.07   37.25   38.54   41.42   45.59   52.77
  4136.4  4146.4  4156.4  4166.4  4176.4  4186.4  4196.4  4396.4  4516.4  4536.4
  4556.4  4576.4    4593    4603    4613    4623    4643  4706.4  4716.4  4726.4
  4733.7  4744.6 4744.71  4744.8  4744.9    4745    5270 5270.19  5270.3  5360.9
  5390.9  5480.9  5570.9  5590.9  5600.9  5610.9  5620.9  5630.9  5650.9
    46.8   46.28   45.26   43.03   39.37   38.55   38.32   40.75    40.2   41.42
   41.66   42.51   49.34   49.49   48.93   47.56    42.6   42.93   42.53   41.11
   38.86   30.75   43.98      55      55      55      55   38.14   28.42   35.49
   35.19    37.2   37.86   37.07   37.25   38.54   41.42   45.59   52.77
    46.7   46.18   45.16   42.93   39.27   38.45   38.22   40.65    40.1   41.32
   41.56   42.41    42.5   42.56   42.61   42.59   42.49   42.82   42.42      41
   38.75   30.64   30.56   30.49   30.42   52.69   52.69   35.83   28.31   35.39
   35.09    37.1   37.76   36.97   37.15   38.44   41.32   45.49   52.67
Pier Skew, UpSta & Num, DnSta & Num=  ,4767.5, 2 ,4767.5, 2 , 0 , 0 , 0 ,,
       3       3
   28.35   53.79
       3       3
   28.25   53.69
Pier Skew, UpSta & Num, DnSta & Num=  ,4816.9, 2 ,4816.9, 2 , 0 , 0 , 0 ,,
       3       3
   27.48   53.79
       3       3
   27.38   53.69
Pier Skew, UpSta & Num, DnSta & Num=  ,4935.9, 2 ,4935.9, 2 , 0 , 0 , 0 ,,
       3       3
    9.43   53.79
       3       3
    9.33   53.69
Pier Skew, UpSta & Num, DnSta & Num=  ,5069.1, 2 ,5069.1, 2 , 0 , 0 , 0 ,,
       3       3
    7.72   53.79
       3       3
    7.62   53.69
Pier Skew, UpSta & Num, DnSta & Num=  ,5184.3, 2 ,5184.3, 2 , 0 , 0 , 0 ,,
       3       3
   25.26   53.79
       3       3
   25.16   53.69
Pier Skew, UpSta & Num, DnSta & Num=  ,5250.8, 2 ,5250.8, 2 , 0 , 0 , 0 ,,
       3       3
   28.85   53.79
       3       3
   28.75   53.69
BR Coef= 1 , 1 , 0 ,1.25, 0 ,,,.8,0,2,0,
WSPro=,,,, 1 ,,,, 0 ,,,, 0 ,,,,-1 ,-1 ,-1 , 0 , 0 , 0 , 0 , 0
BR U #Sta/Elev= 71
  4136.4    46.8  4146.4   46.28  4156.4   45.26  4166.4   43.03  4176.4   39.37
  4186.4   38.55  4196.4   38.32  4396.4   40.75  4516.4    40.2  4536.4   41.42
  4556.4   41.66  4576.4   42.51    4593    42.6    4603   42.66    4613   42.71
  4616.4   42.73    4623   42.69    4643   42.59  4646.4   42.57    4653   42.61
  4706.4   42.92  4716.4   42.52  4726.4    41.1  4733.7   38.85  4735.9   37.21
  4744.6   30.74 4744.71   30.66  4744.8   30.59  4744.9   30.52    4745   30.51
  4745.1   30.51  4767.5   29.38  4791.2   28.88  4816.9   28.52  4904.1   26.14
  4935.9   11.54  4943.1    6.23  4949.1    2.02  4975.2   -2.41  5007.7   -5.06
  5039.5    -.92  5050.9    2.31  5063.1     9.5  5069.1    8.62  5093.4   10.25
  5094.5   12.08  5140.5   26.19    5154   26.39  5154.2   25.88  5174.1   25.56
  5174.5   26.18  5184.3   26.28  5217.7   26.45  5250.3   29.96  5250.8   30.01
  5269.9   28.38    5270   28.39  5270.1    28.4 5270.19    28.4  5270.3   28.41
  5270.4   28.42  5360.9   35.49  5390.9   35.19  5480.9    37.2  5570.9   37.86
  5590.9   37.07  5600.9   37.25  5610.9   38.54  5620.9   41.42  5630.9   45.59
  5650.9   52.77
BR U #Mann= 5
  4136.4     .15  4735.9     .08  4943.1     .04  5063.1     .08  5250.3     .15
BR U Banks=4943.1,5063.1
BR D #Sta/Elev= 71
  4136.4    46.7  4146.4   46.18  4156.4   45.16  4166.4   42.93  4176.4   39.27
  4186.4   38.45  4196.4   38.22  4396.4   40.65  4516.4    40.1  4536.4   41.32
  4556.4   41.56  4576.4   42.41    4593    42.5    4603   42.56    4613   42.61
  4616.4   42.63    4623   42.59    4643   42.49  4646.4   42.47    4653   42.51
  4706.4   42.82  4716.4   42.42  4726.4      41  4733.7   38.75  4735.9   37.11
  4744.6   30.64 4744.71   30.56  4744.8   30.49  4744.9   30.42    4745   30.41
  4745.1   30.41  4767.5   29.28  4791.2   28.78  4816.9   28.42  4904.1   26.04
  4935.9   11.44  4943.1    6.13  4949.1    1.92  4975.2   -2.51  5007.7   -5.16
  5039.5   -1.02  5050.9    2.21  5063.1     9.4  5069.1    8.52  5093.4   10.15
  5094.5   11.98  5140.5   26.09    5154   26.29  5154.2   25.78  5174.1   25.46
  5174.5   26.08  5184.3   26.18  5217.7   26.35  5250.3   29.86  5250.8   29.91
  5269.9   28.28    5270   28.29  5270.1    28.3 5270.19    28.3  5270.3   28.31
  5270.4   28.32  5360.9   35.39  5390.9   35.09  5480.9    37.1  5570.9   37.76
  5590.9   36.97  5600.9   37.15  5610.9   38.44  5620.9   41.32  5630.9   45.49
  5650.9   52.67
BR D #Mann= 5
  4136.4     .15  4735.9     .08  4943.1     .04  5063.1     .08  5250.3     .15
BR D Banks=4943.1,5063.1
BC Design=,, 0 ,, 0 ,,,,,,
BC HTab HWMax=52.8

Type RM Length L Ch R = 1 ,115615.5,42,42,42
BEGIN DESCRIPTION:
Downstream Section of Bridge/Culvert/Weir
END DESCRIPTION:
XS GIS Cut Line= 5
      3119049.45     13842969.32      3119072.11     13842577.28
      3118780.23     13842207.73      3118627.07     13842031.48
      3118573.71     13841617.52
#Sta/Elev= 30
  4136.4   46.59  4156.4   45.05  4176.4   39.16  4196.4   38.11  4516.4   39.99
  4576.4    42.3  4706.4   42.71  4726.4   40.89  4735.9      37    4745    30.3
  4904.1   25.93  4935.9   11.33  4943.1    6.02  4949.1    1.81  4975.2   -2.62
  5007.7   -5.27  5039.5   -1.13  5050.9     2.1  5063.1    9.29  5069.1    8.41
  5093.4   10.04  5094.5   11.87  5140.5   25.98  5217.7   26.24  5250.3   29.75
  5269.9   28.17  5360.9   35.28  5600.9   37.04  5620.9   41.21  5650.9   52.56
#Mann= 5 ,-1 , 0
  4136.4     .15       0  4735.9     .08       0  4943.1     .04       0
  5063.1     .08       0  5250.3     .15       0
#XS Ineff= 2 , 0
            4763    29.5    5279            29.5
Permanent Ineff=
       F       F
Bank Sta=4943.1,5063.1
XS Rating Curve= 0
Exp/Cntr=.5,.3

Type RM Length L Ch R = 1 ,115573.5,40,40,40
BEGIN DESCRIPTION:
Upstream Section of Bridge/Culvert/Weir
END DESCRIPTION:
XS GIS Cut Line= 6
      3119069.83     13842958.69      3119086.79      13842584.6
      3119044.14     13842536.89      3119003.92     13842381.88
       3118634.4     13842029.12      3118585.94     13841627.39
#Sta/Elev= 30
  4136.4   46.91  4156.4   45.37  4176.4   39.48  4196.4   38.43  4616.4   42.84
  4706.4   43.03  4729.9   40.13  4733.7   38.96  4736.8   25.56  4742.1   28.16
  4869.3   21.93  4905.4   23.02  4940.2    9.59    4952   -1.83  5006.9   -5.72
  5050.8    -.18  5051.7    2.58  5058.1    5.49  5062.6   11.38  5091.5    9.37
  5117.1   10.75  5150.3   18.27  5176.7   26.12  5222.7   27.38  5258.2    40.8
  5274.5   43.97  5480.9   37.31  5600.9   37.36  5620.9   41.53  5650.9   52.88
#Mann= 5 ,-1 , 0
  4136.4     .15       0  4729.9     .07       0  4940.2     .04       0
  5062.6     .07       0  5150.3     .15       0
#XS Ineff= 2 , 0
          4732.2    38.4  5250.8              37
Permanent Ineff=
       F       F
Bank Sta=4940.2,5062.6
XS Rating Curve= 0
Exp/Cntr=.5,.3

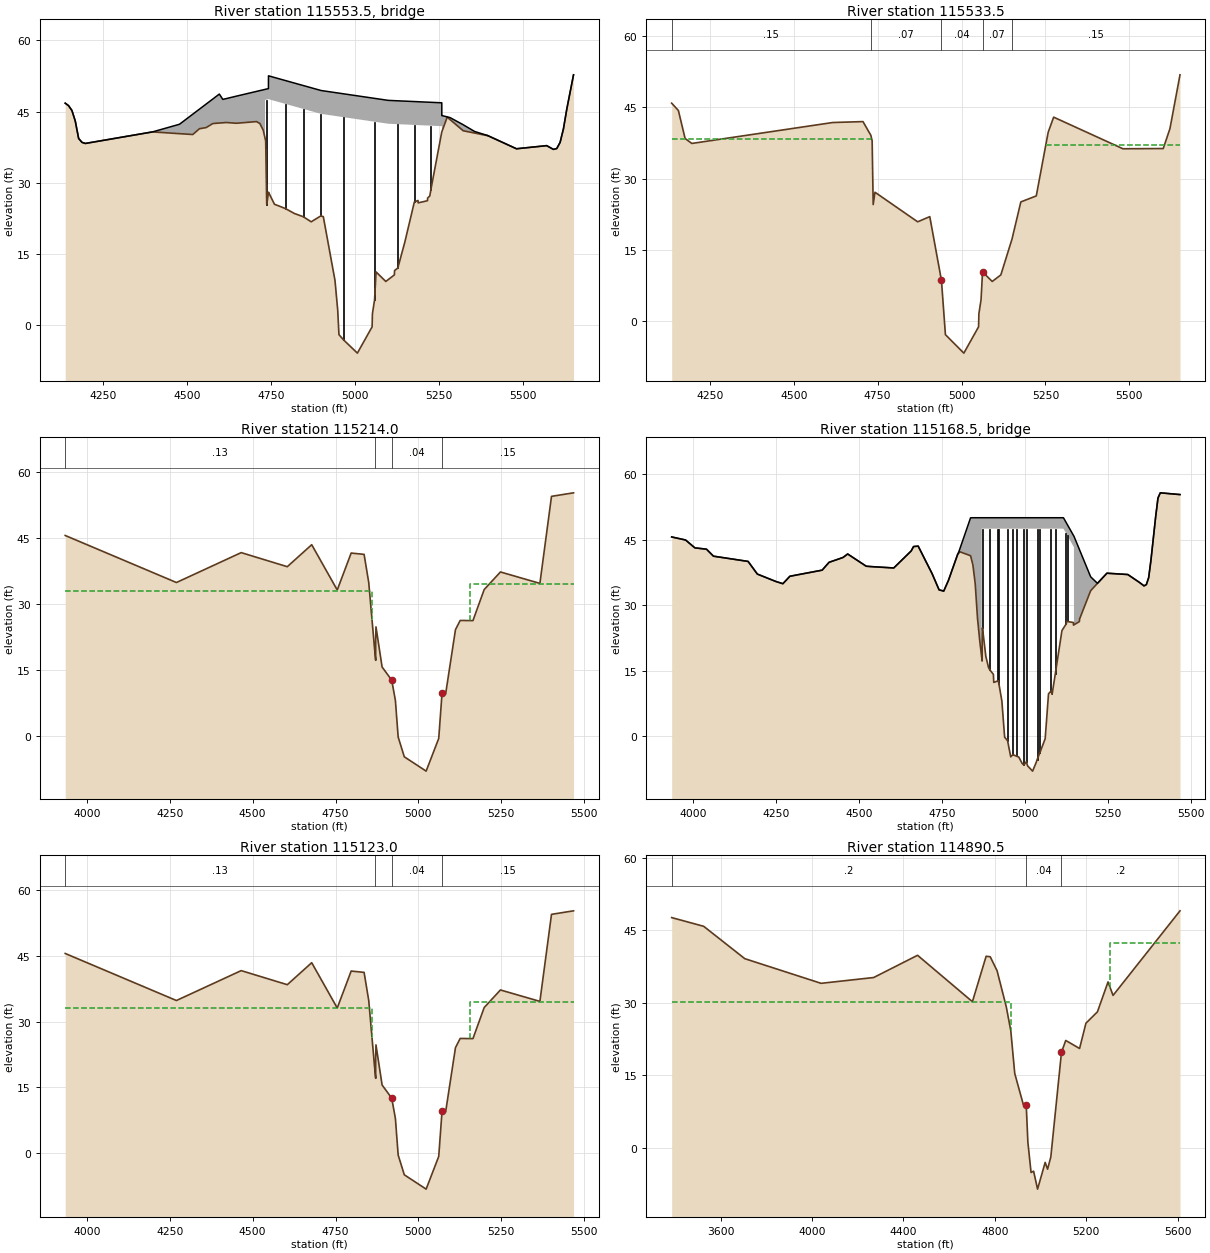
Type RM Length L Ch R = 3 ,115553.5,,,
BEGIN DESCRIPTION:
I 45 S- W ALLEN PARKWAY
Structure ID: WOO-38
END DESCRIPTION:
Bridge Culvert--1,0,-1,-1, 0
Deck Dist Width WeirC Skew NumUp NumDn MinLoCord MaxHiCord MaxSubmerge Is_Ogee
10,20,2.6,0, 44, 44, , , .95, 0, 1,1,,
  4136.4  4146.4  4156.4  4166.4  4176.4  4186.4  4196.4  4396.4  4476.8  4516.4
  4536.4  4556.4  4576.4  4595.6    4606  4616.4  4646.4  4706.4  4716.4  4726.4
 4731.81  4731.9 4741.89    4742 4742.21  4898.6    5099  5258.4  5258.5 5258.79
  5258.9  5274.5  5282.8  5322.2  5356.2  5394.5  5480.9  5570.9  5590.9  5600.9
  5610.9  5620.9  5630.9  5650.9
    46.8   46.28   45.26   43.03   39.37   38.55   38.32   40.75   42.36   44.48
   45.55   46.62   47.69   48.72    47.6   47.77   48.28   49.28   49.45   49.61
    49.7   49.71   49.86   52.56   52.56   49.47   47.39   46.88   44.18   44.18
   44.19   43.92   43.77   42.26   40.84      40    37.2   37.86   37.07   37.25
   38.54   41.42   45.59   52.77
    46.8   46.28   45.26   43.03   39.37   38.55   38.32   40.75   40.38    40.2
   41.42   41.66   42.51   42.62   42.67   42.73   42.57   42.92   42.52    41.1
   39.43   47.49   47.64   47.64   47.64   44.55   42.47   41.96   41.96   41.96
   40.83   43.86   43.36   40.99   40.51      40    37.2   37.86   37.07   37.25
   38.54   41.42   45.59   52.77
  4136.4  4146.4  4156.4  4166.4  4176.4  4186.4  4196.4  4396.4  4476.8  4516.4
  4536.4  4556.4  4576.4  4595.6    4606  4616.4  4646.4  4706.4  4716.4  4726.4
 4731.81  4731.9 4741.89    4742 4742.21  4898.6    5099  5258.4  5258.5 5258.79
  5258.9  5274.5  5282.8  5322.2  5356.2  5394.5  5480.9  5570.9  5590.9  5600.9
  5610.9  5620.9  5630.9  5650.9
    46.8   46.28   45.26   43.03   39.37   38.55   38.32   40.75   42.36   44.48
   45.55   46.62   47.69   48.72    47.6   47.77   48.28   49.28   49.45   49.61
    49.7   49.71   49.86   52.56   52.56   49.47   47.39   46.88   44.18   44.18
   44.19   43.92   43.77   42.26   40.84      40    37.2   37.86   37.07   37.25
   38.54   41.42   45.59   52.77
    45.9   45.38   44.36   42.13   38.47   37.65   37.42   39.85   39.48    39.3
   40.52   40.76   41.61   41.72   41.77   41.83   41.67   42.02   41.62    40.2
   38.53   46.59   46.74   46.74   46.74   43.65   41.57   41.06   41.06   41.06
   39.93   42.96   42.46   40.09   39.61    39.1    36.3   36.96   36.17   36.35
   37.64   40.52   44.69   51.87
Pier Skew, UpSta & Num, DnSta & Num=  ,4736.8, 2 ,4736.8, 2 , 0 , 0 , 0 ,,
     2.8     2.8
   25.14   48.59
     2.8     2.8
   24.24   47.69
Pier Skew, UpSta & Num, DnSta & Num=  ,4792.6, 2 ,4792.6, 2 , 0 , 0 , 0 ,,
     2.8     2.8
   23.56   47.67
     2.8     2.8
   22.66   46.77
Pier Skew, UpSta & Num, DnSta & Num=  ,4845.8, 2 ,4845.8, 2 , 0 , 0 , 0 ,,
     2.8     2.8
   21.83   46.62
     2.8     2.8
   20.93   45.72
Pier Skew, UpSta & Num, DnSta & Num=  ,4897.9, 2 ,4897.9, 2 , 0 , 0 , 0 ,,
     2.8     2.8
      22   45.59
     2.8     2.8
    21.1   44.69
Pier Skew, UpSta & Num, DnSta & Num=  ,4965.6, 2 ,4965.6, 2 , 0 , 0 , 0 ,,
     2.8     2.8
   -4.12   44.87
     2.8     2.8
   -5.02   43.97
Pier Skew, UpSta & Num, DnSta & Num=  ,5058.1, 2 ,5058.1, 2 , 0 , 0 , 0 ,,
     2.8     2.8
    3.74   43.91
     2.8     2.8
    2.84   43.01
Pier Skew, UpSta & Num, DnSta & Num=  ,5127.4, 2 ,5127.4, 2 , 0 , 0 , 0 ,,
     2.8     2.8
   11.01   43.38
     2.8     2.8
   10.11   42.48
Pier Skew, UpSta & Num, DnSta & Num=  ,5176.7, 2 ,5176.7, 2 , 0 , 0 , 0 ,,
     2.8     2.8
   24.59   43.22
     2.8     2.8
   23.69   42.32
Pier Skew, UpSta & Num, DnSta & Num=  ,5225.6, 2 ,5225.6, 2 , 0 , 0 , 0 ,,
     2.8     2.8
   26.91   43.06
     2.8     2.8
   26.01   42.16
BR Coef= 1 , 1 , 0 ,1.25, 0 ,,,.8,0,2,1,
WSPro=,,,, 1 ,,,, 0 ,,,, 0 ,,,,-1 ,-1 ,-1 , 0 , 0 , 0 , 0 , 0
BR U #Sta/Elev= 88
  4136.4    46.8  4146.4   46.28  4156.4   45.26  4166.4   43.03  4176.4   39.37
  4186.4   38.55  4196.4   38.32  4396.4   40.75  4476.8   40.38  4516.4    40.2
  4536.4   41.42  4556.4   41.66  4576.4   42.51  4595.6   42.62  4605.6   42.67
    4606   42.67  4616.4   42.73  4646.4   42.57  4706.4   42.92  4716.4   42.52
  4726.4    41.1  4729.9   40.02 4731.81   39.43  4731.9    39.4  4732.4   39.25
  4733.7   38.85  4736.8   25.45  4741.7   27.85  4741.8    27.9 4741.89   27.95
    4742      28  4742.1   28.05 4742.21   28.03  4759.9   25.52  4792.6   24.61
    4819   23.58  4845.8   22.89  4869.3   21.82  4897.9   23.06  4898.6   23.05
  4905.4   22.91  4940.2    9.48  4948.3    3.25    4952   -1.94  4965.6   -3.03
  5006.9   -5.83  5050.8    -.29  5051.7    2.47  5058.1    5.38  5062.6   11.27
  5091.5    9.26    5099    9.66  5117.1   10.64  5117.7   11.56  5127.4   12.09
  5148.4   17.59  5150.3   18.16  5176.7   26.01  5187.6   26.31    5188   25.81
  5215.7   26.26  5216.1   26.82  5222.7   27.27  5225.6    28.5  5258.2   40.69
 5258.29   40.71  5258.4   40.73  5258.5   40.75 5258.61   40.77  5258.7   40.79
 5258.79    40.8  5258.9   40.83    5259   40.85  5274.5   43.86  5282.8   43.36
  5319.7   41.14  5322.2   40.99  5356.2   40.51  5394.1   39.97  5394.5      40
  5480.9    37.2  5570.9   37.86  5590.9   37.07  5600.9   37.25  5610.9   38.54
  5620.9   41.42  5630.9   45.59  5650.9   52.77
BR U #Mann= 5
  4136.4     .15  4729.9     .07  4940.2     .04  5062.6     .07  5150.3     .15
BR U Banks=4940.2,5062.6
BR D #Sta/Elev= 88
  4136.4    45.9  4146.4   45.38  4156.4   44.36  4166.4   42.13  4176.4   38.47
  4186.4   37.65  4196.4   37.42  4396.4   39.85  4476.8   39.48  4516.4    39.3
  4536.4   40.52  4556.4   40.76  4576.4   41.61  4595.6   41.72  4605.6   41.77
    4606   41.77  4616.4   41.83  4646.4   41.67  4706.4   42.02  4716.4   41.62
  4726.4    40.2  4729.9   39.12 4731.81   38.53  4731.9    38.5  4732.4   38.35
  4733.7   37.95  4736.8   24.55  4741.7   26.95  4741.8      27 4741.89   27.05
    4742    27.1  4742.1   27.15 4742.21   27.13  4759.9   24.62  4792.6   23.71
    4819   22.68  4845.8   21.99  4869.3   20.92  4897.9   22.16  4898.6   22.15
  4905.4   22.01  4940.2    8.58  4948.3    2.35    4952   -2.84  4965.6   -3.93
  5006.9   -6.73  5050.8   -1.19  5051.7    1.57  5058.1    4.48  5062.6   10.37
  5091.5    8.36    5099    8.76  5117.1    9.74  5117.7   10.66  5127.4   11.19
  5148.4   16.69  5150.3   17.26  5176.7   25.11  5187.6   25.41    5188   24.91
  5215.7   25.36  5216.1   25.92  5222.7   26.37  5225.6    27.6  5258.2   39.79
 5258.29   39.81  5258.4   39.83  5258.5   39.85 5258.61   39.87  5258.7   39.89
 5258.79    39.9  5258.9   39.93    5259   39.95  5274.5   42.96  5282.8   42.46
  5319.7   40.24  5322.2   40.09  5356.2   39.61  5394.1   39.07  5394.5    39.1
  5480.9    36.3  5570.9   36.96  5590.9   36.17  5600.9   36.35  5610.9   37.64
  5620.9   40.52  5630.9   44.69  5650.9   51.87
BR D #Mann= 5
  4136.4     .15  4729.9     .07  4940.2     .04  5062.6     .07  5150.3     .15
BR D Banks=4940.2,5062.6
BC Design=,, 0 ,, 0 ,,,,,,
BC HTab HWMax=52.88

Type RM Length L Ch R = 1 ,115533.5,319.5,319.5,319.5
BEGIN DESCRIPTION:
Downstream Section of Bridge/Culvert/Weir
END DESCRIPTION:
XS GIS Cut Line= 6
      3119108.14      13842947.2      3119125.11      13842573.1
      3119082.46     13842525.39      3119042.24     13842370.38
      3118672.72     13842017.62      3118624.26      13841615.9
#Sta/Elev= 30
  4136.4   45.86  4156.4   44.32  4176.4   38.43  4196.4   37.38  4616.4   41.79
  4706.4   41.98  4729.9   39.08  4733.7   37.91  4736.8   24.51  4742.1   27.11
  4869.3   20.88  4905.4   21.97  4940.2    8.54    4952   -2.88  5006.9   -6.77
  5050.8   -1.23  5051.7    1.53  5058.1    4.44  5062.6   10.33  5091.5    8.32
  5117.1     9.7  5150.3   17.22  5176.7   25.07  5222.7   26.33  5258.2   39.75
  5274.5   42.92  5480.9   36.26  5600.9   36.31  5620.9   40.48  5650.9   51.83
#Mann= 5 ,-1 , 0
  4136.4     .15       0  4729.9     .07       0  4940.2     .04       0
  5062.6     .07       0  5150.3     .15       0
#XS Ineff= 2 , 0
          4732.2    38.4  5250.8              37
Permanent Ineff=
       F       F
Bank Sta=4940.2,5062.6
XS Rating Curve= 0
Exp/Cntr=.5,.3

Type RM Length L Ch R = 1 ,115214.0,91,91,91
BEGIN DESCRIPTION:
Upstream Section of Bridge/Culvert/Weir
END DESCRIPTION:
XS GIS Cut Line= 5
      3119117.12     13843173.94      3119167.27     13842283.64
      3119117.19     13842118.05      3119034.14     13841864.32
       3118991.7     13841667.53
#Sta/Elev= 30
 3934.74   45.64 4270.18   34.94 4465.48   41.74  4604.5   38.54 4678.14   43.54
 4755.14   33.24 4797.14   41.64 4836.13   41.34 4850.13   34.94  4869.8   18.08
 4871.13   17.24  4871.2   22.42 4871.97   24.85 4890.42   15.73  4919.5   12.72
 4930.56    8.09 4938.89     -.2 4957.37    -4.7 5023.24   -7.96 5061.18    -.53
 5071.19    9.74 5082.04    9.62 5111.72   24.22 5125.93   26.31 5164.36   26.27
 5198.31   33.34 5247.31   37.34 5366.31   34.74 5401.31   54.54 5467.74   55.34
#Mann= 4 ,-1 , 0
 3934.74     .13       0  4869.8     .08       0  4919.5     .04       0
 5071.19     .15       0
#XS Ineff= 2 , 0
            4860    33.1    5155            34.5
Permanent Ineff=
       F       F
Bank Sta=4919.5,5071.19
XS Rating Curve= 0
Exp/Cntr=.5,.3

Type RM Length L Ch R = 3 ,115168.5,,,
BEGIN DESCRIPTION:
I 45-ALLEN PARKWAY       Skew Angle 45 degrees
Structure ID: WOO-36
END DESCRIPTION:
Bridge Culvert--1,0,-1,-1, 0
Deck Dist Width WeirC Skew NumUp NumDn MinLoCord MaxHiCord MaxSubmerge Is_Ogee
10,71,2.6,0, 52, 52, , , .95, 0, 1,1,,
 3934.74 3976.74 4004.74 4039.74 4060.74 4165.18 4193.18 4249.18 4270.18 4291.18
 4388.48 4409.48 4451.48 4465.48 4521.48  4604.5 4657.14 4664.14 4678.14 4720.14
 4741.14 4755.14 4769.14 4797.14  4801.2 4804.14 4836.13 4843.13 4850.13 4857.13
 4864.13 4869.71  4869.8  5116.2 5147.91 5148.02 5148.12 5164.36 5164.78 5198.31
 5218.82 5247.31 5310.31 5345.31 5359.31 5366.31 5373.31 5380.31 5394.31 5401.31
 5408.31 5467.74
    45.6    44.9    43.1    42.8    41.2      40    37.1    35.4    34.9    36.6
      38    39.8    40.9    41.7    38.9    38.5    42.4    43.4    43.5    37.2
    33.5    33.2    35.6    41.6    42.3   42.95   49.98      50      50      50
      50      50      50      50   45.76   45.75   45.73   42.74   42.66   36.48
   34.98    37.3      37    35.2    34.4    34.7    36.3    40.4    50.2    54.5
    55.7    55.3
    45.6    44.9    43.1    42.8    41.2      40    37.1    35.4    34.9    36.6
      38    39.8    40.9    41.7    38.9    38.5    42.4    43.4    43.5    37.2
    33.5    33.2    35.6    41.6   41.95    42.2    41.3    39.2    34.9    26.9
    21.6   18.09    47.5    47.5   43.26   25.49   25.49   26.23   26.79    33.3
   34.97    37.3      37    35.2    34.4    34.7    36.3    40.4    50.2    54.5
    55.7    55.3
 3934.74 3976.74 4004.74 4039.74 4060.74 4165.18 4193.18 4249.18 4270.18 4291.18
 4388.48 4409.48 4451.48 4465.48 4521.48  4604.5 4657.14 4664.14 4678.14 4720.14
 4741.14 4755.14 4769.14 4797.14  4801.2 4804.14 4836.13 4843.13 4850.13 4857.13
 4864.13 4869.71  4869.8  5116.2 5147.91 5148.02 5148.12 5164.36 5164.78 5198.31
 5218.82 5247.31 5310.31 5345.31 5359.31 5366.31 5373.31 5380.31 5394.31 5401.31
 5408.31 5467.74
    45.6    44.9    43.1    42.8    41.2      40    37.1    35.4    34.9    36.6
      38    39.8    40.9    41.7    38.9    38.5    42.4    43.4    43.5    37.2
    33.5    33.2    35.6    41.6    42.3   42.95   49.98      50      50      50
      50      50      50      50   45.76   45.75   45.73   42.74   42.66   36.48
   34.98    37.3      37    35.2    34.4    34.7    36.3    40.4    50.2    54.5
    55.7    55.3
    45.5    44.8      43    42.7    41.1    39.9      37    35.3    34.8    36.5
    37.9    39.7    40.8    41.6    38.8    38.4    42.3    43.3    43.4    37.1
    33.4    33.1    35.5    41.5   41.85    42.1    41.2    39.1    34.8    26.8
    21.5   17.99    47.4    47.4   43.16   25.39   25.39   26.13   26.69    33.2
   34.87    37.2    36.9    35.1    34.3    34.6    36.2    40.3    50.1    54.4
    55.6    55.2
Pier Skew, UpSta & Num, DnSta & Num=  ,4872, 2 ,4872, 2 , 0 , 0 , 0 ,,
     2.5     2.5
   16.46    48.5
     2.5     2.5
   16.36    48.4
Pier Skew, UpSta & Num, DnSta & Num=  ,4893.9, 2 ,4893.9, 2 , 0 , 0 , 0 ,,
     2.5     2.5
   14.11    48.5
     2.5     2.5
   14.01    48.4
Pier Skew, UpSta & Num, DnSta & Num=  ,4918.2, 2 ,4918.2, 2 , 0 , 0 , 0 ,,
     2.5     2.5
   11.61    48.5
     2.5     2.5
   11.51    48.4
Pier Skew, UpSta & Num, DnSta & Num=  ,4921.5, 2 ,4921.5, 2 , 0 , 0 , 0 ,,
     2.5     2.5
   10.47    48.5
     2.5     2.5
   10.37    48.4
Pier Skew, UpSta & Num, DnSta & Num=  ,4947.7, 2 ,4947.7, 2 , 0 , 0 , 0 ,,
     2.5     2.5
   -2.51    48.5
     2.5     2.5
   -2.61    48.4
Pier Skew, UpSta & Num, DnSta & Num=  ,4963.7, 2 ,4963.7, 2 , 0 , 0 , 0 ,,
     2.5     2.5
   -5.32    48.5
     2.5     2.5
   -5.42    48.4
Pier Skew, UpSta & Num, DnSta & Num=  ,4974.4, 2 ,4974.4, 2 , 0 , 0 , 0 ,,
     2.5     2.5
   -5.61    48.5
     2.5     2.5
   -5.71    48.4
Pier Skew, UpSta & Num, DnSta & Num=  ,4996.9, 2 ,4996.9, 2 , 0 , 0 , 0 ,,
     2.5     2.5
   -7.52    48.5
     2.5     2.5
   -7.62    48.4
Pier Skew, UpSta & Num, DnSta & Num=  ,5004.4, 2 ,5004.4, 2 , 0 , 0 , 0 ,,
     2.5     2.5
   -7.17    48.5
     2.5     2.5
   -7.27    48.4
Pier Skew, UpSta & Num, DnSta & Num=  ,5036.9, 2 ,5036.9, 2 , 0 , 0 , 0 ,,
     2.5     2.5
   -6.64    48.5
     2.5     2.5
   -6.74    48.4
Pier Skew, UpSta & Num, DnSta & Num=  ,5044.5, 2 ,5044.5, 2 , 0 , 0 , 0 ,,
     2.5     2.5
   -5.16    48.5
     2.5     2.5
   -5.26    48.4
Pier Skew, UpSta & Num, DnSta & Num=  ,5077.1, 2 ,5077.1, 2 , 0 , 0 , 0 ,,
     2.5     2.5
    9.09    48.5
     2.5     2.5
    8.99    48.4
Pier Skew, UpSta & Num, DnSta & Num=  ,5091.6, 2 ,5091.6, 2 , 0 , 0 , 0 ,,
     2.5     2.5
   12.59    48.5
     2.5     2.5
   12.49    48.4
Pier Skew, UpSta & Num, DnSta & Num=  ,5123.4, 2 ,5123.4, 2 , 0 , 0 , 0 ,,
     2.5     2.5
   24.42    47.7
     2.5     2.5
   24.32    47.6
Pier Skew, UpSta & Num, DnSta & Num=  ,5127.3, 2 ,5127.3, 2 , 0 , 0 , 0 ,,
     2.5     2.5
   25.24   47.18
     2.5     2.5
   25.14   47.08
Abutment Skew #Up #Dn= , 2 , 2
  4869.6 4890.52
    47.5   15.68
  4869.6 4890.52
    47.4   15.58
Abutment Skew #Up #Dn= , 2 , 2
 5082.04 5148.11
    9.58   43.26
 5082.04 5148.11
    9.48   43.16
BR Coef= 1 , 1 , 0 ,1.25, 0 ,,,.8,0,2,1,
WSPro=,,,, 1 ,,,, 0 ,,,, 0 ,,,,-1 ,-1 ,-1 , 0 , 0 , 0 , 0 , 0
BR U #Sta/Elev= 95
 3934.74    45.6 3976.74    44.9 4004.74    43.1 4039.74    42.8 4060.74    41.2
 4165.18      40 4193.18    37.1 4249.18    35.4 4270.18    34.9 4291.18    36.6
 4325.48    37.1 4388.48      38 4409.48    39.8 4451.48    40.9 4465.48    41.7
 4521.48    38.9  4534.5    38.8  4604.5    38.5 4657.14    42.4 4664.14    43.4
 4678.14    43.5 4720.14    37.2 4741.14    33.5 4755.14    33.2 4769.14    35.6
 4797.14    41.6  4801.2   41.95 4804.14    42.2 4836.13    41.3  4836.2   41.28
 4843.13    39.2 4850.13    34.9 4857.13    26.9 4864.13    21.6 4869.71   18.09
  4869.8   18.04 4871.13    17.2  4871.2   22.38  4871.9   24.59 4871.97   24.81
 4882.19   18.27 4890.42   15.69 4890.52   15.68 4893.88   15.23 4905.01   14.14
 4906.06    12.3 4918.17   12.65  4919.5   12.68 4921.53   12.02 4930.56    8.05
 4938.89    -.24 4947.71   -1.03 4957.37   -4.74 4963.74   -4.22 4974.38   -4.57
 4981.59   -4.78 4991.53   -6.21 4996.92   -6.62 5004.41   -5.85 5008.05   -6.79
 5023.24      -8 5033.88   -6.04 5036.89   -5.36 5044.52   -3.92 5061.18    -.57
 5071.19     9.7 5077.14   10.19 5081.41   10.54 5081.94    9.73 5082.04    9.58
 5091.56    14.2 5111.72   24.18  5116.2   24.71 5124.81   25.73 5125.93   26.27
 5146.16   26.02 5146.58   25.42 5147.91   25.48 5148.02   25.49 5148.12   25.49
 5164.36   26.23 5164.78   26.79 5198.31    33.3 5218.82   34.97 5247.31    37.3
 5310.31      37 5345.31    35.2 5359.31    34.4 5366.31    34.7 5373.31    36.3
 5380.31    40.4 5394.31    50.2 5401.31    54.5 5408.31    55.7 5467.74    55.3
BR U #Mann= 4
 3934.74     .13  4869.8     .08  4919.5     .04 5071.19     .15
BR U Banks=4919.5,5071.19
BR D #Sta/Elev= 95
 3934.74    45.5 3976.74    44.8 4004.74      43 4039.74    42.7 4060.74    41.1
 4165.18    39.9 4193.18      37 4249.18    35.3 4270.18    34.8 4291.18    36.5
 4325.48      37 4388.48    37.9 4409.48    39.7 4451.48    40.8 4465.48    41.6
 4521.48    38.8  4534.5    38.7  4604.5    38.4 4657.14    42.3 4664.14    43.3
 4678.14    43.4 4720.14    37.1 4741.14    33.4 4755.14    33.1 4769.14    35.5
 4797.14    41.5  4801.2   41.85 4804.14    42.1 4836.13    41.2  4836.2   41.18
 4843.13    39.1 4850.13    34.8 4857.13    26.8 4864.13    21.5 4869.71   17.99
  4869.8   17.94 4871.13    17.1  4871.2   22.28  4871.9   24.49 4871.97   24.71
 4882.19   18.17 4890.42   15.59 4890.52   15.58 4893.88   15.13 4905.01   14.04
 4906.06    12.2 4918.17   12.55  4919.5   12.58 4921.53   11.92 4930.56    7.95
 4938.89    -.34 4947.71   -1.13 4957.37   -4.84 4963.74   -4.32 4974.38   -4.67
 4981.59   -4.88 4991.53   -6.31 4996.92   -6.72 5004.41   -5.95 5008.05   -6.89
 5023.24    -8.1 5033.88   -6.14 5036.89   -5.46 5044.52   -4.02 5061.18    -.67
 5071.19     9.6 5077.14   10.09 5081.41   10.44 5081.94    9.63 5082.04    9.48
 5091.56    14.1 5111.72   24.08  5116.2   24.61 5124.81   25.63 5125.93   26.17
 5146.16   25.92 5146.58   25.32 5147.91   25.38 5148.02   25.39 5148.12   25.39
 5164.36   26.13 5164.78   26.69 5198.31    33.2 5218.82   34.87 5247.31    37.2
 5310.31    36.9 5345.31    35.1 5359.31    34.3 5366.31    34.6 5373.31    36.2
 5380.31    40.3 5394.31    50.1 5401.31    54.4 5408.31    55.6 5467.74    55.2
BR D #Mann= 4
 3934.74     .13  4869.8     .08  4919.5     .04 5071.19     .15
BR D Banks=4919.5,5071.19
BC Design=,, 0 ,, 0 ,,,,,,
BC HTab HWMax=55.74

Type RM Length L Ch R = 1 ,115123.0,232.5,232.5,232.5
BEGIN DESCRIPTION:
Downstream Section of Bridge/Culvert/Weir
END DESCRIPTION:
XS GIS Cut Line= 5
      3119175.22     13843243.98      3119225.37     13842353.68
      3119175.29     13842188.09      3119092.24     13841934.36
       3119049.8     13841737.57
#Sta/Elev= 30
 3934.74   45.48 4270.18   34.78 4465.48   41.58  4604.5   38.38 4678.14   43.38
 4755.14   33.08 4797.14   41.48 4836.13   41.18 4850.13   34.78  4869.8   17.92
 4871.13   17.08  4871.2   22.26 4871.97   24.69 4890.42   15.57  4919.5   12.56
 4930.56    7.93 4938.89    -.36 4957.37   -4.86 5023.24   -8.12 5061.18    -.69
 5071.19    9.58 5082.04    9.46 5111.72   24.06 5125.93   26.15 5164.36   26.11
 5198.31   33.18 5247.31   37.18 5366.31   34.58 5401.31   54.38 5467.74   55.18
#Mann= 4 ,-1 , 0
 3934.74     .13       0  4869.8     .08       0  4919.5     .04       0
 5071.19     .15       0
#XS Ineff= 2 , 0
            4860    33.1    5155            34.5
Permanent Ineff=
       F       F
Bank Sta=4919.5,5071.19
XS Rating Curve= 0
Exp/Cntr=.5,.3

Type RM Length L Ch R = 1 ,114890.5,52,52,52
BEGIN DESCRIPTION:
Upstream Section of Bridge/Culvert/Weir
END DESCRIPTION:
XS GIS Cut Line= 6
      3118992.47      13843887.1      3119310.16     13843442.98
      3119369.53     13842426.37      3119411.48     13842286.45
      3119510.32     13842219.73      3119899.48     13842167.99
#Sta/Elev= 30
  3386.2   47.62  3526.2   45.82  3706.2   39.12    4040   34.02    4270   35.22
  4462.2   39.82  4702.2   30.22  4762.2   39.62  4780.1   39.52  4810.1   36.62
  4850.1   29.22  4870.1   24.22  4887.4   15.37  4925.1    8.91  4937.7    8.78
  4944.9    1.14  4958.8   -5.12  4969.9   -4.85  4987.3   -8.56  5020.5   -3.03
    5031   -4.43  5045.2   -1.92  5091.9   19.75  5110.5    22.2  5171.1   20.54
  5198.9   25.77  5249.2   28.12  5295.6   34.31  5317.6   31.52  5610.5   49.02
#Mann= 3 ,-1 , 0
  3386.2      .2       0  4937.7     .04       0  5091.9      .2       0
#XS Ineff= 2 , 0
            4870    30.2    5305            42.3
Permanent Ineff=
       F       F
Bank Sta=4937.7,5091.9
XS Rating Curve= 0
Exp/Cntr=.5,.3