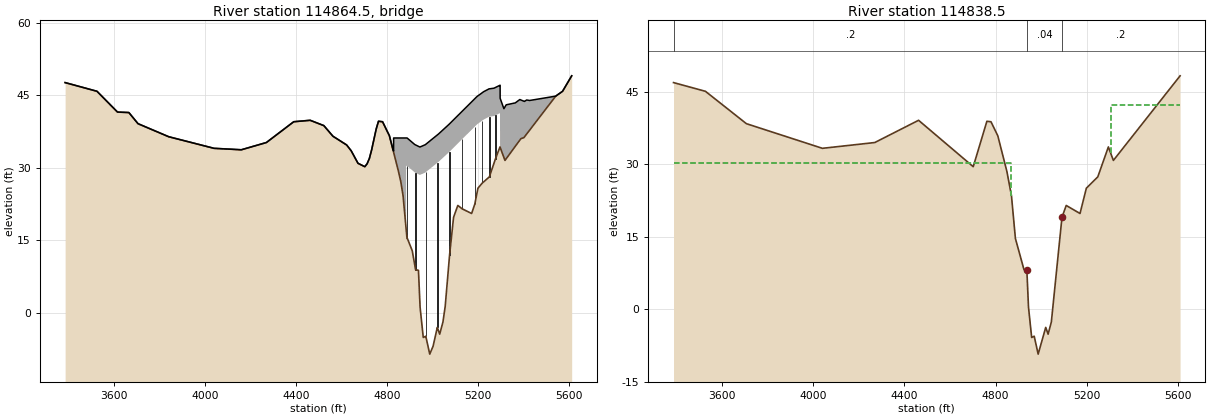
HEC-RAS study W100-00-00.prj: W100-00-00

--- W100-00-00.g01 (geometry) --- (continued)

Type RM Length L Ch R = 3 ,114864.5,,,
BEGIN DESCRIPTION:
I-45 N. ALLEN E RAMP
Structure ID: W00-34
END DESCRIPTION:
Bridge Culvert--1,0,-1,-1, 0
Deck Dist Width WeirC Skew NumUp NumDn MinLoCord MaxHiCord MaxSubmerge Is_Ogee
10,32,2.6,0, 60, 60, , , .95, 0, 1,1,,
  3386.2  3526.2  3616.2  3666.2  3706.2  3841.1    4040    4160    4270    4390
  4462.2  4522.2  4562.2  4622.2  4642.2  4672.2  4702.2  4712.2  4722.2  4732.2
  4752.2  4762.2  4780.1  4810.1  4825.2 4828.49  4828.6  4850.1  4860.1  4870.1
 4883.61  4883.7  4887.8  4921.6    4944  4967.6  5025.8    5072  5194.7    5224
  5247.5  5269.2  5295.7 5295.79  5295.9  5296.3 5296.41  5312.8  5317.6  5322.8
  5362.8  5382.8  5387.6  5400.5  5402.8  5412.8  5425.8  5540.5  5570.5  5610.5
    47.6    45.8    41.5    41.4    39.1    36.4      34    33.7    35.2    39.5
    39.8    38.7    36.5    34.7    33.5    30.9    30.2    30.8    31.9    33.7
      38    39.6    39.5    36.6   33.82   33.44   36.14   36.14   36.14   36.14
   36.14   36.14   36.14   34.78   34.27   34.75   36.97   38.97   44.72   45.72
    46.3   46.44   47.05   47.05   47.05   47.05   44.35    42.2   42.58      43
    43.4    44.1      44   43.75    43.7      44    43.9    44.8    45.8      49
    47.6    45.8    41.5    41.4    39.1    36.4      34    33.7    35.2    39.5
    39.8    38.7    36.5    34.7    33.5    30.9    30.2    30.8    31.9    33.7
      38    39.6    39.5    36.6   33.81    33.2   33.18    29.2    27.1    24.2
   17.29   30.37   30.37   29.01    28.5   28.98    31.2    33.2   38.95   39.95
   40.53   40.67   41.28   41.28   34.25    34.2   34.19   32.11    31.5   31.83
   34.41   35.69      36    36.2   36.34   36.96   37.75    44.8    45.8      49
  3386.2  3526.2  3616.2  3666.2  3706.2  3841.1    4040    4160    4270    4390
  4462.2  4522.2  4562.2  4622.2  4642.2  4672.2  4702.2  4712.2  4722.2  4732.2
  4752.2  4762.2  4780.1  4810.1  4825.2 4828.49  4828.6  4850.1  4860.1  4870.1
 4883.61  4883.7  4887.8  4921.6    4944  4967.6  5025.8    5072  5194.7    5224
  5247.5  5269.2  5295.7 5295.79  5295.9  5296.3 5296.41  5312.8  5317.6  5322.8
  5362.8  5382.8  5387.6  5400.5  5402.8  5412.8  5425.8  5540.5  5570.5  5610.5
    47.6    45.8    41.5    41.4    39.1    36.4      34    33.7    35.2    39.5
    39.8    38.7    36.5    34.7    33.5    30.9    30.2    30.8    31.9    33.7
      38    39.6    39.5    36.6   33.82   33.44   36.14   36.14   36.14   36.14
   36.14   36.14   36.14   34.78   34.27   34.75   36.97   38.97   44.72   45.72
    46.3   46.44   47.05   47.05   47.05   47.05   44.35    42.2   42.58      43
    43.4    44.1      44   43.75    43.7      44    43.9    44.8    45.8      49
   46.95   45.15   40.85   40.75   38.45   35.75   33.35   33.05   34.55   38.85
   39.15   38.05   35.85   34.05   32.85   30.25   29.55   30.15   31.25   33.05
   37.35   38.95   38.85   35.95   33.16   32.55   32.53   28.55   26.45   23.55
   16.64   29.72   29.72   28.36   27.85   28.33   30.55   32.55    38.3    39.3
   39.88   40.02   40.63   40.63    33.6   33.55   33.54   31.46   30.85   31.18
   33.76   35.04   35.35   35.55   35.69   36.31    37.1   44.15   45.15   48.35
Pier Skew, UpSta & Num, DnSta & Num=  ,4887.5, 2 ,4887.5, 2 , 0 , 0 , 0 ,,
     2.5     2.5
   14.34   31.37
     2.5     2.5
   13.69   30.72
Pier Skew, UpSta & Num, DnSta & Num=  ,4925.1, 2 ,4925.1, 2 , 0 , 0 , 0 ,,
     2.5     2.5
    7.88   29.96
     2.5     2.5
    7.23   29.31
Pier Skew, UpSta & Num, DnSta & Num=  ,4969.9, 2 ,4969.9, 2 , 0 , 0 , 0 ,,
     2.5     2.5
   -6.14   30.12
     2.5     2.5
   -6.79   29.47
Pier Skew, UpSta & Num, DnSta & Num=  ,5020.5, 2 ,5020.5, 2 , 0 , 0 , 0 ,,
     2.5     2.5
   -4.31   32.04
     2.5     2.5
   -4.96   31.39
Pier Skew, UpSta & Num, DnSta & Num=  ,5074.5, 2 ,5074.5, 2 , 0 , 0 , 0 ,,
     2.5     2.5
   10.32   34.37
     2.5     2.5
    9.67   33.72
Pier Skew, UpSta & Num, DnSta & Num=  ,5129.7, 2 ,5129.7, 2 , 0 , 0 , 0 ,,
     2.5     2.5
   20.46   36.93
     2.5     2.5
   19.81   36.28
Pier Skew, UpSta & Num, DnSta & Num=  ,5185.1, 2 ,5185.1, 2 , 0 , 0 , 0 ,,
     2.5     2.5
   21.28   39.58
     2.5     2.5
   20.63   38.93
Pier Skew, UpSta & Num, DnSta & Num=  ,5217.4, 2 ,5217.4, 2 , 0 , 0 , 0 ,,
     2.5     2.5
   25.72   40.76
     2.5     2.5
   25.07   40.11
Pier Skew, UpSta & Num, DnSta & Num=  ,5249.2, 2 ,5249.2, 2 , 0 , 0 , 0 ,,
     2.5     2.5
   27.05   41.55
     2.5     2.5
    26.4    40.9
Pier Skew, UpSta & Num, DnSta & Num=  ,5275.1, 2 ,5275.1, 2 , 0 , 0 , 0 ,,
     2.5     2.5
   30.55   41.84
     2.5     2.5
    29.9   41.19
BR Coef= 1 , 1 , 0 ,1.25, 0 ,,,.8,0,2,0,
WSPro=,,,, 1 ,,,, 0 ,,,, 0 ,,,,-1 ,-1 ,-1 , 0 , 0 , 0 , 0 , 0
BR U #Sta/Elev= 101
  3386.2    47.6  3526.2    45.8  3616.2    41.5  3666.2    41.4  3706.2    39.1
  3841.1    36.4    4040      34    4160    33.7    4270    35.2    4390    39.5
  4462.2    39.8  4522.2    38.7  4562.2    36.5  4622.2    34.7  4642.2    33.5
  4672.2    30.9  4702.2    30.2  4712.2    30.8  4722.2    31.9  4732.2    33.7
  4752.2      38  4762.2    39.6  4780.1    39.5  4810.1    36.6  4825.2   33.81
 4828.49    33.2  4828.6   33.18 4828.71   33.16  4850.1    29.2  4860.1    27.1
  4870.1    24.2 4883.61   17.29  4883.7   17.24  4883.8   17.19  4887.4   15.35
  4887.5   15.35  4887.8   15.35  4888.9   15.34  4889.1   15.34  4910.4   12.82
  4921.6    9.83  4925.1    8.89  4937.7    8.76    4944    2.07  4944.9    1.12
  4958.8   -5.14  4967.6   -4.93  4969.9   -4.87  4980.5   -7.13  4987.3   -8.58
    5002   -6.93  5020.5   -3.05  5020.9    -3.1  5025.8   -3.76    5031   -4.45
  5045.2   -1.94  5055.1    1.29    5072   10.63  5074.5   12.01  5075.2   12.32
  5091.9   19.73  5110.5   22.18  5117.7   21.92  5129.7   21.48  5129.9   21.48
  5164.9   20.66  5171.1   20.52  5184.9   22.43  5185.1   22.46  5194.7   24.75
  5198.9   25.75    5217   26.77  5217.4   26.79    5224   27.06  5247.5   28.03
  5249.2    28.1  5249.6   28.16  5269.2    30.9  5275.1   31.73  5275.2   31.74
  5295.6   34.29  5295.7   34.28 5295.79   34.27  5295.9   34.25    5296   34.24
 5296.19   34.22  5296.3    34.2 5296.41   34.19  5312.8   32.11  5317.6    31.5
  5322.8   31.83  5362.8   34.41  5382.8   35.69  5387.6      36  5400.5    36.2
  5402.8   36.34  5412.8   36.96  5425.8   37.75  5540.5    44.8  5570.5    45.8
  5610.5      49
BR U #Mann= 3
  3386.2      .2  4937.7     .04  5091.9      .2
BR U Banks=4937.7,5091.9
BR D #Sta/Elev= 101
  3386.2   46.95  3526.2   45.15  3616.2   40.85  3666.2   40.75  3706.2   38.45
  3841.1   35.75    4040   33.35    4160   33.05    4270   34.55    4390   38.85
  4462.2   39.15  4522.2   38.05  4562.2   35.85  4622.2   34.05  4642.2   32.85
  4672.2   30.25  4702.2   29.55  4712.2   30.15  4722.2   31.25  4732.2   33.05
  4752.2   37.35  4762.2   38.95  4780.1   38.85  4810.1   35.95  4825.2   33.16
 4828.49   32.55  4828.6   32.53 4828.71   32.51  4850.1   28.55  4860.1   26.45
  4870.1   23.55 4883.61   16.64  4883.7   16.59  4883.8   16.54  4887.4    14.7
  4887.5    14.7  4887.8    14.7  4888.9   14.69  4889.1   14.69  4910.4   12.17
  4921.6    9.18  4925.1    8.24  4937.7    8.11    4944    1.42  4944.9     .47
  4958.8   -5.79  4967.6   -5.58  4969.9   -5.52  4980.5   -7.78  4987.3   -9.23
    5002   -7.58  5020.5    -3.7  5020.9   -3.75  5025.8   -4.41    5031    -5.1
  5045.2   -2.59  5055.1     .64    5072    9.98  5074.5   11.36  5075.2   11.67
  5091.9   19.08  5110.5   21.53  5117.7   21.27  5129.7   20.83  5129.9   20.83
  5164.9   20.01  5171.1   19.87  5184.9   21.78  5185.1   21.81  5194.7    24.1
  5198.9    25.1    5217   26.12  5217.4   26.14    5224   26.41  5247.5   27.38
  5249.2   27.45  5249.6   27.51  5269.2   30.25  5275.1   31.08  5275.2   31.09
  5295.6   33.64  5295.7   33.63 5295.79   33.62  5295.9    33.6    5296   33.59
 5296.19   33.57  5296.3   33.55 5296.41   33.54  5312.8   31.46  5317.6   30.85
  5322.8   31.18  5362.8   33.76  5382.8   35.04  5387.6   35.35  5400.5   35.55
  5402.8   35.69  5412.8   36.31  5425.8    37.1  5540.5   44.15  5570.5   45.15
  5610.5   48.35
BR D #Mann= 3
  3386.2      .2  4937.7     .04  5091.9      .2
BR D Banks=4937.7,5091.9
BC Design=,, 0 ,, 0 ,,,,,,
BC HTab HWMax=49.02

Type RM Length L Ch R = 1 ,114838.5,346.5,346.5,346.5
BEGIN DESCRIPTION:
Downstream Section of Bridge/Culvert/Weir
END DESCRIPTION:
XS GIS Cut Line= 6
      3119037.24     13843913.54      3119354.94     13843469.42
      3119414.31     13842452.81      3119456.26     13842312.89
       3119555.1     13842246.17      3119944.25     13842194.43
#Sta/Elev= 30
  3386.2   46.91  3526.2   45.11  3706.2   38.41    4040   33.31    4270   34.51
  4462.2   39.11  4702.2   29.51  4762.2   38.91  4780.1   38.81  4810.1   35.91
  4850.1   28.51  4870.1   23.51  4887.4   14.66  4925.1     8.2  4937.7    8.07
  4944.9     .43  4958.8   -5.83  4969.9   -5.56  4987.3   -9.27  5020.5   -3.74
    5031   -5.14  5045.2   -2.63  5091.9   19.04  5110.5   21.49  5171.1   19.83
  5198.9   25.06  5249.2   27.41  5295.6    33.6  5317.6   30.81  5610.5   48.31
#Mann= 3 ,-1 , 0
  3386.2      .2       0  4937.7     .04       0  5091.9      .2       0
#XS Ineff= 2 , 0
            4870    30.2    5305            42.3
Permanent Ineff=
       F       F
Bank Sta=4937.7,5091.9
XS Rating Curve= 0
Exp/Cntr=.5,.3