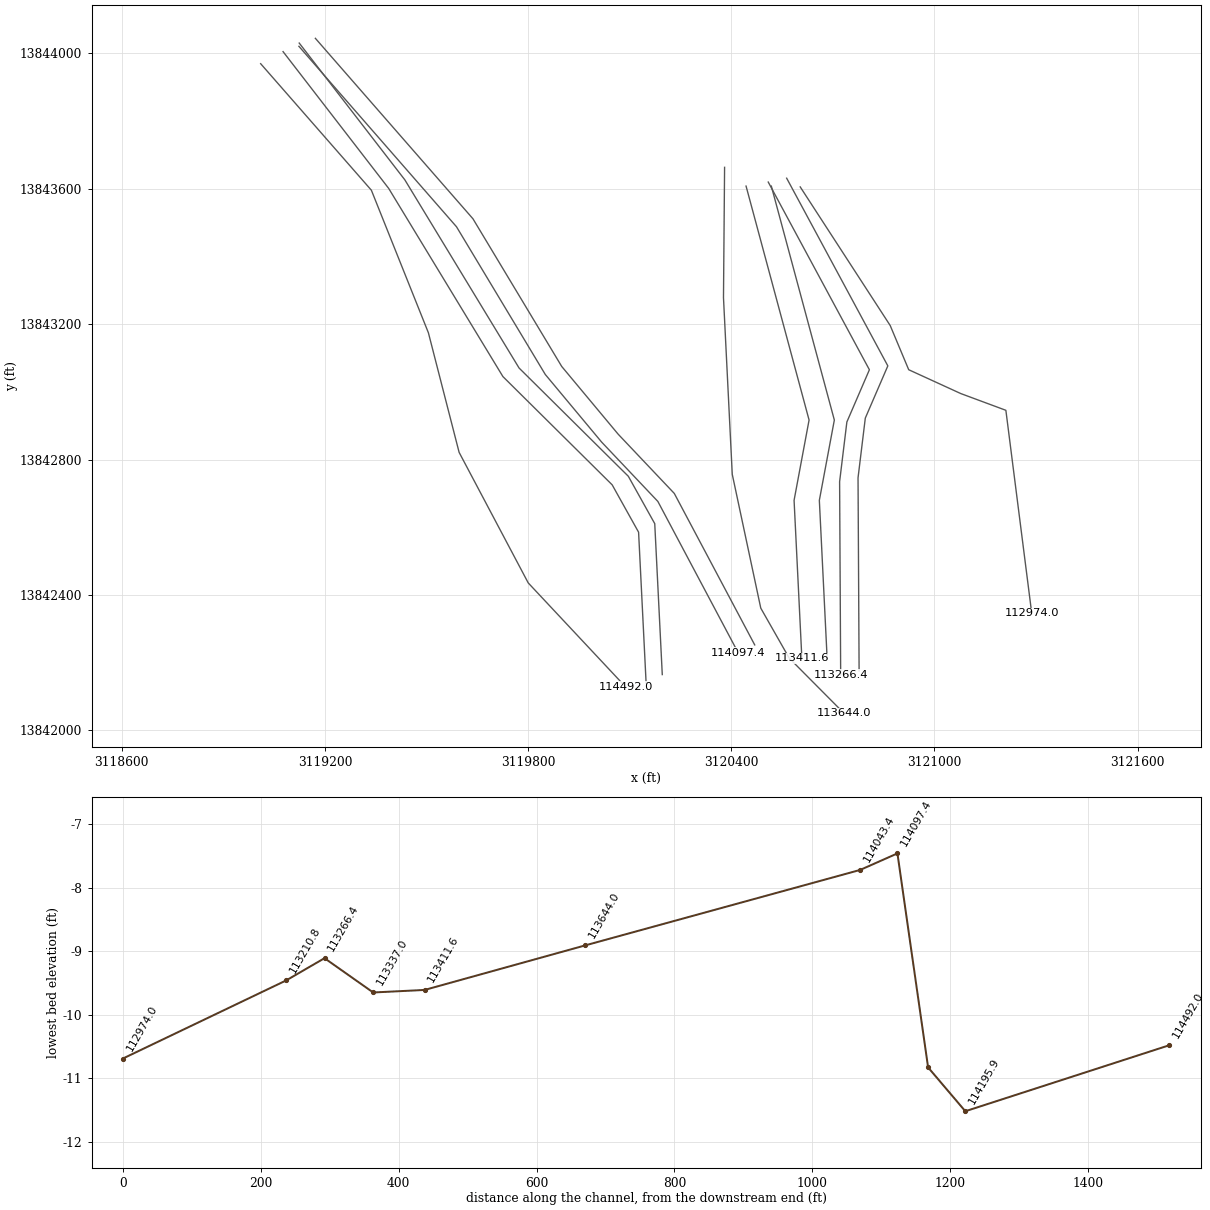
HEC-RAS study W100-00-00.prj: W100-00-00

--- W100-00-00.g01 (geometry) --- (continued)

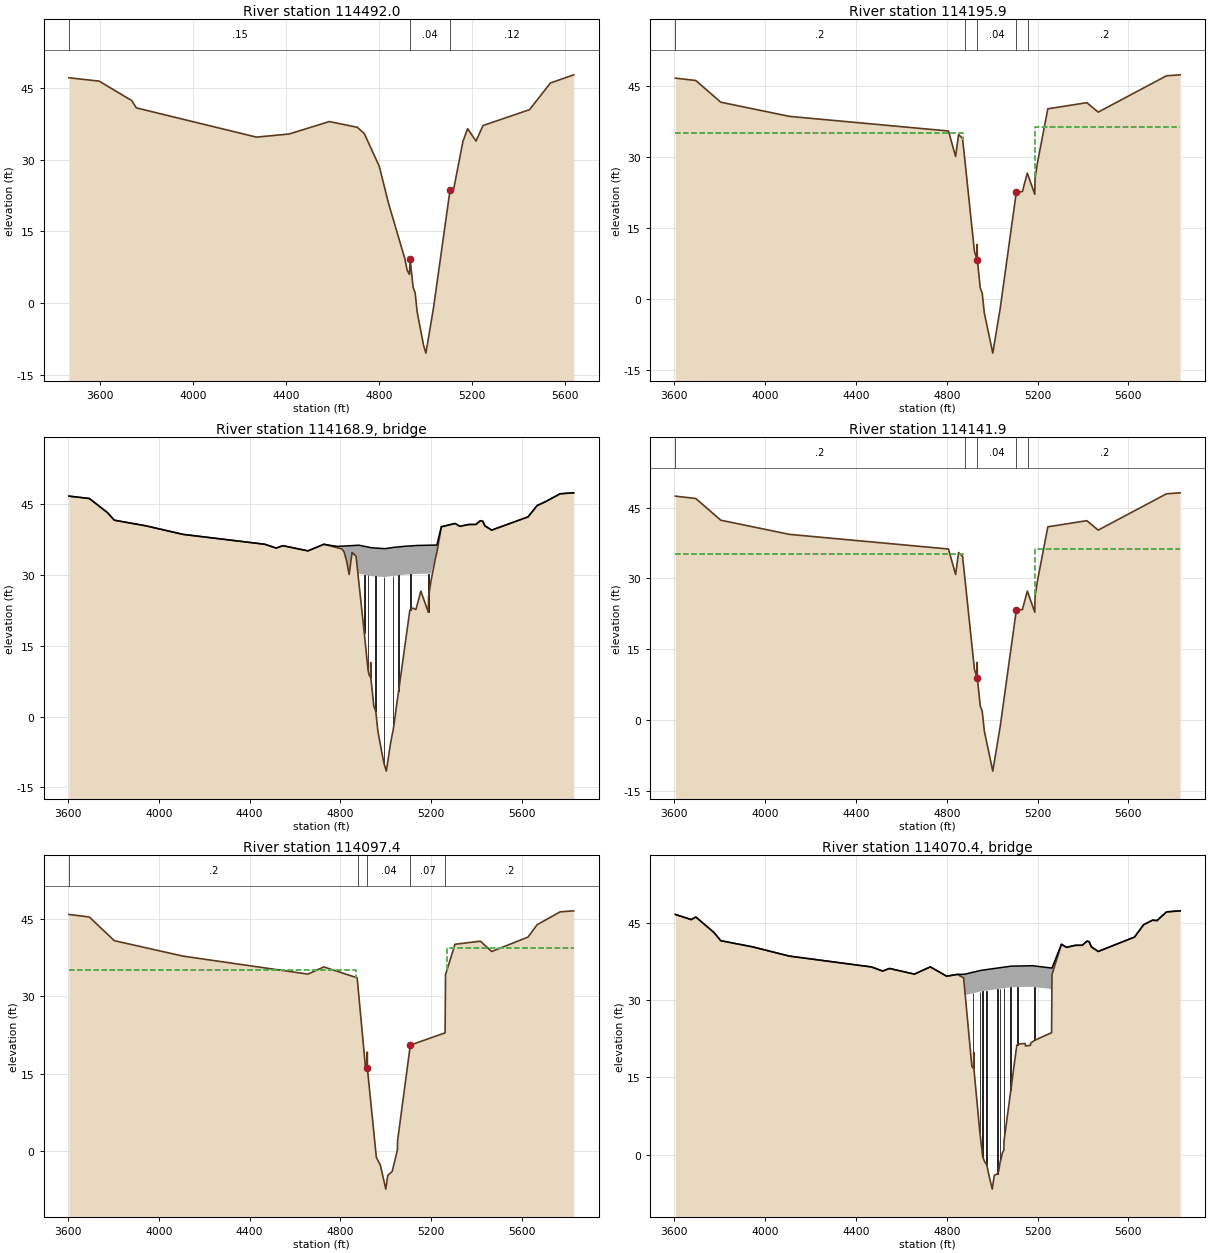
Type RM Length L Ch R = 1 ,114492.0,229.6,296.1,343.1
BEGIN DESCRIPTION:
Cross Section 114492.0-Interpolated
END DESCRIPTION:
XS GIS Cut Line= 6
      3119010.38      13843968.9      3119337.29     13843595.29
      3119505.71     13843174.23       3119596.4     13842821.19
      3119800.45     13842435.76      3120087.58     13842129.17
#Sta/Elev= 30
  3467.4   47.15  3597.4   46.45  3737.4   42.39  3757.4   40.85  4273.9   34.73
  4413.9   35.38  4587.3   37.99  4707.3   36.79  4737.3   35.49  4801.8   28.65
  4841.8   20.87  4911.8     9.3  4921.8    6.87  4931.8    5.99  4934.6    9.17
  4947.4    3.29    4956    2.21  4965.2   -1.96  4992.6   -8.89  5002.5  -10.48
  5035.5     -.9    5106   23.58  5121.8   23.85  5161.8   33.85  5181.8   36.49
    5218   33.91    5248   37.15    5448   40.48    5538   46.06    5638   47.77
#Mann= 3 ,-1 , 0
  3467.4     .15       0  4934.6     .04       0    5106     .12       0
Bank Sta=4934.6,5106
XS Rating Curve= 0
Exp/Cntr=.5,.3

Type RM Length L Ch R = 1 ,114195.9,54,54,54
BEGIN DESCRIPTION:
Upstream Section of Bridge/Culvert/Weir
END DESCRIPTION:
XS GIS Cut Line= 6
      3119076.54     13844004.48      3119388.44     13843600.56
       3119725.7     13843045.01      3120048.32     13842725.33
      3120126.31     13842585.48      3120148.54      13842139.8
#Sta/Elev= 30
  3604.2   46.74  3694.2   46.24  3804.2   41.64  4106.5   38.64  4807.3   35.54
  4838.7   30.14  4851.7   34.79  4869.2   33.99  4879.4   29.42  4921.7   10.01
  4933.4     8.3  4933.7    11.5  4934.6    8.13  4947.4    2.25    4956    1.17
  4965.2      -3  5002.5  -11.52  5035.5   -1.94    5106   22.54    5133   22.72
  5154.6   26.63  5159.2      26  5187.6   22.14  5188.7   25.44  5198.7   28.64
    5245   40.24  5416.9   41.54  5466.8   39.54    5768   47.24    5828   47.44
#Mann= 5 ,-1 , 0
  3604.2      .2       0  4879.4     .07       0  4934.6     .04       0
    5106     .07       0  5159.2      .2       0
#XS Ineff= 2 , 0
            4870    35.2    5190            36.3
Permanent Ineff=
       F       F
Bank Sta=4934.6,5106
XS Rating Curve= 0
Exp/Cntr=.5,.3

Type RM Length L Ch R = 3 ,114168.9,,,
BEGIN DESCRIPTION:
S. CAPITAL STREET
Structure ID: WOO-32
END DESCRIPTION:
Bridge Culvert--1,0,-1,-1, 0
Deck Dist Width WeirC Skew NumUp NumDn MinLoCord MaxHiCord MaxSubmerge Is_Ogee
10,34,2.6,0, 42, 42, , , .95, 0, 1,1,,
  3604.2  3694.2  3774.2  3804.2  3944.2  4106.5  4467.3  4517.3  4547.3  4657.3
  4727.3    4786  4807.3  4817.3  4828.7  4838.7  4851.7  4869.2 4882.11  4882.2
  4937.4  4996.3  5035.5  5090.6  5138.4  5198.7  5218.7    5225    5245    5305
  5326.9  5365.9  5396.9  5416.9  5426.9  5436.8  5466.8  5626.8  5666.8  5706.8
    5768    5828
    46.7    46.2    43.2    41.6    40.4    38.6    36.5    35.7    36.2    35.1
    36.5   36.05   36.11   36.13   36.16   36.19   36.22   36.27    36.3    36.3
   35.76   35.57   35.85    36.1   36.25   36.31   36.33   36.33   40.21   40.91
   40.31    40.7    40.7    41.5    41.4    40.4    39.5    42.3    44.7    45.6
    47.2    47.4
    46.7    46.2    43.2    41.6    40.4    38.6    36.5    35.7    36.2    35.1
    36.5   35.77    35.5    34.8    32.7    30.1   34.75   33.95   28.16   30.28
   29.74   29.55   29.83   30.08   30.23   30.29    33.5    34.7    40.2    40.9
    40.3   40.69    40.7    41.5    41.4    40.4    39.5    42.3    44.7    45.6
    47.2    47.4
  3604.2  3694.2  3774.2  3804.2  3944.2  4106.5  4467.3  4517.3  4547.3  4657.3
  4727.3    4786  4807.3  4817.3  4828.7  4838.7  4851.7  4869.2 4882.11  4882.2
  4937.4  4996.3  5035.5  5090.6  5138.4  5198.7  5218.7    5225    5245    5305
  5326.9  5365.9  5396.9  5416.9  5426.9  5436.8  5466.8  5626.8  5666.8  5706.8
    5768    5828
    46.7    46.2    43.2    41.6    40.4    38.6    36.5    35.7    36.2    35.1
    36.5   36.05   36.11   36.13   36.16   36.19   36.22   36.27    36.3    36.3
   35.76   35.57   35.85    36.1   36.25   36.31   36.33   36.33   40.21   40.91
   40.31    40.7    40.7    41.5    41.4    40.4    39.5    42.3    44.7    45.6
    47.2    47.4
   46.67   46.17   43.17   41.57   40.37   38.57   36.47   35.67   36.17   35.07
   36.47   35.74   35.47   34.77   32.67   30.07   34.72   33.92   28.13   30.25
   29.71   29.52    29.8   30.05    30.2   30.26   33.47   34.67   40.17   40.87
   40.27   40.66   40.67   41.47   41.37   40.37   39.47   42.27   44.67   45.57
   47.17   47.37
Pier Skew, UpSta & Num, DnSta & Num=  ,4905.3, 2 ,4905.3, 2 , 0 , 0 , 0 ,,
     3.5     3.5
   15.93   31.07
     3.5     3.5
    15.9   31.04
Pier Skew, UpSta & Num, DnSta & Num=  ,4921.7, 2 ,4921.7, 2 , 0 , 0 , 0 ,,
     3.5     3.5
    8.54   30.91
     3.5     3.5
    8.51   30.88
Pier Skew, UpSta & Num, DnSta & Num=  ,4956, 2 ,4956, 2 , 0 , 0 , 0 ,,
     3.5     3.5
    -.63   30.69
     3.5     3.5
    -.66   30.66
Pier Skew, UpSta & Num, DnSta & Num=  ,4992.6, 2 ,4992.6, 2 , 0 , 0 , 0 ,,
     3.5     3.5
  -11.25   30.57
     3.5     3.5
  -11.28   30.54
Pier Skew, UpSta & Num, DnSta & Num=  ,5032, 2 ,5032, 2 , 0 , 0 , 0 ,,
       3       3
   -4.35   30.82
       3       3
   -4.38   30.79
Pier Skew, UpSta & Num, DnSta & Num=  ,5056.7, 2 ,5056.7, 2 , 0 , 0 , 0 ,,
     3.5     3.5
    3.79   30.93
     3.5     3.5
    3.76    30.9
Pier Skew, UpSta & Num, DnSta & Num=  ,5108.9, 2 ,5108.9, 2 , 0 , 0 , 0 ,,
       3       3
   21.58   31.14
       3       3
   21.55   31.11
Pier Skew, UpSta & Num, DnSta & Num=  ,5187.6, 2 ,5187.6, 2 , 0 , 0 , 0 ,,
       3       3
    21.3   31.28
       3       3
   21.27   31.25
Abutment Skew #Up #Dn= , 2 , 2
    4882  4926.1
   30.28    8.89
    4882  4926.1
   30.25    8.86
Abutment Skew #Up #Dn= , 2 , 2
  5154.7 5261.49
   26.58   40.39
  5154.7 5261.49
   26.55   40.36
BR Coef= 1 , 1 , 0 ,1.25, 0 ,,,.8,0,2,0,
WSPro=,,,, 1 ,,,, 0 ,,,, 0 ,,,,-1 ,-1 ,-1 , 0 , 0 , 0 , 0 , 0
BR U #Sta/Elev= 89
  3604.2    46.7  3694.2    46.2  3774.2    43.2  3804.2    41.6  3944.2    40.4
  4106.5    38.6  4467.3    36.5  4517.3    35.7  4547.3    36.2  4657.3    35.1
  4727.3    36.5  4737.1   36.38    4786   35.77  4807.3    35.5 4812.69   35.12
  4812.8   35.12 4812.91   35.11  4817.3    34.8  4818.7    34.5  4828.7    32.7
  4838.7    30.1  4851.7   34.75  4851.8   34.74  4869.2   33.95  4879.4   29.38
  4881.9   28.25    4882   28.21 4882.11   28.16  4882.2   28.12  4905.3   17.76
  4921.7    9.97    4926    8.91  4926.1    8.89  4933.4    8.26  4933.7   11.46
  4934.6    8.09  4937.4     6.8  4947.4    2.21    4956    1.13  4957.9     .31
  4965.2   -3.04  4983.3   -7.77  4992.6   -9.97  4996.3  -10.56  5002.5  -11.56
  5020.1   -5.99  5027.5      -4    5032   -3.02  5032.2   -2.96  5035.5   -1.98
    5042      .3  5046.9     2.1  5056.7    5.38  5090.6   17.15    5106    22.5
  5108.9   22.67  5119.5   22.97    5133   22.68  5138.4   23.66 5139.79   23.91
  5139.9   23.93 5140.01   23.95  5154.6   26.59  5154.7   26.58  5159.2   25.96
  5187.6    22.1  5188.7    25.4  5198.7    28.6  5218.7    33.5    5225    34.7
    5245    40.2  5261.2   40.39 5261.29   40.39  5261.4   40.39  5261.5   40.39
    5305    40.9  5326.9    40.3  5365.9   40.69  5366.9    40.7  5396.9    40.7
  5416.9    41.5  5426.9    41.4  5436.8    40.4  5466.8    39.5  5626.8    42.3
  5666.8    44.7  5706.8    45.6    5768    47.2    5828    47.4
BR U #Mann= 5
  3604.2      .2  4879.4     .07  4934.6     .04    5106     .07  5159.2      .2
BR U Banks=4934.6,5106
BR D #Sta/Elev= 89
  3604.2   46.67  3694.2   46.17  3774.2   43.17  3804.2   41.57  3944.2   40.37
  4106.5   38.57  4467.3   36.47  4517.3   35.67  4547.3   36.17  4657.3   35.07
  4727.3   36.47  4737.1   36.35    4786   35.74  4807.3   35.47 4812.69   35.09
  4812.8   35.09 4812.91   35.08  4817.3   34.77  4818.7   34.47  4828.7   32.67
  4838.7   30.07  4851.7   34.72  4851.8   34.71  4869.2   33.92  4879.4   29.35
  4881.9   28.22    4882   28.18 4882.11   28.13  4882.2   28.09  4905.3   17.73
  4921.7    9.94    4926    8.88  4926.1    8.86  4933.4    8.23  4933.7   11.43
  4934.6    8.06  4937.4    6.77  4947.4    2.18    4956     1.1  4957.9     .28
  4965.2   -3.07  4983.3    -7.8  4992.6     -10  4996.3  -10.59  5002.5  -11.59
  5020.1   -6.02  5027.5   -4.03    5032   -3.05  5032.2   -2.99  5035.5   -2.01
    5042     .27  5046.9    2.07  5056.7    5.35  5090.6   17.12    5106   22.47
  5108.9   22.64  5119.5   22.94    5133   22.65  5138.4   23.63 5139.79   23.88
  5139.9    23.9 5140.01   23.92  5154.6   26.56  5154.7   26.55  5159.2   25.93
  5187.6   22.07  5188.7   25.37  5198.7   28.57  5218.7   33.47    5225   34.67
    5245   40.17  5261.2   40.36 5261.29   40.36  5261.4   40.36  5261.5   40.36
    5305   40.87  5326.9   40.27  5365.9   40.66  5366.9   40.67  5396.9   40.67
  5416.9   41.47  5426.9   41.37  5436.8   40.37  5466.8   39.47  5626.8   42.27
  5666.8   44.67  5706.8   45.57    5768   47.17    5828   47.37
BR D #Mann= 5
  3604.2      .2  4879.4     .07  4934.6     .04    5106     .07  5159.2      .2
BR D Banks=4934.6,5106
BC Design=,, 0 ,, 0 ,,,,,,
BC HTab HWMax=47.44

Type RM Length L Ch R = 1 ,114141.9,44.5,44.5,44.5
BEGIN DESCRIPTION:
Downstream Section of Bridge/Culvert/Weir
END DESCRIPTION:
XS GIS Cut Line= 6
      3119124.25     13844029.78      3119436.14     13843625.86
       3119773.4     13843070.31      3120096.02     13842750.63
      3120174.01     13842610.78      3120196.24      13842165.1
#Sta/Elev= 30
  3604.2   47.43  3694.2   46.93  3804.2   42.33  4106.5   39.33  4807.3   36.23
  4838.7   30.83  4851.7   35.48  4869.2   34.68  4879.4   30.11  4921.7    10.7
  4933.4    8.99  4933.7   12.19  4934.6    8.82  4947.4    2.94    4956    1.86
  4965.2   -2.31  5002.5  -10.83  5035.5   -1.25    5106   23.23    5133   23.41
  5154.6   27.32  5159.2   26.69  5187.6   22.83  5188.7   26.13  5198.7   29.33
    5245   40.93  5416.9   42.23  5466.8   40.23    5768   47.93    5828   48.13
#Mann= 5 ,-1 , 0
  3604.2      .2       0  4879.4     .07       0  4934.6     .04       0
    5106     .07       0  5159.2      .2       0
#XS Ineff= 2 , 0
            4870    35.2    5190            36.3
Permanent Ineff=
       F       F
Bank Sta=4934.6,5106
XS Rating Curve= 0
Exp/Cntr=.5,.3

Type RM Length L Ch R = 1 ,114097.4,54,54,54
BEGIN DESCRIPTION:
Upstream Section of Bridge/Culvert/Weir
END DESCRIPTION:
XS GIS Cut Line= 6
      3119123.34     13844020.19      3119588.63      13843487.4
      3119850.78     13843051.27      3120017.16     13842851.62
      3120183.22     13842676.33      3120420.59     13842229.19
#Sta/Elev= 30
  3604.2   45.93  3694.2   45.43  3804.2   40.83  4106.5   37.83  4657.3   34.33
  4727.3   35.73  4874.1   33.61  4879.9   30.85  4910.3    16.4  4918.3   16.06
  4918.6   19.17    4919   16.06  4958.6   -1.29  4976.3   -2.79  5000.2   -7.46
    5009   -4.79  5028.4      -4  5051.4     .14  5052.2    1.98  5108.3   20.54
  5260.7    22.9  5261.5   22.91  5263.3   34.23    5305   40.13  5416.9   40.73
  5466.8   38.73  5626.8   41.53  5666.8   43.93    5768   46.43    5828   46.63
#Mann= 5 ,-1 , 0
  3604.2      .2       0  4879.9     .07       0    4919     .04       0
  5108.3     .07       0  5260.7      .2       0
#XS Ineff= 2 , 0
            4870    35.1    5270            39.5
Permanent Ineff=
       F       F
Bank Sta=4919,5108.3
XS Rating Curve= 0
Exp/Cntr=.5,.3

Type RM Length L Ch R = 3 ,114070.4,,,
BEGIN DESCRIPTION:
N. CAPITAL STREET
Structure ID: WOO-31
END DESCRIPTION:
Bridge Culvert--1,0,-1,-1, 0
Deck Dist Width WeirC Skew NumUp NumDn MinLoCord MaxHiCord MaxSubmerge Is_Ogee
10,34,2.6,0, 38, 38, , , .95, 0, 1,1,,
  3604.2  3674.2  3694.2  3774.2  3804.2  3944.2  4106.5  4467.3  4517.3  4547.3
  4657.3  4727.3  4799.3  4846.7  4874.1 4882.71  4882.8  4950.5  5082.2  5176.7
 5262.09  5262.2  5263.3    5305  5326.9  5366.9  5396.9  5416.9  5426.9  5436.8
  5466.8  5626.8  5666.8  5706.8  5726.8    5728    5768    5828
    46.7    45.7    46.2    43.2    41.6    40.4    38.6    36.5    35.7    36.2
    35.1   36.51    34.7   35.05   35.06   35.12   35.12   35.83   36.64   36.73
   36.28   36.28   36.28   40.91   40.31   40.71   40.71   41.51   41.41   40.41
   39.51    42.3    44.7    45.6    45.5    45.6    47.2    47.4
   46.69   45.69   46.19   43.19   41.59   40.39   38.59   36.49   35.69   36.19
   35.09   36.49   34.68   35.03   34.37   30.28   31.03   31.74   32.55   32.64
   32.19   28.07   34.99   40.89   40.29   40.69   40.69   41.49   41.39   40.39
   39.49   42.29   44.69   45.59   45.49   45.59   47.19   47.39
  3604.2  3674.2  3694.2  3774.2  3804.2  3944.2  4106.5  4467.3  4517.3  4547.3
  4657.3  4727.3  4799.3  4846.7  4874.1 4882.71  4882.8  4950.5  5082.2  5176.7
 5262.09  5262.2  5263.3    5305  5326.9  5366.9  5396.9  5416.9  5426.9  5436.8
  5466.8  5626.8  5666.8  5706.8  5726.8    5728    5768    5828
    46.7    45.7    46.2    43.2    41.6    40.4    38.6    36.5    35.7    36.2
    35.1   36.51    34.7   35.05   35.06   35.12   35.12   35.83   36.64   36.73
   36.28   36.28   36.28   40.91   40.31   40.71   40.71   41.51   41.41   40.41
   39.51    42.3    44.7    45.6    45.5    45.6    47.2    47.4
    45.7    44.7    45.2    42.2    40.6    39.4    37.6    35.5    34.7    35.2
    34.1    35.5   33.69   34.04   33.38   29.29   30.04   30.75   31.56   31.65
    31.2   27.08      34    39.9    39.3    39.7    39.7    40.5    40.4    39.4
    38.5    41.3    43.7    44.6    44.5    44.6    46.2    46.4
Pier Skew, UpSta & Num, DnSta & Num=  ,4915.5, 2 ,4915.5, 2 , 0 , 0 , 0 ,,
     3.5     3.5
   15.84   32.39
     3.5     3.5
   14.85    31.4
Pier Skew, UpSta & Num, DnSta & Num=  ,4946.1, 2 ,4946.1, 2 , 0 , 0 , 0 ,,
     3.5     3.5
    2.43   32.71
     3.5     3.5
    1.44   31.72
Pier Skew, UpSta & Num, DnSta & Num=  ,4958.6, 2 ,4958.6, 2 , 0 , 0 , 0 ,,
       3       3
   -1.68    32.8
       3       3
   -2.67   31.81
Pier Skew, UpSta & Num, DnSta & Num=  ,4976.3, 2 ,4976.3, 2 , 0 , 0 , 0 ,,
     3.5     3.5
    -3.4   32.91
     3.5     3.5
   -4.39   31.92
Pier Skew, UpSta & Num, DnSta & Num=  ,5021.9, 2 ,5021.9, 2 , 0 , 0 , 0 ,,
     3.5     3.5
   -4.76   33.19
     3.5     3.5
   -5.75    32.2
Pier Skew, UpSta & Num, DnSta & Num=  ,5034.6, 2 ,5034.6, 2 , 0 , 0 , 0 ,,
       3       3
   -2.91   33.27
       3       3
    -3.9   32.28
Pier Skew, UpSta & Num, DnSta & Num=  ,5052.2, 2 ,5052.2, 2 , 0 , 0 , 0 ,,
     3.5     3.5
    -.18   33.37
     3.5     3.5
   -1.17   32.38
Pier Skew, UpSta & Num, DnSta & Num=  ,5082.2, 2 ,5082.2, 2 , 0 , 0 , 0 ,,
     3.5     3.5
      11   33.56
     3.5     3.5
   10.01   32.57
Pier Skew, UpSta & Num, DnSta & Num=  ,5110.7, 2 ,5110.7, 2 , 0 , 0 , 0 ,,
       3       3
   20.32   33.58
       3       3
   19.33   32.59
Pier Skew, UpSta & Num, DnSta & Num=  ,5186.9, 2 ,5186.9, 2 , 0 , 0 , 0 ,,
       3       3
   21.18    33.6
       3       3
   20.19   32.61
Abutment Skew #Up #Dn= , 2 , 2
  4882.6  4910.3
   31.03   17.16
  4882.6  4910.3
   30.04   16.17
BR Coef= 1 , 1 , 0 ,1.25, 0 ,,,.8,0,2,0,
WSPro=,,,, 1 ,,,, 0 ,,,, 0 ,,,,-1 ,-1 ,-1 , 0 , 0 , 0 , 0 , 0
BR U #Sta/Elev= 91
  3604.2   46.69  3674.2   45.69  3694.2   46.19  3774.2   43.19  3804.2   41.59
  3944.2   40.39  4106.5   38.59  4467.3   36.49  4517.3   35.69  4547.3   36.19
  4657.3   35.09  4720.7   36.36  4727.3   36.49  4740.7   36.15  4750.7    35.9
  4799.3   34.68  4805.2   34.72 4821.49   34.84  4821.6   34.84 4821.71   34.85
  4846.7   35.03  4874.1   34.37  4879.9   31.61  4882.5   30.38  4882.6   30.33
 4882.71   30.28  4882.8   30.23  4910.2   17.21  4910.3   17.16  4915.5   16.86
  4918.3   16.82  4918.6   19.93    4919   16.82  4946.1    4.12  4950.5    2.39
  4950.6    2.35  4954.9     .93  4955.9     .33  4958.6    -.53    4967   -1.38
  4976.3   -2.03  4986.4   -4.17  5000.2    -6.7    5009   -4.03  5021.9   -3.72
  5028.4   -3.24  5034.6   -1.48  5038.9    -.87    5044     .26  5051.4      .9
  5051.8     2.5  5052.2    2.74  5082.2   12.57  5084.4   13.31  5108.3    21.3
  5110.7   21.35  5120.6   21.53  5145.1   21.61  5146.3   21.14  5168.8   21.25
    5169   21.67  5176.7   21.91  5186.9   22.23  5241.3   23.31  5260.7   23.66
  5261.4   23.67  5261.5   23.67    5262   26.81 5262.09   27.38  5262.2   28.07
  5262.3    28.7  5263.3   34.99    5305   40.89 5311.19   40.72  5311.3   40.72
 5311.41   40.71  5326.9   40.29  5366.9   40.69  5396.9   40.69  5416.9   41.49
  5426.9   41.39  5436.8   40.39  5466.8   39.49  5516.8   40.37  5626.8   42.29
  5666.8   44.69  5706.8   45.59  5726.8   45.49    5728   45.59    5768   47.19
    5828   47.39
BR U #Mann= 5
  3604.2      .2  4879.9     .07    4919     .04  5108.3     .07  5260.7      .2
BR U Banks=4919,5108.3
BR D #Sta/Elev= 91
  3604.2    45.7  3674.2    44.7  3694.2    45.2  3774.2    42.2  3804.2    40.6
  3944.2    39.4  4106.5    37.6  4467.3    35.5  4517.3    34.7  4547.3    35.2
  4657.3    34.1  4720.7   35.37  4727.3    35.5  4740.7   35.16  4750.7   34.91
  4799.3   33.69  4805.2   33.73 4821.49   33.85  4821.6   33.85 4821.71   33.86
  4846.7   34.04  4874.1   33.38  4879.9   30.62  4882.5   29.39  4882.6   29.34
 4882.71   29.29  4882.8   29.24  4910.2   16.22  4910.3   16.17  4915.5   15.87
  4918.3   15.83  4918.6   18.94    4919   15.83  4946.1    3.13  4950.5     1.4
  4950.6    1.36  4954.9    -.06  4955.9    -.66  4958.6   -1.52    4967   -2.37
  4976.3   -3.02  4986.4   -5.16  5000.2   -7.69    5009   -5.02  5021.9   -4.71
  5028.4   -4.23  5034.6   -2.47  5038.9   -1.86    5044    -.73  5051.4    -.09
  5051.8    1.51  5052.2    1.75  5082.2   11.58  5084.4   12.32  5108.3   20.31
  5110.7   20.36  5120.6   20.54  5145.1   20.62  5146.3   20.15  5168.8   20.26
    5169   20.68  5176.7   20.92  5186.9   21.24  5241.3   22.32  5260.7   22.67
  5261.4   22.68  5261.5   22.68    5262   25.82 5262.09   26.39  5262.2   27.08
  5262.3   27.71  5263.3      34    5305    39.9 5311.19   39.73  5311.3   39.73
 5311.41   39.72  5326.9    39.3  5366.9    39.7  5396.9    39.7  5416.9    40.5
  5426.9    40.4  5436.8    39.4  5466.8    38.5  5516.8   39.38  5626.8    41.3
  5666.8    43.7  5706.8    44.6  5726.8    44.5    5728    44.6    5768    46.2
    5828    46.4
BR D #Mann= 5
  3604.2      .2  4879.9     .07    4919     .04  5108.3     .07  5260.7      .2
BR D Banks=4919,5108.3
BC Design=,, 0 ,, 0 ,,,,,,
BC HTab HWMax=46.63

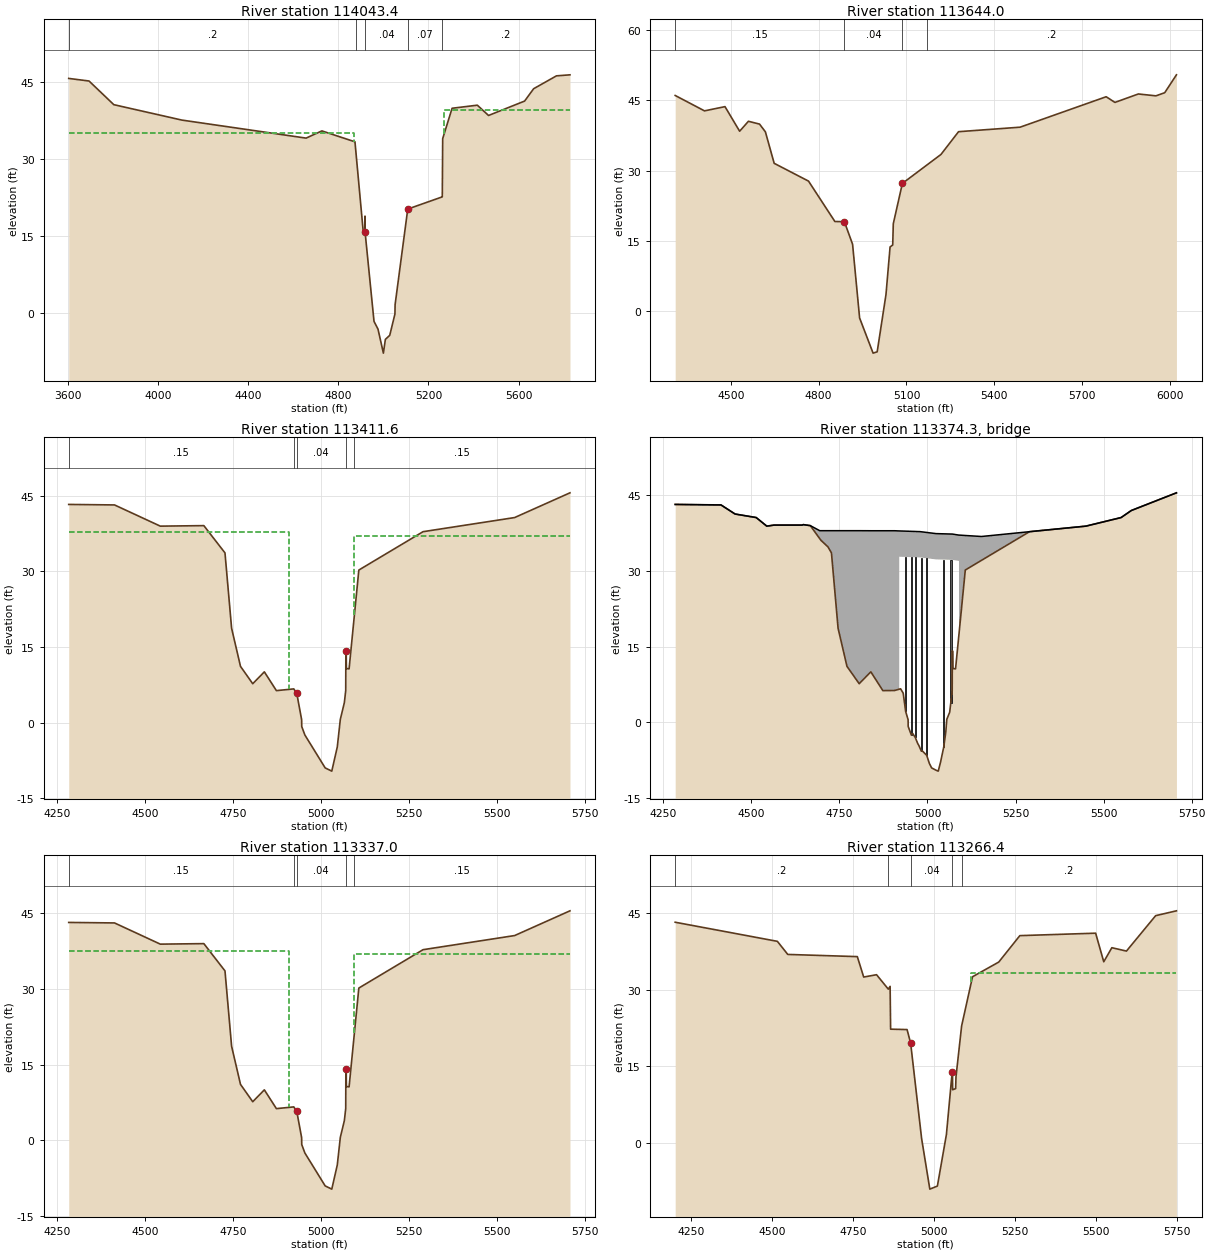
Type RM Length L Ch R = 1 ,114043.4,399.4,399.4,399.4
BEGIN DESCRIPTION:
Downstream Section of Bridge/Culvert/Weir
END DESCRIPTION:
XS GIS Cut Line= 6
      3119171.93     13844043.76      3119637.21     13843510.98
      3119899.36     13843074.85      3120065.74      13842875.2
       3120231.8     13842699.91      3120469.17     13842252.76
#Sta/Elev= 30
  3604.2   45.67  3694.2   45.17  3804.2   40.57  4106.5   37.57  4657.3   34.07
  4727.3   35.47  4874.1   33.35  4879.9   30.59  4910.3   16.14  4918.3    15.8
  4918.6   18.91    4919    15.8  4958.6   -1.55  4976.3   -3.05  5000.2   -7.72
    5009   -5.05  5028.4   -4.26  5051.4    -.12  5052.2    1.72  5108.3   20.28
  5260.7   22.64  5261.5   22.65  5263.3   33.97    5305   39.87  5416.9   40.47
  5466.8   38.47  5626.8   41.27  5666.8   43.67    5768   46.17    5828   46.37
#Mann= 5 ,-1 , 0
  3604.2      .2       0  4879.9     .07       0    4919     .04       0
  5108.3     .07       0  5260.7      .2       0
#XS Ineff= 2 , 0
            4870      35    5270            39.5
Permanent Ineff=
       F       F
Bank Sta=4919,5108.3
XS Rating Curve= 0
Exp/Cntr=.5,.3

Type RM Length L Ch R = 1 ,113644.0,248.6,232.4,226.6
BEGIN DESCRIPTION:
Cross Section 113644.0-Interpolated
END DESCRIPTION:
XS GIS Cut Line= 6
      3120380.22      13843662.9      3120376.98     13843277.88
      3120402.89     13842756.41       3120487.1     13842361.26
      3120571.07     13842213.69      3120733.18     13842050.55
#Sta/Elev= 30
  4310.5      46  4410.5   42.72  4480.5   43.62  4530.5   38.38  4560.5    40.5
  4598.4    39.9  4618.4   38.25  4648.4   31.54  4765.6   27.75  4855.6   19.14
    4888    19.1    4916    14.3    4940   -1.42    4986   -8.91    5000   -8.63
    5030    3.56    5044   13.72    5053   14.13    5055   18.67    5086   27.26
  5170.5   31.22  5217.7   33.43  5277.7   38.28  5487.7   39.24  5781.7   45.73
  5811.5   44.52  5891.5   46.32  5951.5   45.92  5981.5   46.59  6021.5    50.4
#Mann= 4 ,-1 , 0
  4310.5     .15       0    4888     .04       0    5086      .2       0
  5170.5      .2       0
Bank Sta=4888,5086
XS Rating Curve= 0
Exp/Cntr=.5,.3

Type RM Length L Ch R = 1 ,113411.6,74.6,74.6,74.6
BEGIN DESCRIPTION:
Upstream Section of Bridge/Culvert/Weir
END DESCRIPTION:
XS GIS Cut Line= 4
      3120443.64     13843607.47      3120629.71     13842916.69
      3120585.43     13842679.66      3120608.38     13842213.75
#Sta/Elev= 30
  4283.9   43.23  4413.9   43.13  4543.9   38.93  4667.5   39.03  4727.5   33.63
 4746.32   18.69 4771.52   11.15 4806.24    7.71 4839.28   10.06 4873.44    6.34
  4922.8    6.68 4931.18    5.84 4945.12     .58 4945.34    -.76  4954.3   -2.45
 5011.93   -8.97 5030.69   -9.61 5046.31   -4.83 5054.94     .65 5066.36    3.95
 5070.28    6.36 5070.67   14.26 5071.62    14.1 5072.18   10.72 5079.81   10.65
  5094.1   20.75  5107.5   30.23  5289.8   37.83  5549.8   40.63  5706.9   45.53
#Mann= 5 ,-1 , 0
  4283.9     .15       0  4922.8     .04       0 4931.18     .04       0
 5070.67     .04       0  5094.1     .15       0
#XS Ineff= 2 , 0
            4910    37.8    5095              37
Permanent Ineff=
       F       F
Bank Sta=4931.18,5070.67
XS Rating Curve= 0
Exp/Cntr=.5,.3

Type RM Length L Ch R = 3 ,113374.3,,,
BEGIN DESCRIPTION:
TEXAS AVENUE       Skew Angle 56 Degrees
Structure ID: WOO-30
END DESCRIPTION:
Bridge Culvert--1,0,-1,-1, 0
Deck Dist Width WeirC Skew NumUp NumDn MinLoCord MaxHiCord MaxSubmerge Is_Ogee
10,54.6,2.6,0, 33, 33, , , .95, 0, 1,1,,
  4283.9  4413.9  4453.9  4513.9  4543.9  4563.9  4643.9  4647.5  4667.5 4694.24
  4697.5  4717.5  4727.5 4746.32 4771.52 4806.24 4839.28 4873.44 4906.48 4919.89
 4919.98 4979.62 5024.42 5070.95 5089.56 5089.67  5107.5 5153.44  5289.8  5449.8
  5549.8  5578.9  5706.9
    43.2    43.1    41.3    40.6    38.9    39.1    39.1    39.2      39      38
      38      38      38      38      38      38   37.99   37.99   37.99   37.95
   37.95   37.81   37.42   37.33   37.12   37.13   37.05   36.85    37.8    38.9
    40.6      42    45.5
    43.2    43.1    41.3    40.6    38.9    39.1    39.1    39.2      39   36.42
    36.1    34.8    33.6   18.66   11.12    7.68   10.03    6.31    6.33    6.59
   32.84    32.7   32.31   32.22   32.01   17.59    30.2   32.12    37.8    38.9
    40.6      42    45.5
  4283.9  4413.9  4453.9  4513.9  4543.9  4563.9  4643.9  4647.5  4667.5 4694.24
  4697.5  4717.5  4727.5 4746.32 4771.52 4806.24 4839.28 4873.44 4906.48 4919.89
 4919.98 4979.62 5024.42 5070.95 5089.56 5089.67  5107.5 5153.44  5289.8  5449.8
  5549.8  5578.9  5706.9
    43.2    43.1    41.3    40.6    38.9    39.1    39.1    39.2      39      38
      38      38      38      38      38      38   37.99   37.99   37.99   37.95
   37.95   37.81   37.42   37.33   37.12   37.13   37.05   36.85    37.8    38.9
    40.6      42    45.5
   43.11   43.01   41.21   40.51   38.81   39.01   39.01   39.11   38.91   36.33
   36.01   34.71   33.51   18.57   11.03    7.59    9.94    6.22    6.24     6.5
   32.75   32.61   32.22   32.13   31.92    17.5   30.11   32.03   37.71   38.81
   40.51   41.91   45.41
Pier Skew, UpSta & Num, DnSta & Num=  ,4938.2, 2 ,4938.2, 2 , 0 , 0 , 0 ,,
       4       4
      .7    33.8
       4       4
     .61   33.71
Pier Skew, UpSta & Num, DnSta & Num=  ,4954.3, 2 ,4954.3, 2 , 0 , 0 , 0 ,,
       4       4
    -3.3   33.76
       4       4
   -3.39   33.67
Pier Skew, UpSta & Num, DnSta & Num=  ,4965.5, 2 ,4965.5, 2 , 0 , 0 , 0 ,,
       4       4
   -4.32   33.74
       4       4
   -4.41   33.65
Pier Skew, UpSta & Num, DnSta & Num=  ,4982.9, 2 ,4982.9, 2 , 0 , 0 , 0 ,,
       4       4
   -6.64   33.69
       4       4
   -6.73    33.6
Pier Skew, UpSta & Num, DnSta & Num=  ,4997.9, 2 ,4997.9, 2 , 0 , 0 , 0 ,,
       4       4
   -7.92   33.56
       4       4
   -8.01   33.47
Pier Skew, UpSta & Num, DnSta & Num=  ,5046.3, 2 ,5046.3, 2 , 0 , 0 , 0 ,,
       4       4
   -6.52   33.27
       4       4
   -6.61   33.18
Pier Skew, UpSta & Num, DnSta & Num=  ,5066.4, 2 ,5066.4, 2 , 0 , 0 , 0 ,,
       4       4
    1.74   33.24
       4       4
    1.65   33.15
Abutment Skew #Up #Dn= , 2 , 2
 4919.78 4923.78
   32.84    6.67
 4919.78 4923.78
   32.75    6.58
Abutment Skew #Up #Dn= , 2 , 2
 5079.91 5089.76
   10.69   32.01
 5079.91 5089.76
    10.6   31.92
BR Coef= 1 , 1 , 0 ,1.25, 0 ,,,.8,-1,2,0,
WSPro=,,,, 1 ,,,, 0 ,,,, 0 ,,,,-1 ,-1 ,-1 , 0 , 0 , 0 , 0 , 0
BR U #Sta/Elev= 75
  4283.9    43.2  4413.9    43.1  4453.9    41.3  4513.9    40.6  4543.9    38.9
  4563.9    39.1  4643.9    39.1  4647.5    39.2  4667.5      39 4694.24   36.42
  4697.5    36.1  4717.5    34.8  4727.5    33.6 4746.32   18.66 4771.52   11.12
 4806.24    7.68 4839.28   10.03 4873.44    6.31 4906.48    6.33 4919.34    6.58
 4919.42    6.58 4919.55    6.59 4919.66    6.59 4919.76    6.59 4919.89    6.59
 4919.98     6.6  4922.8    6.65 4923.68    6.67 4923.78    6.67 4931.18    5.81
 4938.23    2.17 4945.12     .55 4945.34    -.79  4954.3   -2.48 4957.83   -2.16
  4965.5   -2.97 4972.39   -4.16 4975.86   -4.59 4979.62   -5.19 4982.86    -5.7
 4985.38   -5.63 4997.87    -6.5  5005.6   -8.14 5011.93      -9 5023.52   -9.43
 5024.42   -9.46 5030.69   -9.64 5037.18   -7.88 5046.31   -4.86 5052.08    -1.9
 5054.94     .62 5063.17    2.03 5066.36    3.92 5070.28    6.33 5070.67   14.23
 5070.95   14.18 5071.62   14.07 5072.18   10.69 5079.81   10.62 5079.91   10.69
 5084.63   14.03 5084.74   14.11 5084.85   14.18 5089.51   17.48 5089.56   17.51
 5089.67   17.59 5089.77   17.66  5094.1   20.72  5107.5    30.2 5153.44   32.12
  5289.8    37.8  5449.8    38.9  5549.8    40.6  5578.9      42  5706.9    45.5
BR U #Mann= 5
  4283.9     .15  4922.8     .04 4931.18     .04 5070.67     .04  5094.1     .15
BR U Banks=4931.18,5070.67
BR D #Sta/Elev= 75
  4283.9   43.11  4413.9   43.01  4453.9   41.21  4513.9   40.51  4543.9   38.81
  4563.9   39.01  4643.9   39.01  4647.5   39.11  4667.5   38.91 4694.24   36.33
  4697.5   36.01  4717.5   34.71  4727.5   33.51 4746.32   18.57 4771.52   11.03
 4806.24    7.59 4839.28    9.94 4873.44    6.22 4906.48    6.24 4919.34    6.49
 4919.42    6.49 4919.55     6.5 4919.66     6.5 4919.76     6.5 4919.89     6.5
 4919.98    6.51  4922.8    6.56 4923.68    6.58 4923.78    6.58 4931.18    5.72
 4938.23    2.08 4945.12     .46 4945.34    -.88  4954.3   -2.57 4957.83   -2.25
  4965.5   -3.06 4972.39   -4.25 4975.86   -4.68 4979.62   -5.28 4982.86   -5.79
 4985.38   -5.72 4997.87   -6.59  5005.6   -8.23 5011.93   -9.09 5023.52   -9.52
 5024.42   -9.55 5030.69   -9.73 5037.18   -7.97 5046.31   -4.95 5052.08   -1.99
 5054.94     .53 5063.17    1.94 5066.36    3.83 5070.28    6.24 5070.67   14.14
 5070.95   14.09 5071.62   13.98 5072.18    10.6 5079.81   10.53 5079.91    10.6
 5084.63   13.94 5084.74   14.02 5084.85   14.09 5089.51   17.39 5089.56   17.42
 5089.67    17.5 5089.77   17.57  5094.1   20.63  5107.5   30.11 5153.44   32.03
  5289.8   37.71  5449.8   38.81  5549.8   40.51  5578.9   41.91  5706.9   45.41
BR D #Mann= 5
  4283.9     .15  4922.8     .04 4931.18     .04 5070.67     .04  5094.1     .15
BR D Banks=4931.18,5070.67
BC Design=,, 0 ,, 0 ,,,,,,
BC HTab HWMax=45.53

Type RM Length L Ch R = 1 ,113337.0,70.6,70.6,70.6
BEGIN DESCRIPTION:
Downstream Section of Bridge/Culvert/Weir
END DESCRIPTION:
XS GIS Cut Line= 4
      3120518.24     13843607.47      3120704.31     13842916.69
      3120660.03     13842679.66      3120682.98     13842213.75
#Sta/Elev= 30
  4283.9   43.19  4413.9   43.09  4543.9   38.89  4667.5   38.99  4727.5   33.59
 4746.32   18.65 4771.52   11.11 4806.24    7.67 4839.28   10.02 4873.44     6.3
  4922.8    6.64 4931.18     5.8 4945.12     .54 4945.34     -.8  4954.3   -2.49
 5011.93   -9.01 5030.69   -9.65 5046.31   -4.87 5054.94     .61 5066.36    3.91
 5070.28    6.32 5070.67   14.22 5071.62   14.06 5072.18   10.68 5079.81   10.61
  5094.1   20.71  5107.5   30.19  5289.8   37.79  5549.8   40.59  5706.9   45.49
#Mann= 5 ,-1 , 0
  4283.9     .15       0  4922.8     .04       0 4931.18     .04       0
 5070.67     .04       0  5094.1     .15       0
#XS Ineff= 2 , 0
            4910    37.5    5095              37
Permanent Ineff=
       F       F
Bank Sta=4931.18,5070.67
XS Rating Curve= 0
Exp/Cntr=.5,.3

Type RM Length L Ch R = 1 ,113266.4,55.6,55.6,55.6
BEGIN DESCRIPTION:
Upstream Section of Bridge/Culvert/Weir
END DESCRIPTION:
XS GIS Cut Line= 5
      3120509.12     13843619.39      3120807.81     13843065.16
      3120741.32       13842911.      3120719.86      13842734.6
        3120723.     13842164.49
#Sta/Elev= 30
  4201.8   43.28  4516.8   39.53  4548.9   36.96 4763.28   36.53 4782.96   32.52
 4822.55   32.98  4858.9   30.14 4864.38   30.69 4865.94   22.29 4916.67   22.21
 4927.71   19.52 4961.49     .82  4986.8   -9.11 5010.13   -8.51 5037.93    1.61
 5055.86   13.95 5056.69   13.91  5057.1    10.4 5066.38   10.62 5067.48   12.93
  5084.8   22.91 5118.44   32.58  5199.3   35.46  5264.3   40.65    5498   41.13
    5523   35.52    5548   38.28    5593   37.62    5683   44.57  5747.1   45.52
#Mann= 5 ,-1 , 0
  4201.8      .2       0  4858.9     .12       0 4927.71     .04       0
 5055.86      .1       0  5084.8      .2       0
#XS Ineff= 2 , 0
            4765    36.1    5115            33.3
Permanent Ineff=
       F       F
Bank Sta=4927.71,5055.86
XS Rating Curve= 0
Exp/Cntr=.5,.3

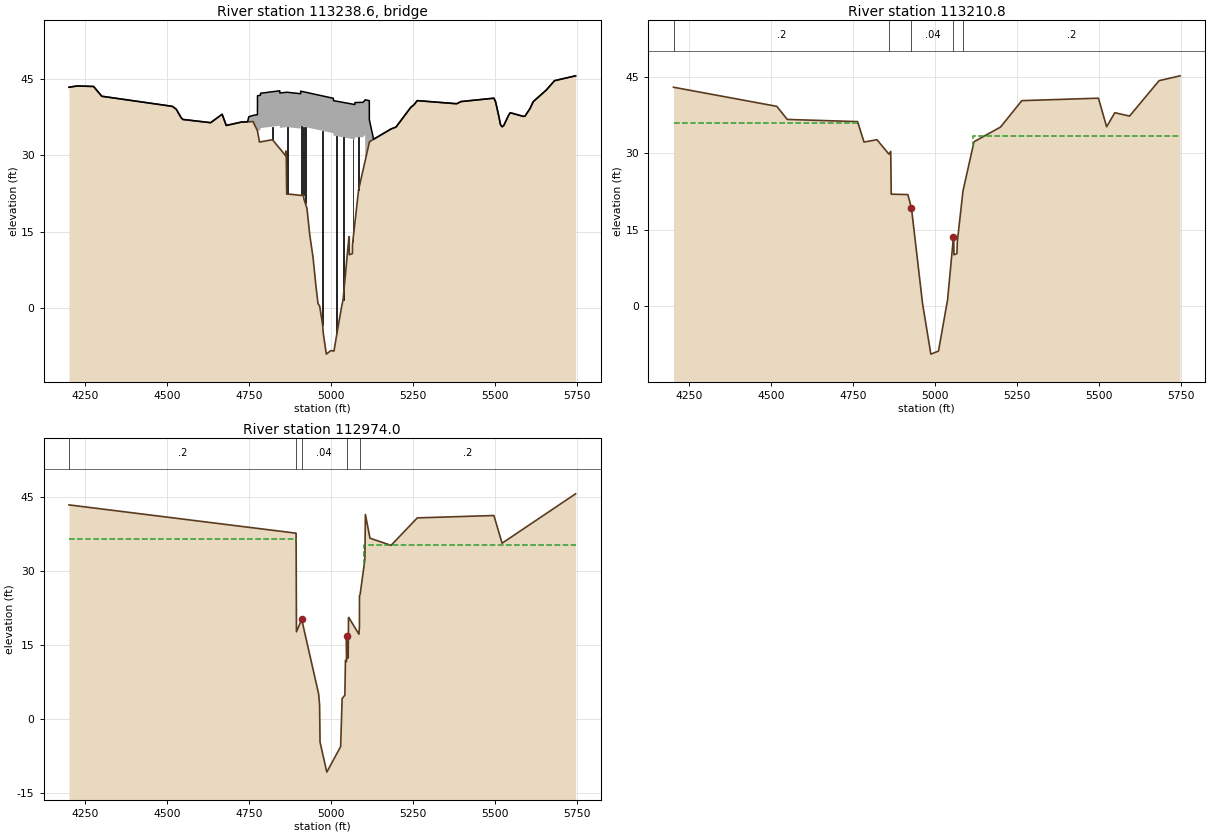
Type RM Length L Ch R = 3 ,113238.6,,,
BEGIN DESCRIPTION:
BAGBY        Skew Angle 34 Degrees
Structure ID: W00-29
END DESCRIPTION:
Bridge Culvert--1,0,-1,-1, 0
Deck Dist Width WeirC Skew NumUp NumDn MinLoCord MaxHiCord MaxSubmerge Is_Ogee
10,35.6,2.6,0, 58, 58, , , .95, 0, 1,1,,
  4201.8  4226.8  4276.8  4301.8  4516.8  4528.9  4543.9  4548.9  4633.9  4668.9
 4681.53 4727.84 4746.44 4750.42 4763.28 4776.69  4776.8 4785.86 4786.11 4844.79
 4845.12 4866.37 4908.53  4908.7  5008.3 5008.72 5073.79 5074.29 5099.18 5105.28
 5105.39 5105.49 5117.93 5118.03 5118.44 5130.97  5184.3  5199.3  5244.3  5254.3
  5264.3  5384.3    5398    5498    5503    5513    5518    5523    5528    5543
    5548    5588    5593    5608    5618    5658    5683  5747.1
   43.36   43.61   43.51   41.59   39.61   39.05   37.38   37.04    36.4   38.05
   35.86   36.52   36.58   37.58   37.83   37.98   41.68   41.78   42.18   42.66
   42.23   42.38   42.09   42.59   41.19   40.73   39.96   40.36    40.4   40.89
    40.9    40.9   40.72   37.02   36.88   33.15   35.17   35.54    39.4   39.92
   40.73   40.12   40.55   41.21   40.53   37.66   36.04    35.6   35.84   37.88
   38.36   37.63    37.7   39.16   40.53   42.82   44.65    45.6
   43.36   43.61   43.51   41.59   39.61   39.05   37.38   37.04    36.4   38.05
   35.86   36.52   36.57   36.58   36.61   34.83   34.83   34.93   35.33   35.81
   35.38   35.53   35.24   35.74   34.34   33.88   33.11   33.51   33.55   34.04
   28.95   28.98   32.52   32.54   32.66   33.14   35.17   35.54    39.4   39.92
   40.73   40.12   40.55   41.21   40.53   37.66   36.04    35.6   35.84   37.88
   38.36   37.63    37.7   39.16   40.53   42.82   44.65    45.6
  4201.8  4226.8  4276.8  4301.8  4516.8  4528.9  4543.9  4548.9  4633.9  4668.9
 4681.53 4727.84 4746.44 4750.42 4763.28 4776.69  4776.8 4785.86 4786.11 4844.79
 4845.12 4866.37 4908.53  4908.7  5008.3 5008.72 5073.79 5074.29 5099.18 5105.28
 5105.39 5105.49 5117.93 5118.03 5118.44 5130.97  5184.3  5199.3  5244.3  5254.3
  5264.3  5384.3    5398    5498    5503    5513    5518    5523    5528    5543
    5548    5588    5593    5608    5618    5658    5683  5747.1
   43.36   43.61   43.51   41.59   39.61   39.05   37.38   37.04    36.4   38.05
   35.86   36.52   36.58   37.58   37.83   37.98   41.68   41.78   42.18   42.66
   42.23   42.38   42.09   42.59   41.19   40.73   39.96   40.36    40.4   40.89
    40.9    40.9   40.72   37.02   36.88   33.15   35.17   35.54    39.4   39.92
   40.73   40.12   40.55   41.21   40.53   37.66   36.04    35.6   35.84   37.88
   38.36   37.63    37.7   39.16   40.53   42.82   44.65    45.6
   42.98   43.23   43.13   41.21   39.23   38.67      37   36.66   36.02   37.67
   35.48   36.14   36.19    36.2   36.23   34.45   34.45   34.55   34.95   35.43
      35   35.15   34.86   35.36   33.96    33.5   32.73   33.13   33.17   33.66
   28.57    28.6   32.14   32.16   32.28   32.76   34.79   35.16   39.02   39.54
   40.35   39.74   40.17   40.83   40.15   37.28   35.66   35.22   35.46    37.5
   37.98   37.25   37.32   38.78   40.15   42.44   44.27   45.22
Pier Skew, UpSta & Num, DnSta & Num=  ,4822.5, 2 ,4822.5, 2 , 0 , 0 , 0 ,,
       3       3
   31.94   36.64
       3       3
   31.56   36.26
Pier Skew, UpSta & Num, DnSta & Num=  ,4868.4, 2 ,4868.4, 2 , 0 , 0 , 0 ,,
       3       3
   21.39   36.53
       3       3
   21.01   36.15
Pier Skew, UpSta & Num, DnSta & Num=  ,4912.5, 2 ,4912.5, 2 , 0 , 0 , 0 ,,
       3       3
   21.12    36.7
       3       3
   20.74   36.32
Pier Skew, UpSta & Num, DnSta & Num=  ,4916.7, 2 ,4916.7, 2 , 0 , 0 , 0 ,,
       3       3
   20.62   36.64
       3       3
   20.24   36.26
Pier Skew, UpSta & Num, DnSta & Num=  ,4922.9, 2 ,4922.9, 2 , 0 , 0 , 0 ,,
       3       3
   19.25   36.55
       3       3
   18.87   36.17
Pier Skew, UpSta & Num, DnSta & Num=  ,4975.4, 2 ,4975.4, 2 , 0 , 0 , 0 ,,
       3       3
   -5.57   35.78
       3       3
   -5.95    35.4
Pier Skew, UpSta & Num, DnSta & Num=  ,5019.3, 2 ,5019.3, 2 , 0 , 0 , 0 ,,
       3       3
   -6.52   34.78
       3       3
    -6.9    34.4
Pier Skew, UpSta & Num, DnSta & Num=  ,5037.9, 2 ,5037.9, 2 , 0 , 0 , 0 ,,
       3       3
     .22   34.55
       3       3
    -.16   34.17
Pier Skew, UpSta & Num, DnSta & Num=  ,5067.5, 2 ,5067.5, 2 , 0 , 0 , 0 ,,
     1.5     1.5
   11.47    34.2
     1.5     1.5
   11.09   33.82
Pier Skew, UpSta & Num, DnSta & Num=  ,5085.2, 2 ,5085.2, 2 , 0 , 0 , 0 ,,
     1.5     1.5
   21.76   34.53
     1.5     1.5
   21.38   34.15
Abutment Skew #Up #Dn= , 2 , 2
 4759.02 4866.04
    36.6   22.37
 4759.02 4866.04
   36.22   21.99
Abutment Skew #Up #Dn= , 2 , 2
 5066.57 5105.48
   12.35   34.04
 5066.57 5105.48
   11.97   33.66
BR Coef= 1 , 1 , 0 ,1.25, 0 ,,,.8,-1,2,0,
WSPro=,,,, 1 ,,,, 0 ,,,, 0 ,,,,-1 ,-1 ,-1 , 0 , 0 , 0 , 0 , 0
BR U #Sta/Elev= 104
  4201.8   43.36  4226.8   43.61  4276.8   43.51  4301.8   41.59  4516.8   39.61
  4518.9   39.54  4528.9   39.05  4543.9   37.38  4548.9   37.04  4633.9    36.4
  4668.9   38.05 4681.53   35.86 4681.61   35.86 4727.84   36.52 4746.44   36.57
 4750.42   36.58 4759.02    36.6 4759.13    36.6 4759.22    36.6 4763.28   36.61
 4776.56   34.84 4776.69   34.79  4776.8   34.76  4776.9   34.72 4782.96    32.6
 4785.86   32.63 4786.11   32.64 4822.55   33.06 4844.79   31.32 4845.12    31.3
  4858.9   30.22 4862.97    29.9 4863.13   30.84 4864.38   30.77 4865.94   22.37
 4866.04   22.37 4866.37   22.38 4868.45   22.41 4908.53   22.14  4908.7   22.14
 4912.52   22.11 4916.67   22.29 4918.74   21.36 4927.71    19.6 4936.34   14.34
 4941.82   11.93 4946.38    9.92 4955.01     4.4 4961.49      .9 4966.63     .37
 4975.43   -3.24 4977.18   -4.79 4981.99   -6.91  4986.8   -9.03 5000.17   -8.34
  5008.3   -8.41 5008.72   -8.42 5010.13   -8.43 5019.16   -4.98 5033.37     .25
 5037.93    1.69 5055.86   14.03 5056.69   13.99  5057.1   10.48 5066.38    10.7
 5066.47   12.28 5066.57   12.35 5067.48   13.01 5073.79   16.65 5074.29   16.93
  5084.8   22.99 5085.16    23.2 5099.18   27.19 5105.28   28.92 5105.39   28.95
 5105.49   28.98 5117.53    32.4 5117.82   32.48 5117.93   32.52 5118.03   32.54
 5118.44   32.66 5130.97   33.14  5184.3   35.17  5199.3   35.54  5244.3    39.4
  5254.3   39.92  5264.3   40.73  5384.3   40.12    5398   40.55    5498   41.21
    5503   40.53    5513   37.66    5518   36.04    5523    35.6    5528   35.84
    5543   37.88    5548   38.36    5588   37.63    5593    37.7    5608   39.16
    5618   40.53    5658   42.82    5683   44.65  5747.1    45.6
BR U #Mann= 5
  4201.8      .2  4858.9     .12 4927.71     .04 5055.86      .1  5084.8      .2
BR U Banks=4927.71,5055.86
BR D #Sta/Elev= 104
  4201.8   42.98  4226.8   43.23  4276.8   43.13  4301.8   41.21  4516.8   39.23
  4518.9   39.16  4528.9   38.67  4543.9      37  4548.9   36.66  4633.9   36.02
  4668.9   37.67 4681.53   35.48 4681.61   35.48 4727.84   36.14 4746.44   36.19
 4750.42    36.2 4759.02   36.22 4759.13   36.22 4759.22   36.22 4763.28   36.23
 4776.56   34.46 4776.69   34.41  4776.8   34.38  4776.9   34.34 4782.96   32.22
 4785.86   32.25 4786.11   32.26 4822.55   32.68 4844.79   30.94 4845.12   30.92
  4858.9   29.84 4862.97   29.52 4863.13   30.46 4864.38   30.39 4865.94   21.99
 4866.04   21.99 4866.37      22 4868.45   22.03 4908.53   21.76  4908.7   21.76
 4912.52   21.73 4916.67   21.91 4918.74   20.98 4927.71   19.22 4936.34   13.96
 4941.82   11.55 4946.38    9.54 4955.01    4.02 4961.49     .52 4966.63    -.01
 4975.43   -3.62 4977.18   -5.17 4981.99   -7.29  4986.8   -9.41 5000.17   -8.72
  5008.3   -8.79 5008.72    -8.8 5010.13   -8.81 5019.16   -5.36 5033.37    -.13
 5037.93    1.31 5055.86   13.65 5056.69   13.61  5057.1    10.1 5066.38   10.32
 5066.47    11.9 5066.57   11.97 5067.48   12.63 5073.79   16.27 5074.29   16.55
  5084.8   22.61 5085.16   22.82 5099.18   26.81 5105.28   28.54 5105.39   28.57
 5105.49    28.6 5117.53   32.02 5117.82    32.1 5117.93   32.14 5118.03   32.16
 5118.44   32.28 5130.97   32.76  5184.3   34.79  5199.3   35.16  5244.3   39.02
  5254.3   39.54  5264.3   40.35  5384.3   39.74    5398   40.17    5498   40.83
    5503   40.15    5513   37.28    5518   35.66    5523   35.22    5528   35.46
    5543    37.5    5548   37.98    5588   37.25    5593   37.32    5608   38.78
    5618   40.15    5658   42.44    5683   44.27  5747.1   45.22
BR D #Mann= 5
  4201.8      .2  4858.9     .12 4927.71     .04 5055.86      .1  5084.8      .2
BR D Banks=4927.71,5055.86
BC Design=,, 0 ,, 0 ,,,,,,
BC HTab HWMax=45.52

Type RM Length L Ch R = 1 ,113210.8,236.8,236.8,236.8
BEGIN DESCRIPTION:
Downstream Section of Bridge/Culvert/Weir
END DESCRIPTION:
XS GIS Cut Line= 5
      3120563.53     13843630.82      3120862.23      13843076.6
      3120795.74     13842922.44      3120774.28     13842746.04
      3120777.42     13842175.92
#Sta/Elev= 30
  4201.8   42.93  4516.8   39.18  4548.9   36.61 4763.28   36.18 4782.96   32.17
 4822.55   32.63  4858.9   29.79 4864.38   30.34 4865.94   21.94 4916.67   21.86
 4927.71   19.17 4961.49     .47  4986.8   -9.46 5010.13   -8.86 5037.93    1.26
 5055.86    13.6 5056.69   13.56  5057.1   10.05 5066.38   10.27 5067.48   12.58
  5084.8   22.56 5118.44   32.23  5199.3   35.11  5264.3    40.3    5498   40.78
    5523   35.17    5548   37.93    5593   37.27    5683   44.22  5747.1   45.17
#Mann= 5 ,-1 , 0
  4201.8      .2       0  4858.9     .12       0 4927.71     .04       0
 5055.86      .1       0  5084.8      .2       0
#XS Ineff= 2 , 0
            4765    35.9    5115            33.3
Permanent Ineff=
       F       F
Bank Sta=4927.71,5055.86
XS Rating Curve= 0
Exp/Cntr=.5,.3

Type RM Length L Ch R = 1 ,112974.0,58.2,58.2,58.2
BEGIN DESCRIPTION:
Upstream Section of Bridge/Culvert/Weir
END DESCRIPTION:
XS GIS Cut Line= 6
      3120603.55     13843605.07      3120869.31     13843195.66
       3120923.9     13843065.25      3121077.72     13842994.83
       3121210.8     13842945.45       3121287.2     13842345.65
#Sta/Elev= 30
  4201.8   43.41  4894.6   37.68 4895.69   17.73  4911.7   20.23 4963.34    5.15
 4966.23    2.98 4967.63   -4.62  4988.3  -10.69  5030.5   -5.51 5035.02    4.19
 5043.37    4.89 5045.08   11.94 5048.28   11.67 5048.44   16.82 5049.45   12.32
 5053.51   12.44 5054.44   20.49  5055.3   20.62 5086.27   17.23 5087.75   18.66
 5087.91   24.99  5089.8   25.24 5104.44   32.37 5105.98   41.48 5119.96   36.67
  5184.3   35.22  5264.3   40.78    5498   41.26    5523   35.65  5747.1   45.65
#Mann= 5 ,-1 , 0
  4201.8      .2       0  4894.6     .08       0  4911.7     .04       0
 5048.44     .08       0  5089.8      .2       0
#XS Ineff= 2 , 0
          4894.7    36.6    5102            35.3
Permanent Ineff=
       F       F
Bank Sta=4911.7,5048.44
XS Rating Curve= 0
Exp/Cntr=.5,.3