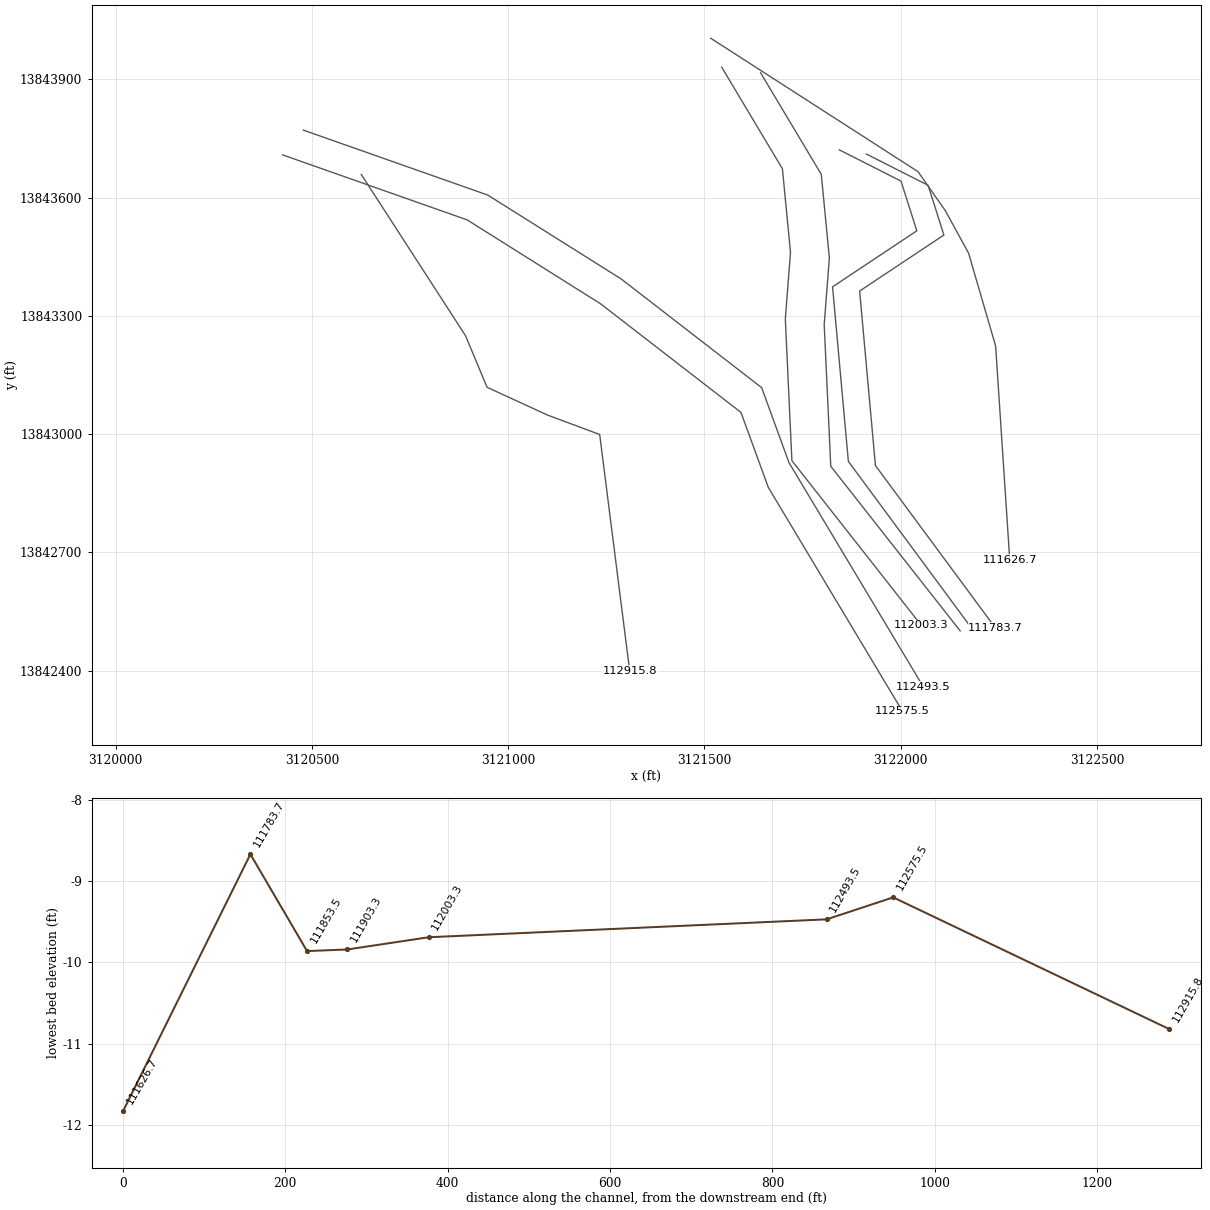
HEC-RAS study W100-00-00.prj: W100-00-00

--- W100-00-00.g01 (geometry) --- (continued)

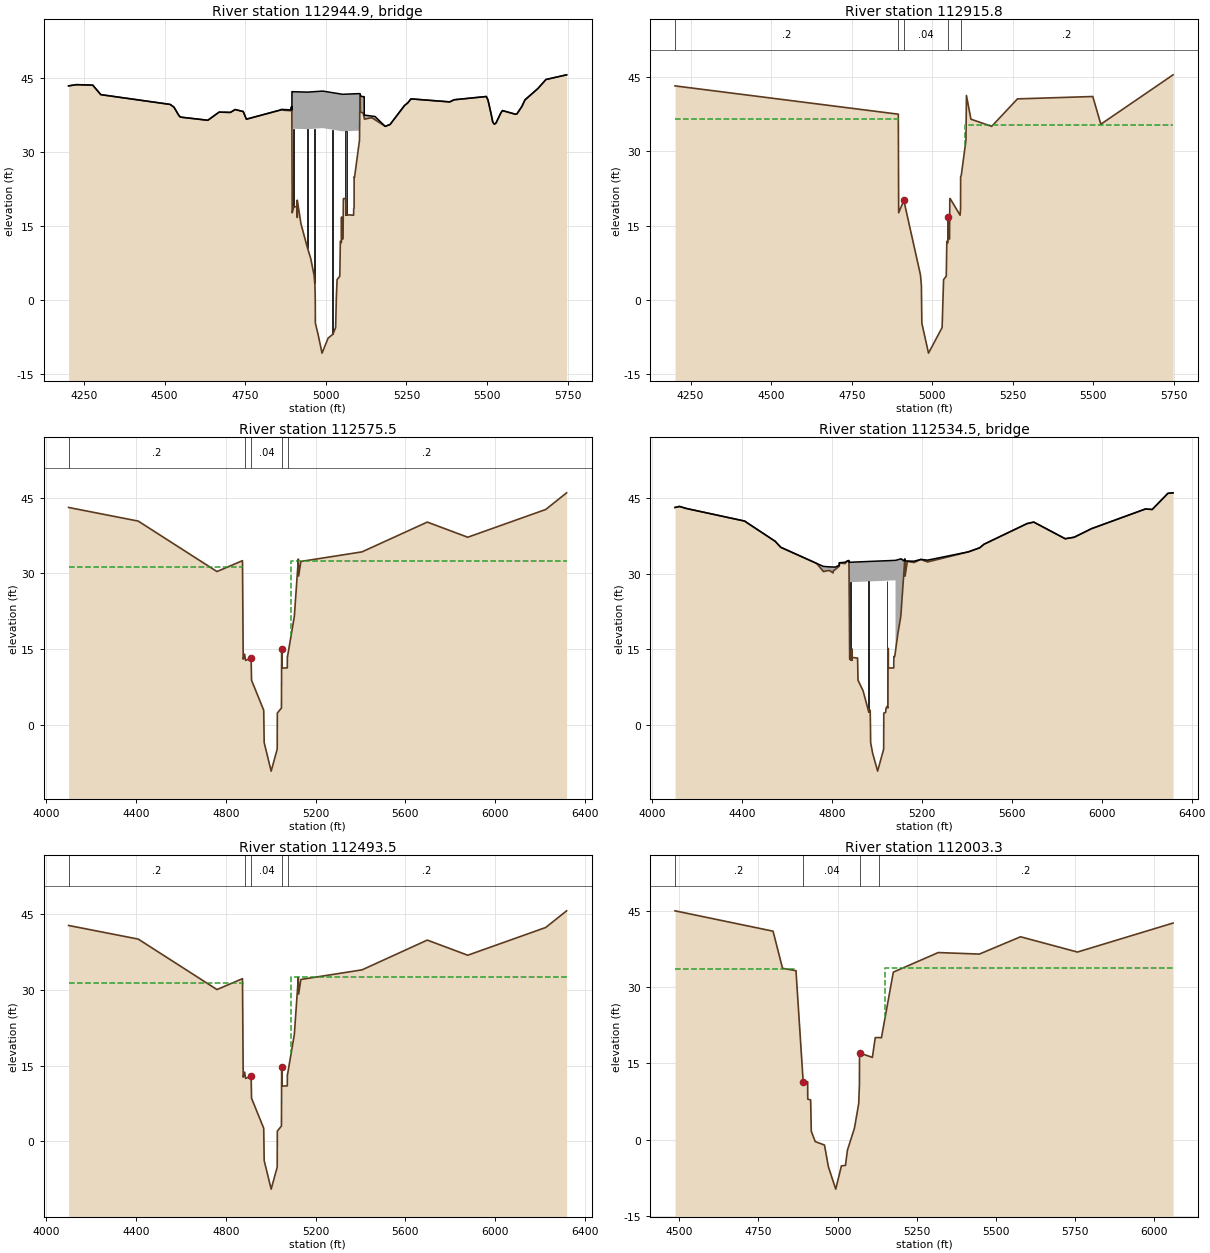
Type RM Length L Ch R = 3 ,112944.9,,,
BEGIN DESCRIPTION:
PRAIRIE      Skew Angle 38 degrees
Structure ID: WOO-28
END DESCRIPTION:
Bridge Culvert--1,0,-1,-1, 0
Deck Dist Width WeirC Skew NumUp NumDn MinLoCord MaxHiCord MaxSubmerge Is_Ogee
10,38.2,2.6,0, 60, 60, , , .95, 0, 1,1,,
  4201.8  4226.8  4276.8  4301.8  4516.8  4528.9  4543.9  4548.9  4633.9  4668.9
  4703.9  4718.6  4743.6  4753.6 4859.21  4862.1  4891.5 4892.13 4894.52  4894.6
 4894.78 4894.89 4895.01 4943.61 4990.64 5051.79 5104.44 5105.98 5106.14 5106.86
 5106.94 5108.97 5116.22 5119.16 5119.27 5119.96 5142.97 5152.57  5184.3  5199.3
  5244.3  5254.3  5264.3  5384.3    5398    5498    5503    5513    5518    5523
    5528    5543    5548    5588    5593    5608    5618    5658    5683  5747.1
   43.36   43.61   43.51   41.59   39.61   39.05   37.38   37.04    36.4   38.05
   37.99   38.57   38.17   36.62   38.48   38.61    38.5   39.01    39.1   38.49
   38.49   42.19   42.19    42.1   42.31   41.66    41.8    41.8    41.8   41.66
   41.64   41.25   41.19   41.16   37.46   37.45   37.25   37.17   35.17   35.54
    39.4   39.92   40.73   40.12   40.55   41.21   40.53   37.66   36.04    35.6
   35.84   37.88   38.36   37.63    37.7   39.16   40.53   42.82   44.65    45.6
   43.36   43.61   43.51   41.59   39.61   39.05   37.38   37.04    36.4   38.05
   37.99   38.57   38.17   36.62   38.47   38.46   38.34      39   39.09   37.63
   34.33   32.32   34.69    34.6   34.81   34.16    34.3   41.43   41.43   41.42
   38.09   38.04   37.86   36.89   36.85   36.62   36.93   36.51   35.17   35.54
    39.4   39.92   40.73   40.12   40.55   41.21   40.53   37.66   36.04    35.6
   35.84   37.88   38.36   37.63    37.7   39.16   40.53   42.82   44.65    45.6
  4201.8  4226.8  4276.8  4301.8  4516.8  4528.9  4543.9  4548.9  4633.9  4668.9
  4703.9  4718.6  4743.6  4753.6 4859.21  4862.1  4891.5 4892.13 4894.52  4894.6
 4894.78 4894.89 4895.01 4943.61 4990.64 5051.79 5104.44 5105.98 5106.14 5106.86
 5106.94 5108.97 5116.22 5119.16 5119.27 5119.96 5142.97 5152.57  5184.3  5199.3
  5244.3  5254.3  5264.3  5384.3    5398    5498    5503    5513    5518    5523
    5528    5543    5548    5588    5593    5608    5618    5658    5683  5747.1
   43.36   43.61   43.51   41.59   39.61   39.05   37.38   37.04    36.4   38.05
   37.99   38.57   38.17   36.62   38.48   38.61    38.5   39.01    39.1   38.49
   38.49   42.19   42.19    42.1   42.31   41.66    41.8    41.8    41.8   41.66
   41.64   41.25   41.19   41.16   37.46   37.45   37.25   37.17   35.17   35.54
    39.4   39.92   40.73   40.12   40.55   41.21   40.53   37.66   36.04    35.6
   35.84   37.88   38.36   37.63    37.7   39.16   40.53   42.82   44.65    45.6
   43.23   43.48   43.38   41.46   39.48   38.92   37.25   36.91   36.27   37.92
   37.86   38.44   38.04   36.49   38.34   38.33   38.21   38.87   38.96    37.5
    34.2   32.19   34.56   34.47   34.68   34.03   34.17    41.3    41.3   41.29
   37.96   37.91   37.73   36.76   36.72   36.49    36.8   36.38   35.04   35.41
   39.27   39.79    40.6   39.99   40.42   41.08    40.4   37.53   35.91   35.47
   35.71   37.75   38.23    37.5   37.57   39.03    40.4   42.69   44.52   45.47
Pier Skew, UpSta & Num, DnSta & Num=  ,4900.7, 2 ,4900.7, 2 , 0 , 0 , 0 ,,
       3       3
   17.56   35.68
       3       3
   17.43   35.55
Pier Skew, UpSta & Num, DnSta & Num=  ,4942.7, 2 ,4942.7, 2 , 0 , 0 , 0 ,,
       3       3
    9.32   35.61
       3       3
    9.19   35.48
Pier Skew, UpSta & Num, DnSta & Num=  ,4965.7, 2 ,4965.7, 2 , 0 , 0 , 0 ,,
       3       3
    -.56   35.71
       3       3
    -.69   35.58
Pier Skew, UpSta & Num, DnSta & Num=  ,5022, 2 ,5022, 2 , 0 , 0 , 0 ,,
       3       3
   -7.99    35.5
       3       3
   -8.12   35.37
Pier Skew, UpSta & Num, DnSta & Num=  ,5063.1, 2 ,5063.1, 2 , 0 , 0 , 0 ,,
     4.5     4.5
   16.27    35.2
     4.5     4.5
   16.14   35.07
Abutment Skew #Up #Dn= , 2 , 2
 5089.15 5106.23
   24.87   41.43
 5089.15 5106.23
   24.74    41.3
BR Coef= 1 , 1 , 0 ,1.25, 0 ,,,.8,0,2,0,
WSPro=,,,, 1 ,,,, 0 ,,,, 0 ,,,,-1 ,-1 ,-1 , 0 , 0 , 0 , 0 , 0
BR U #Sta/Elev= 111
  4201.8   43.36  4226.8   43.61  4276.8   43.51  4301.8   41.59  4516.8   39.61
  4518.9   39.54  4528.9   39.05  4543.9   37.38  4548.9   37.04  4633.9    36.4
  4668.9   38.05  4703.9   37.99  4718.6   38.57  4743.6   38.17  4753.6   36.62
 4850.55   38.32 4858.35   38.45 4859.21   38.47  4862.1   38.46  4891.5   38.34
 4892.13      39 4894.52   39.09  4894.6   37.63 4894.72   35.43 4894.78   34.33
 4894.89   32.32 4895.01   30.12  4895.1   28.48 4895.69   17.68 4895.79   17.71
 4900.71   18.94 4905.39   18.91 4905.46   18.91 4910.61   18.88 4910.69   20.17
 4911.47   16.72  4911.7   20.18 4922.86   15.45 4942.75   10.63 4943.61   10.45
 4953.12    8.44 4963.34     5.1 4965.68    3.45 4966.23    2.93 4967.24     .28
 4967.63   -4.67 4975.51   -6.81  4988.3  -10.74 4990.64  -10.36 5007.18    -7.7
    5022   -6.91  5030.5   -5.56 5032.68     .54 5035.02    4.14 5043.37    4.84
 5045.08   11.89 5048.28   11.62 5048.44   16.77  5049.2   16.81 5049.45   12.27
 5051.79   12.34 5053.51   12.39 5054.44   20.44  5055.3   20.57 5061.62   20.55
  5063.1   17.28 5086.27   17.18  5086.5   18.47 5087.75   18.61 5087.91   24.94
 5089.05   24.82 5089.15   24.87  5089.8   25.19 5104.44   32.32 5105.98   41.43
 5106.03   41.43 5106.14   41.43 5106.24   41.43 5106.86   41.42 5106.94   38.09
 5108.97   38.04 5116.22   37.86 5119.05   36.92 5119.16   36.89 5119.27   36.85
 5119.96   36.62 5142.97   36.93 5143.05   36.91 5152.57   36.51  5184.3   35.17
  5199.3   35.54  5244.3    39.4  5254.3   39.92  5264.3   40.73  5384.3   40.12
    5398   40.55    5498   41.21    5503   40.53    5513   37.66    5518   36.04
    5523    35.6    5528   35.84    5543   37.88    5548   38.36    5588   37.63
    5593    37.7    5608   39.16    5618   40.53    5658   42.82    5683   44.65
  5747.1    45.6
BR U #Mann= 5
  4201.8      .2  4894.6     .08  4911.7     .04 5048.44     .08  5089.8      .2
BR U Banks=4911.7,5048.44
BR D #Sta/Elev= 111
  4201.8   43.23  4226.8   43.48  4276.8   43.38  4301.8   41.46  4516.8   39.48
  4518.9   39.41  4528.9   38.92  4543.9   37.25  4548.9   36.91  4633.9   36.27
  4668.9   37.92  4703.9   37.86  4718.6   38.44  4743.6   38.04  4753.6   36.49
 4850.55   38.19 4858.35   38.32 4859.21   38.34  4862.1   38.33  4891.5   38.21
 4892.13   38.87 4894.52   38.96  4894.6    37.5 4894.72    35.3 4894.78    34.2
 4894.89   32.19 4895.01   29.99  4895.1   28.35 4895.69   17.55 4895.79   17.58
 4900.71   18.81 4905.39   18.78 4905.46   18.78 4910.61   18.75 4910.69   20.04
 4911.47   16.59  4911.7   20.05 4922.86   15.32 4942.75    10.5 4943.61   10.32
 4953.12    8.31 4963.34    4.97 4965.68    3.32 4966.23     2.8 4967.24     .15
 4967.63    -4.8 4975.51   -6.94  4988.3  -10.87 4990.64  -10.49 5007.18   -7.83
    5022   -7.04  5030.5   -5.69 5032.68     .41 5035.02    4.01 5043.37    4.71
 5045.08   11.76 5048.28   11.49 5048.44   16.64  5049.2   16.68 5049.45   12.14
 5051.79   12.21 5053.51   12.26 5054.44   20.31  5055.3   20.44 5061.62   20.42
  5063.1   17.15 5086.27   17.05  5086.5   18.34 5087.75   18.48 5087.91   24.81
 5089.05   24.69 5089.15   24.74  5089.8   25.06 5104.44   32.19 5105.98    41.3
 5106.03    41.3 5106.14    41.3 5106.24    41.3 5106.86   41.29 5106.94   37.96
 5108.97   37.91 5116.22   37.73 5119.05   36.79 5119.16   36.76 5119.27   36.72
 5119.96   36.49 5142.97    36.8 5143.05   36.78 5152.57   36.38  5184.3   35.04
  5199.3   35.41  5244.3   39.27  5254.3   39.79  5264.3    40.6  5384.3   39.99
    5398   40.42    5498   41.08    5503    40.4    5513   37.53    5518   35.91
    5523   35.47    5528   35.71    5543   37.75    5548   38.23    5588    37.5
    5593   37.57    5608   39.03    5618    40.4    5658   42.69    5683   44.52
  5747.1   45.47
BR D #Mann= 5
  4201.8      .2  4894.6     .08  4911.7     .04 5048.44     .08  5089.8      .2
BR D Banks=4911.7,5048.44
BC Design=,, 0 ,, 0 ,,,,,,
BC HTab HWMax=45.65

Type RM Length L Ch R = 1 ,112915.8,340.3,340.3,340.3
BEGIN DESCRIPTION:
Downstream Section of Bridge/Culvert/Weir
END DESCRIPTION:
XS GIS Cut Line= 6
      3120625.95     13843658.79      3120891.71     13843249.38
       3120946.3     13843118.97      3121100.12     13843048.55
       3121233.2     13842999.17      3121309.59     13842399.37
#Sta/Elev= 30
  4201.8   43.28  4894.6   37.55 4895.69    17.6  4911.7    20.1 4963.34    5.02
 4966.23    2.85 4967.63   -4.75  4988.3  -10.82  5030.5   -5.64 5035.02    4.06
 5043.37    4.76 5045.08   11.81 5048.28   11.54 5048.44   16.69 5049.45   12.19
 5053.51   12.31 5054.44   20.36  5055.3   20.49 5086.27    17.1 5087.75   18.53
 5087.91   24.86  5089.8   25.11 5104.44   32.24 5105.98   41.35 5119.96   36.54
  5184.3   35.09  5264.3   40.65    5498   41.13    5523   35.52  5747.1   45.52
#Mann= 5 ,-1 , 0
  4201.8      .2       0  4894.6     .08       0  4911.7     .04       0
 5048.44     .08       0  5089.8      .2       0
#XS Ineff= 2 , 0
          4894.7    36.6    5102            35.3
Permanent Ineff=
       F       F
Bank Sta=4911.7,5048.44
XS Rating Curve= 0
Exp/Cntr=.5,.3

Type RM Length L Ch R = 1 ,112575.5,82,82,82
BEGIN DESCRIPTION:
Upstream Section of Bridge/Culvert/Weir
END DESCRIPTION:
XS GIS Cut Line= 6
       3120425.7     13843708.49      3120895.63     13843543.63
      3121235.69     13843330.58      3121593.02     13843055.23
      3121662.78     13842864.74      3122004.72     13842296.45
#Sta/Elev= 30
  4100.7   43.05  4410.7   40.35  4761.2   30.35  4874.8   32.51    4878      13
  4884.4   13.98  4888.3   12.74  4913.2    13.2  4915.1    8.81  4969.3    2.86
  4971.3   -3.54  5002.4    -9.2  5029.3   -4.83  5029.8     2.3  5048.2    3.31
    5049   15.06  5050.1   15.11  5050.2   11.23  5074.2   11.26  5074.5   13.52
  5075.3   13.52  5105.5   21.44  5123.4   32.83  5124.6   29.45  5134.6   32.35
  5406.7   34.25  5697.3   40.15  5877.3   37.15  6224.4   42.65  6317.3   45.95
#Mann= 5 ,-1 , 0
  4100.7      .2       0  4884.4     .08       0  4913.2     .04       0
    5049     .08       0  5075.3      .2       0
#XS Ineff= 2 , 0
            4875    31.3    5090            32.5
Permanent Ineff=
       F       F
Bank Sta=4913.2,5049
XS Rating Curve= 0
Exp/Cntr=.5,.3

Type RM Length L Ch R = 3 ,112534.5,,,
BEGIN DESCRIPTION:
PRESTON STREET
Structure ID: WOO-27
END DESCRIPTION:
Bridge Culvert--1,0,-1,-1, 0
Deck Dist Width WeirC Skew NumUp NumDn MinLoCord MaxHiCord MaxSubmerge Is_Ogee
10,62,2.6,0, 44, 44, , , .95, 0, 1,1,,
  4100.7  4120.7  4150.7  4410.7  4546.3  4571.2  4731.2  4761.2  4787.4  4804.2
  4804.6  4814.5  4831.8  4831.9    4857  4869.7  4874.8 4875.59 4877.01  4877.1
 5081.99  5082.1  5092.7  5105.5  5107.2  5118.5  5123.4  5124.6  5134.6  5164.6
  5194.6  5224.6  5406.7  5456.7  5475.6  5667.3  5697.3  5837.3  5877.3  5954.4
  6194.4  6224.4  6294.4  6317.3
    43.1    43.3    42.9    40.4    36.4   35.21   32.01   31.42   31.33    31.3
    31.3   31.28   31.67   32.14   32.24   32.55   32.57   32.24   32.24   32.24
   32.62   32.62   32.75   32.91   32.93   32.53   32.89   32.51   32.49   32.45
   32.81   32.66   34.31   35.11   35.81    39.9    40.2    36.9    37.2    38.9
    42.8    42.7    45.9      46
    43.1    43.3    42.9    40.4    36.4    35.2      32    30.4   30.62   30.13
   30.47   30.83   31.46   32.13   31.96   32.54   32.56   27.74   19.09   28.28
   28.66   14.73   18.13   21.49   22.57   29.76   32.88    29.5    32.4    32.2
    32.8    32.3    34.3    35.1    35.8    39.9    40.2    36.9    37.2    38.9
    42.8    42.7    45.9      46
  4100.7  4120.7  4150.7  4410.7  4546.3  4571.2  4731.2  4761.2  4787.4  4804.2
  4804.6  4814.5  4831.8  4831.9    4857  4869.7  4874.8 4875.59 4877.01  4877.1
 5081.99  5082.1  5092.7  5105.5  5107.2  5118.5  5123.4  5124.6  5134.6  5164.6
  5194.6  5224.6  5406.7  5456.7  5475.6  5667.3  5697.3  5837.3  5877.3  5954.4
  6194.4  6224.4  6294.4  6317.3
    43.1    43.3    42.9    40.4    36.4   35.21   32.01   31.42   31.33    31.3
    31.3   31.28   31.67   32.14   32.24   32.55   32.57   32.24   32.24   32.24
   32.62   32.62   32.75   32.91   32.93   32.53   32.89   32.51   32.49   32.45
   32.81   32.66   34.31   35.11   35.81    39.9    40.2    36.9    37.2    38.9
    42.8    42.7    45.9      46
   42.78   42.98   42.58   40.08   36.08   34.88   31.68   30.08    30.3   29.81
   30.15   30.51   31.14   31.81   31.64   32.22   32.24   27.42   18.77   27.96
   28.34   14.41   17.81   21.17   22.25   29.44   32.56   29.18   32.08   31.88
   32.48   31.98   33.98   34.78   35.48   39.58   39.88   36.58   36.88   38.58
   42.48   42.38   45.58   45.68
Pier Skew, UpSta & Num, DnSta & Num=  ,4880.7, 2 ,4880.7, 2 , 0 , 0 , 0 ,,
     3.5     3.5
   12.01   29.29
     3.5     3.5
   11.69   28.97
Pier Skew, UpSta & Num, DnSta & Num=  ,4962.8, 2 ,4962.8, 2 , 0 , 0 , 0 ,,
     3.5     3.5
    1.66   29.45
     3.5     3.5
    1.34   29.13
Pier Skew, UpSta & Num, DnSta & Num=  ,5044.2, 2 ,5044.2, 2 , 0 , 0 , 0 ,,
     3.5     3.5
    2.52   29.61
     3.5     3.5
     2.2   29.29
Abutment Skew #Up #Dn= , 2 , 2
  4876.9    4878
   28.28   13.05
  4876.9    4878
   27.96   12.73
Abutment Skew #Up #Dn= , 2 , 2
  5078.5 5082.19
   13.57   28.66
  5078.5 5082.19
   13.25   28.34
BR Coef= 1 , 1 , 0 ,1.25, 0 ,,,.8,0,2,0,
WSPro=,,,, 1 ,,,, 0 ,,,, 0 ,,,,-1 ,-1 ,-1 , 0 , 0 , 0 , 0 , 0
BR U #Sta/Elev= 96
  4100.7    43.1  4120.7    43.3  4150.7    42.9  4410.7    40.4  4416.3    40.2
  4546.3    36.4  4564.4   35.53  4571.2    35.2  4684.4   32.94  4731.2      32
  4761.2    30.4  4764.5   30.43  4787.4   30.62  4804.2   30.13  4804.6   30.47
  4814.5   30.83  4831.8   31.46  4831.9   32.13    4857   31.96  4857.5   31.98
  4869.7   32.54  4874.8   32.56 4875.59   27.74  4875.7   27.07 4875.81    26.4
  4876.8   20.37  4876.9   19.76 4877.01   19.09  4877.1   18.54  4877.9   13.66
    4878   13.05  4880.7   12.94  4884.4   14.03  4887.6   14.98  4888.3   12.79
  4889.1   15.01  4889.3   13.38  4913.2   13.25  4915.1    8.86  4937.5    6.79
  4940.1    6.36  4962.8    2.57  4969.3    2.91  4970.5    -.13  4971.3   -3.49
  4980.2    -5.6  5002.4   -9.15  5022.1   -5.94  5024.3   -5.59  5029.3   -4.78
  5029.4   -3.35  5029.8    2.35  5038.2    2.47  5039.4    3.22  5044.2    3.69
  5048.2    3.36    5049   15.11  5050.1   15.16  5050.2   11.28  5074.2   11.31
  5074.5   13.57  5075.3   13.57  5078.4   13.57  5078.5   13.57  5081.9   14.66
 5081.99   14.69  5082.1   14.73  5082.2   14.76  5092.7   18.13  5105.5   21.49
 5106.09   21.87  5106.2   21.94 5106.31   22.01  5107.2   22.57  5118.5   29.76
  5123.4   32.88  5124.6    29.5  5134.6    32.4  5157.9   32.24  5164.6    32.2
  5194.6    32.8  5224.6    32.3  5406.7    34.3  5412.4   34.39  5456.7    35.1
  5475.6    35.8  5484.5   35.99  5667.3    39.9  5697.3    40.2  5837.3    36.9
  5877.3    37.2  5954.4    38.9  6194.4    42.8  6224.4    42.7  6294.4    45.9
  6317.3      46
BR U #Mann= 5
  4100.7      .2  4884.4     .08  4913.2     .04    5049     .08  5075.3      .2
BR U Banks=4913.2,5049
BR D #Sta/Elev= 96
  4100.7   42.78  4120.7   42.98  4150.7   42.58  4410.7   40.08  4416.3   39.88
  4546.3   36.08  4564.4   35.21  4571.2   34.88  4684.4   32.62  4731.2   31.68
  4761.2   30.08  4764.5   30.11  4787.4    30.3  4804.2   29.81  4804.6   30.15
  4814.5   30.51  4831.8   31.14  4831.9   31.81    4857   31.64  4857.5   31.66
  4869.7   32.22  4874.8   32.24 4875.59   27.42  4875.7   26.75 4875.81   26.08
  4876.8   20.05  4876.9   19.44 4877.01   18.77  4877.1   18.22  4877.9   13.34
    4878   12.73  4880.7   12.62  4884.4   13.71  4887.6   14.66  4888.3   12.47
  4889.1   14.69  4889.3   13.06  4913.2   12.93  4915.1    8.54  4937.5    6.47
  4940.1    6.04  4962.8    2.25  4969.3    2.59  4970.5    -.45  4971.3   -3.81
  4980.2   -5.92  5002.4   -9.47  5022.1   -6.26  5024.3   -5.91  5029.3    -5.1
  5029.4   -3.67  5029.8    2.03  5038.2    2.15  5039.4     2.9  5044.2    3.37
  5048.2    3.04    5049   14.79  5050.1   14.84  5050.2   10.96  5074.2   10.99
  5074.5   13.25  5075.3   13.25  5078.4   13.25  5078.5   13.25  5081.9   14.34
 5081.99   14.37  5082.1   14.41  5082.2   14.44  5092.7   17.81  5105.5   21.17
 5106.09   21.55  5106.2   21.62 5106.31   21.69  5107.2   22.25  5118.5   29.44
  5123.4   32.56  5124.6   29.18  5134.6   32.08  5157.9   31.92  5164.6   31.88
  5194.6   32.48  5224.6   31.98  5406.7   33.98  5412.4   34.07  5456.7   34.78
  5475.6   35.48  5484.5   35.67  5667.3   39.58  5697.3   39.88  5837.3   36.58
  5877.3   36.88  5954.4   38.58  6194.4   42.48  6224.4   42.38  6294.4   45.58
  6317.3   45.68
BR D #Mann= 5
  4100.7      .2  4884.4     .08  4913.2     .04    5049     .08  5075.3      .2
BR D Banks=4913.2,5049
BC Design=,, 0 ,, 0 ,,,,,,
BC HTab HWMax=45.95

Type RM Length L Ch R = 1 ,112493.5,490.2,490.2,490.2
BEGIN DESCRIPTION:
Downstream Section of Bridge/Culvert/Weir
END DESCRIPTION:
XS GIS Cut Line= 6
      3120478.35     13843771.36      3120948.29     13843606.49
      3121288.35     13843393.44      3121645.68     13843118.09
      3121715.44      13842927.6      3122057.37     13842359.32
#Sta/Elev= 30
  4100.7   42.78  4410.7   40.08  4761.2   30.08  4874.8   32.24    4878   12.73
  4884.4   13.71  4888.3   12.47  4913.2   12.93  4915.1    8.54  4969.3    2.59
  4971.3   -3.81  5002.4   -9.47  5029.3    -5.1  5029.8    2.03  5048.2    3.04
    5049   14.79  5050.1   14.84  5050.2   10.96  5074.2   10.99  5074.5   13.25
  5075.3   13.25  5105.5   21.17  5123.4   32.56  5124.6   29.18  5134.6   32.08
  5406.7   33.98  5697.3   39.88  5877.3   36.88  6224.4   42.38  6317.3   45.68
#Mann= 5 ,-1 , 0
  4100.7      .2       0  4884.4     .08       0  4913.2     .04       0
    5049     .08       0  5075.3      .2       0
#XS Ineff= 2 , 0
            4875    31.3    5090            32.5
Permanent Ineff=
       F       F
Bank Sta=4913.2,5049
XS Rating Curve= 0
Exp/Cntr=.5,.3

Type RM Length L Ch R = 1 ,112003.3,100,100,100
BEGIN DESCRIPTION:
Upstream Section of Bridge/Culvert/Weir
END DESCRIPTION:
XS GIS Cut Line= 6
        3121544.     13843930.99      3121698.63     13843673.25
      3121719.21     13843461.31      3121706.04      13843292.1
      3121722.78     13842932.75       3122052.3     13842515.12
#Sta/Elev= 30
  4486.2      45  4796.2      41  4826.2    33.7  4868.7   33.24  4891.4   11.45
  4905.6   11.42  4905.9       8  4915.1    7.83  4917.1    1.68  4929.6    -.35
  4958.9   -1.03    4971   -5.25  4994.4   -9.69  5012.4   -5.11  5025.2   -5.03
  5031.4   -2.03  5053.7    2.31  5067.1    7.14  5069.4   10.98  5069.6   17.08
  5110.3    16.2  5119.4   20.08  5131.2    20.1  5138.9   20.06  5176.5   32.95
  5318.6    36.8  5448.6    36.5  5578.9    39.9  5758.9    36.9  6061.2    42.6
#Mann= 4 ,-1 , 0
  4486.2      .2       0  4891.4     .04       0  5069.6     .08       0
  5131.2      .2       0
#XS Ineff= 2 , 0
            4864    33.5    5150           33.74
Permanent Ineff=
       F       F
Bank Sta=4891.4,5069.6
XS Rating Curve= 0
Exp/Cntr=.5,.3

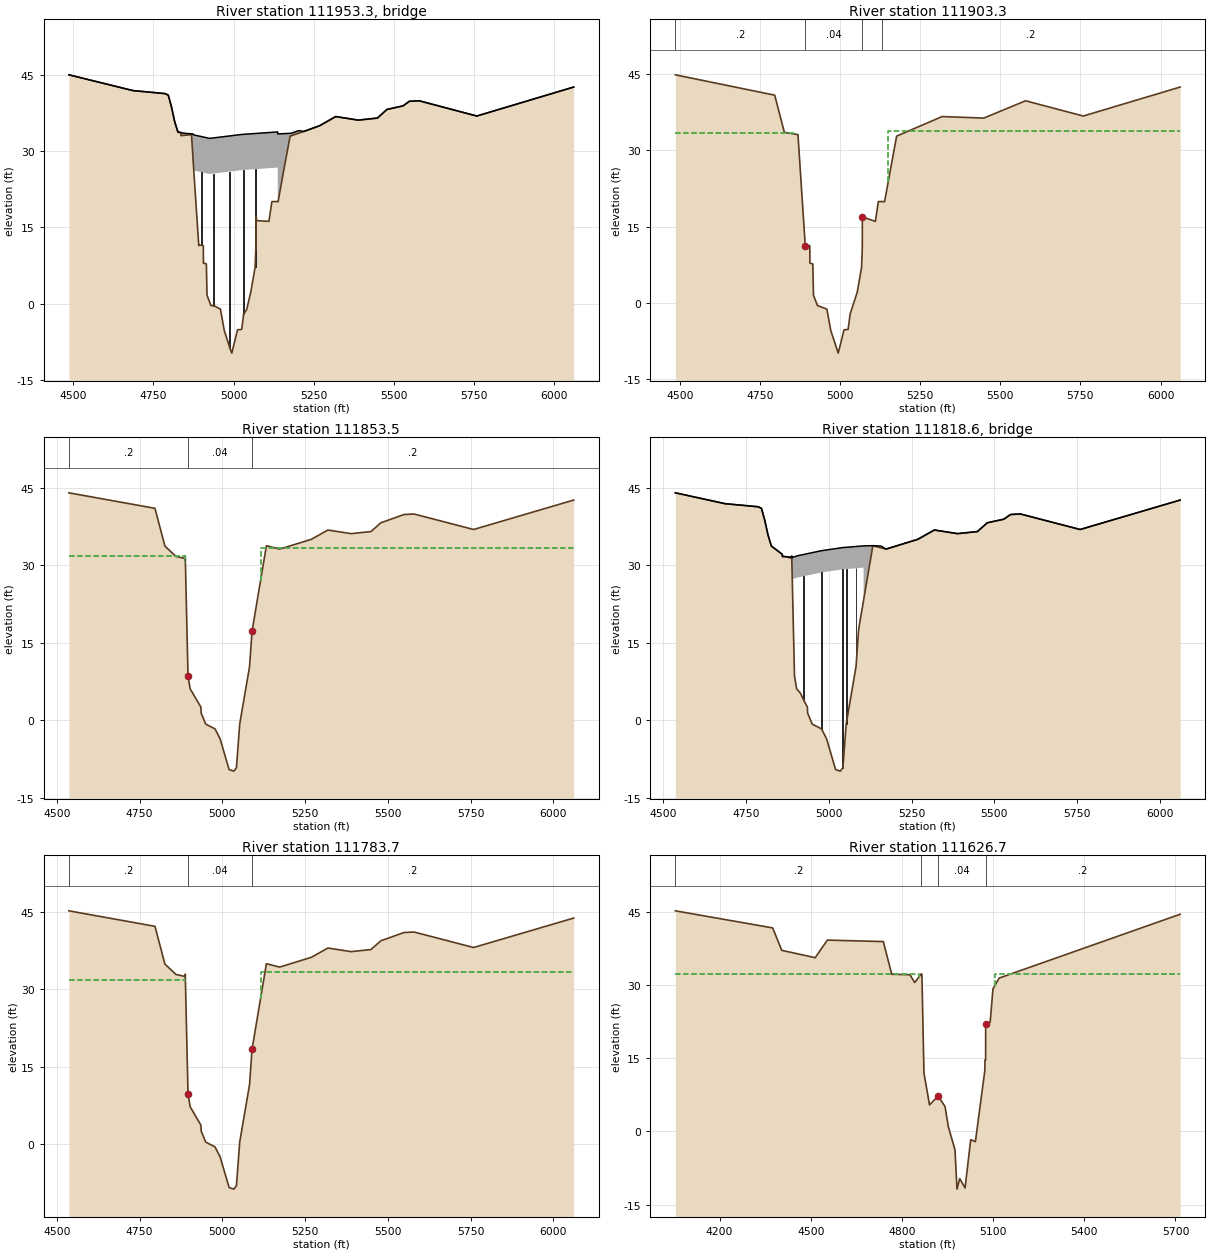
Type RM Length L Ch R = 3 ,111953.3,,,
BEGIN DESCRIPTION:
CONGRESS STREET
Structure ID: WOO-26
END DESCRIPTION:
Bridge Culvert--1,0,-1,-1, 0
Deck Dist Width WeirC Skew NumUp NumDn MinLoCord MaxHiCord MaxSubmerge Is_Ogee
10,80,2.6,0, 35, 35, , , .95, 0, 1,1,,
  4486.2  4686.2  4786.2  4796.2  4806.2  4816.2  4826.2  4835.3  4835.6  4844.1
  4868.7  4873.5  4874.7    4876  4925.3  5025.2  5137.4 5137.79  5137.9  5138.9
  5158.3  5176.5  5179.6  5203.5  5218.9  5268.6  5318.6  5388.6  5448.6  5478.6
  5528.6  5548.6  5578.9  5758.9  6061.2
      45    41.9   41.31   41.01   38.71   35.81   33.84   33.68   33.68   33.53
   33.41   33.39   33.21   33.19   32.51   33.28   33.78   33.48   33.39   33.39
   33.45    33.5   33.51   34.04   33.87      35    36.8    36.1    36.5    38.2
    38.9    39.8    39.9    36.9    42.6
      45    41.9    41.3      41    38.7    35.8    33.7   33.61   33.05    33.1
   33.24   28.48   27.29   26.19   25.51   26.28   26.78   26.48   20.07   20.06
   26.85   32.95   33.02   33.54   33.87      35    36.8    36.1    36.5    38.2
    38.9    39.8    39.9    36.9    42.6
  4486.2  4686.2  4786.2  4796.2  4806.2  4816.2  4826.2  4835.3  4835.6  4844.1
  4868.7  4873.5  4874.7    4876  4925.3  5025.2  5137.4 5137.79  5137.9  5138.9
  5158.3  5176.5  5179.6  5203.5  5218.9  5268.6  5318.6  5388.6  5448.6  5478.6
  5528.6  5548.6  5578.9  5758.9  6061.2
      45    41.9   41.31   41.01   38.71   35.81   33.84   33.68   33.68   33.53
   33.41   33.39   33.21   33.19   32.51   33.28   33.78   33.48   33.39   33.39
   33.45    33.5   33.51   34.04   33.87      35    36.8    36.1    36.5    38.2
    38.9    39.8    39.9    36.9    42.6
   44.86   41.76   41.16   40.86   38.56   35.66   33.56   33.47   32.91   32.96
    33.1   28.34   27.15   26.05   25.37   26.14   26.64   26.34   19.93   19.92
   26.71   32.81   32.88    33.4   33.73   34.86   36.66   35.96   36.36   38.06
   38.76   39.66   39.76   36.76   42.46
Pier Skew, UpSta & Num, DnSta & Num=  ,4898.8, 2 ,4898.8, 2 , 0 , 0 , 0 ,,
     2.8     2.8
   10.52   26.89
     2.8     2.8
   10.38   26.75
Pier Skew, UpSta & Num, DnSta & Num=  ,4937.7, 2 ,4937.7, 2 , 0 , 0 , 0 ,,
     2.8     2.8
   -1.39   26.63
     2.8     2.8
   -1.53   26.49
Pier Skew, UpSta & Num, DnSta & Num=  ,4988.1, 2 ,4988.1, 2 , 0 , 0 , 0 ,,
     3.4     3.4
   -9.91   27.04
     3.4     3.4
  -10.05    26.9
Pier Skew, UpSta & Num, DnSta & Num=  ,5031.4, 2 ,5031.4, 2 , 0 , 0 , 0 ,,
     3.3     3.3
   -3.83   27.32
     3.3     3.3
   -3.97   27.18
Pier Skew, UpSta & Num, DnSta & Num=  ,5067.1, 2 ,5067.1, 2 , 0 , 0 , 0 ,,
     2.8     2.8
    5.64   27.46
     2.8     2.8
     5.5   27.32
Abutment Skew #Up #Dn= , 2 , 2
  4874.5  4891.5
   27.29   11.45
  4874.5  4891.5
   27.15   11.31
Abutment Skew #Up #Dn= , 2 , 2
  5134.4 5137.99
    20.1   26.48
  5134.4 5137.99
   19.96   26.34
BR Coef= 1 , 1 , 0 ,1.25, 0 ,,,.8,0,2,0,
WSPro=,,,, 1 ,,,, 0 ,,,, 0 ,,,,-1 ,-1 ,-1 , 0 , 0 , 0 , 0 , 0
BR U #Sta/Elev= 78
  4486.2      45  4686.2    41.9  4760.3   41.46  4786.2    41.3  4794.3   41.06
  4796.2      41  4806.2    38.7  4816.2    35.8  4826.2    33.7  4835.2   33.61
  4835.3   33.61  4835.6   33.05  4844.1    33.1  4868.7   33.24  4873.5   28.48
  4874.5   27.49 4874.61   27.38  4874.7   27.29    4876      26  4891.4   11.45
  4891.5   11.45  4898.8   11.55  4905.6   11.42  4905.9       8 4908.79    7.95
  4908.9    7.94 4909.01    7.94  4915.1    7.83  4917.1    1.68  4925.3     .35
  4929.6    -.35  4937.7    -.35  4958.9   -1.03    4971   -5.25  4981.6   -7.34
  4988.1   -8.62  4994.4   -9.69  5012.4   -5.11  5025.2   -5.03  5027.1   -4.11
  5031.4   -2.03  5041.1    -1.1  5053.7    2.31  5067.1    7.14  5069.4   10.98
  5069.6   17.08    5071   17.05  5071.6   16.35    5089   16.28  5110.3    16.2
  5119.4   20.08  5131.2    20.1  5134.3    20.1  5134.4    20.1  5137.4   20.07
 5137.79   20.07  5137.9   20.07    5138   20.07  5138.9   20.06  5158.3   26.85
  5176.5   32.95 5176.99   32.96  5177.1   32.96 5177.21   32.97  5179.6   33.02
  5203.5   33.54  5218.9   33.87  5220.5    33.9  5268.6      35  5318.6    36.8
  5388.6    36.1  5448.6    36.5  5478.6    38.2  5528.6    38.9  5548.6    39.8
  5578.9    39.9  5758.9    36.9  6061.2    42.6
BR U #Mann= 4
  4486.2      .2  4891.4     .04  5069.6     .08  5131.2      .2
BR U Banks=4891.4,5069.6
BR D #Sta/Elev= 78
  4486.2   44.86  4686.2   41.76  4760.3   41.32  4786.2   41.16  4794.3   40.92
  4796.2   40.86  4806.2   38.56  4816.2   35.66  4826.2   33.56  4835.2   33.47
  4835.3   33.47  4835.6   32.91  4844.1   32.96  4868.7    33.1  4873.5   28.34
  4874.5   27.35 4874.61   27.24  4874.7   27.15    4876   25.86  4891.4   11.31
  4891.5   11.31  4898.8   11.41  4905.6   11.28  4905.9    7.86 4908.79    7.81
  4908.9     7.8 4909.01     7.8  4915.1    7.69  4917.1    1.54  4925.3     .21
  4929.6    -.49  4937.7    -.49  4958.9   -1.17    4971   -5.39  4981.6   -7.48
  4988.1   -8.76  4994.4   -9.83  5012.4   -5.25  5025.2   -5.17  5027.1   -4.25
  5031.4   -2.17  5041.1   -1.24  5053.7    2.17  5067.1       7  5069.4   10.84
  5069.6   16.94    5071   16.91  5071.6   16.21    5089   16.14  5110.3   16.06
  5119.4   19.94  5131.2   19.96  5134.3   19.96  5134.4   19.96  5137.4   19.93
 5137.79   19.93  5137.9   19.93    5138   19.93  5138.9   19.92  5158.3   26.71
  5176.5   32.81 5176.99   32.82  5177.1   32.82 5177.21   32.83  5179.6   32.88
  5203.5    33.4  5218.9   33.73  5220.5   33.76  5268.6   34.86  5318.6   36.66
  5388.6   35.96  5448.6   36.36  5478.6   38.06  5528.6   38.76  5548.6   39.66
  5578.9   39.76  5758.9   36.76  6061.2   42.46
BR D #Mann= 4
  4486.2      .2  4891.4     .04  5069.6     .08  5131.2      .2
BR D Banks=4891.4,5069.6
BC Design=,, 0 ,, 0 ,,,,,,
BC HTab HWMax=45

Type RM Length L Ch R = 1 ,111903.3,49.8,49.8,49.8
BEGIN DESCRIPTION:
Downstream Section of Bridge/Culvert/Weir
END DESCRIPTION:
XS GIS Cut Line= 6
      3121642.99     13843916.85      3121797.63     13843659.11
      3121818.21     13843447.17      3121805.04     13843277.96
      3121821.78     13842918.61      3122151.29     13842500.98
#Sta/Elev= 30
  4486.2   44.85  4796.2   40.85  4826.2   33.55  4868.7   33.09  4891.4    11.3
  4905.6   11.27  4905.9    7.85  4915.1    7.68  4917.1    1.53  4929.6     -.5
  4958.9   -1.18    4971    -5.4  4994.4   -9.84  5012.4   -5.26  5025.2   -5.18
  5031.4   -2.18  5053.7    2.16  5067.1    6.99  5069.4   10.83  5069.6   16.93
  5110.3   16.05  5119.4   19.93  5131.2   19.95  5138.9   19.91  5176.5    32.8
  5318.6   36.65  5448.6   36.35  5578.9   39.75  5758.9   36.75  6061.2   42.45
#Mann= 4 ,-1 , 0
  4486.2      .2       0  4891.4     .04       0  5069.6     .08       0
  5131.2      .2       0
#XS Ineff= 2 , 0
            4864    33.5    5150           33.74
Permanent Ineff=
       F       F
Bank Sta=4891.4,5069.6
XS Rating Curve= 0
Exp/Cntr=.5,.3

Type RM Length L Ch R = 1 ,111853.5,69.8,69.8,69.8
BEGIN DESCRIPTION:
Upstream Section of Bridge/Culvert/Weir
END DESCRIPTION:
XS GIS Cut Line= 6
      3121843.59     13843721.26      3122000.72     13843641.98
      3122040.97     13843515.88      3121826.33     13843373.68
      3121866.57     13842930.99      3122172.26     13842518.78
#Sta/Elev= 30
  4536.2   44.01  4796.2   41.01  4826.2   33.71 4859.59   31.69 4887.39    31.3
 4887.74   31.75 4896.02    8.63 4902.43    6.09 4935.14    2.51 4935.62    1.41
 4949.49    -.75 4977.71   -1.69 4993.03   -3.61 5020.22   -9.56 5034.57   -9.86
  5042.3   -9.19 5052.23    -.75 5081.97   10.39 5089.42   17.19 5132.83   33.77
 5172.91   33.12  5268.6   35.01  5318.6   36.81  5388.6   36.11  5448.6   36.51
  5478.6   38.21  5548.6   39.81  5578.9   39.91  5758.9   36.91  6061.2   42.61
#Mann= 3 ,-1 , 0
  4536.2      .2       0 4896.02     .04       0 5089.42      .2       0
#XS Ineff= 2 , 0
          4888.2    31.8    5115            33.3
Permanent Ineff=
       F       F
Bank Sta=4896.02,5089.42
XS Rating Curve= 0
Exp/Cntr=.5,.3

Type RM Length L Ch R = 3 ,111818.6,,,
BEGIN DESCRIPTION:
SMITH STREET     Skew angle 46 degrees
Structure ID: WOO-25
END DESCRIPTION:
Bridge Culvert--1,0,-1,-1, 0
Deck Dist Width WeirC Skew NumUp NumDn MinLoCord MaxHiCord MaxSubmerge Is_Ogee
10,49.8,2.6,0, 33, 33, , , .95, 0, 1,1,,
  4536.2  4686.2  4786.2  4796.2  4806.2  4816.2  4826.2 4859.31 4859.59 4872.35
 4887.39 4887.74 4890.78 4890.89 4890.98 4907.61 4977.71 5041.68 5104.74 5104.85
 5132.83 5157.46 5172.91  5268.6  5318.6  5388.6  5448.6  5478.6  5528.6  5548.6
  5578.9  5758.9  6061.2
      44    41.9    41.3      41    38.7    35.8    33.7    32.1   31.69   31.63
   31.56   31.75   31.54   31.54   31.54   31.85    32.8    33.4   33.73   33.73
   33.77   33.69   33.11      35    36.8    36.1    36.5    38.2    38.9    39.8
    39.9    36.9    42.6
      44    41.9    41.3      41    38.7    35.8    33.7   32.09   31.68   31.62
   31.29   31.74   23.25   22.94   27.33   27.64   28.59   29.19   29.52   23.24
   33.76   33.36   33.11      35    36.8    36.1    36.5    38.2    38.9    39.8
    39.9    36.9    42.6
  4536.2  4686.2  4786.2  4796.2  4806.2  4816.2  4826.2 4859.31 4859.59 4872.35
 4887.39 4887.74 4890.78 4890.89 4890.98 4907.61 4977.71 5041.68 5104.74 5104.85
 5105.78 5132.83 5172.91  5268.6  5318.6  5388.6  5448.6  5478.6  5528.6  5548.6
  5578.9  5758.9  6061.2
    45.4    43.3    42.7    42.4    40.1    37.2    35.1   33.49   33.08   33.02
   32.69   33.14   31.54   31.54   31.54   31.85    32.8    33.4   33.73   33.73
   33.69   35.16   34.51    36.4    38.2    37.5    37.9    39.6    40.3    41.2
    41.3    38.3      44
    45.4    43.3    42.7    42.4    40.1    37.2    35.1   33.49   33.08   33.02
   32.69   33.14   24.65   24.34   28.73   29.04   29.99   30.59   30.92   24.64
   24.99   35.16   34.51    36.4    38.2    37.5    37.9    39.6    40.3    41.2
    41.3    38.3      44
Pier Skew, UpSta & Num, DnSta & Num=  ,4924.1, 2 ,4924.1, 2 , 0 , 0 , 0 ,,
     2.5     2.5
     2.7   28.88
     2.5     2.5
     4.1   30.28
Pier Skew, UpSta & Num, DnSta & Num=  ,4977.7, 2 ,4977.7, 2 , 0 , 0 , 0 ,,
     2.5     2.5
   -2.86    29.6
     2.5     2.5
   -1.46      31
Pier Skew, UpSta & Num, DnSta & Num=  ,5042.3, 2 ,5042.3, 2 , 0 , 0 , 0 ,,
     2.5     2.5
  -10.31    30.2
     2.5     2.5
   -8.91    31.6
Pier Skew, UpSta & Num, DnSta & Num=  ,5052.2, 2 ,5052.2, 2 , 0 , 0 , 0 ,,
     3.8     3.8
   -3.37   30.26
     3.8     3.8
   -1.97   31.66
Pier Skew, UpSta & Num, DnSta & Num=  ,5082, 2 ,5082, 2 , 0 , 0 , 0 ,,
     2.2     2.2
    8.97   30.41
     2.2     2.2
   10.37   31.81
Abutment Skew #Up #Dn= , 2 , 2
 4890.78 4896.02
   27.33    8.63
 4890.78 4896.02
   28.73   10.03
Abutment Skew #Up #Dn= , 2 , 2
 5091.56 5104.94
   18.24   29.52
 5091.56 5104.94
   19.64   30.92
BR Coef= 1 , 1 , 0 ,1.25, 0 ,,,.8,0,2,0,
WSPro=,,,, 1 ,,,, 0 ,,,, 0 ,,,,-1 ,-1 ,-1 , 0 , 0 , 0 , 0 , 0
BR U #Sta/Elev= 61
  4536.2      44  4686.2    41.9  4786.2    41.3  4796.2      41  4806.2    38.7
  4816.2    35.8  4826.2    33.7 4848.75    32.6 4855.65   32.27 4859.31   32.09
 4859.59   31.68 4865.17   31.65 4872.35   31.62 4887.39   31.29 4887.74   31.74
 4890.78   23.25 4890.89   22.94 4890.98   22.69 4895.53    9.99 4895.64    9.68
 4895.75    9.37 4895.92     8.9 4896.02    8.62 4902.43    6.08 4907.61    5.69
  4914.1     5.2  4924.1    3.85 4935.14     2.5 4935.62     1.4 4949.49    -.76
 4975.99   -1.64 4977.71    -1.7 4993.03   -3.62 5020.22   -9.57 5034.57   -9.87
 5041.68   -9.25  5042.3    -9.2 5052.23    -.76 5081.97   10.38 5089.42   17.18
 5091.46    18.2 5091.56   18.24 5104.74   23.19 5104.85   23.24 5104.95   23.27
 5105.78   23.59 5132.83   33.76 5157.25   33.36 5157.36   33.36 5157.46   33.36
 5172.91   33.11  5268.6      35  5318.6    36.8  5388.6    36.1  5448.6    36.5
  5478.6    38.2  5528.6    38.9  5548.6    39.8  5578.9    39.9  5758.9    36.9
  6061.2    42.6
BR U #Mann= 3
  4536.2      .2 4896.02     .04 5089.42      .2
BR U Banks=4896.02,5089.42
BR D #Sta/Elev= 61
  4536.2    45.4  4686.2    43.3  4786.2    42.7  4796.2    42.4  4806.2    40.1
  4816.2    37.2  4826.2    35.1 4848.75      34 4855.65   33.67 4859.31   33.49
 4859.59   33.08 4865.17   33.05 4872.35   33.02 4887.39   32.69 4887.74   33.14
 4890.78   24.65 4890.89   24.34 4890.98   24.09 4895.53   11.39 4895.64   11.08
 4895.75   10.77 4895.92    10.3 4896.02   10.02 4902.43    7.48 4907.61    7.09
  4914.1     6.6  4924.1    5.25 4935.14     3.9 4935.62     2.8 4949.49     .64
 4975.99    -.24 4977.71     -.3 4993.03   -2.22 5020.22   -8.17 5034.57   -8.47
 5041.68   -7.85  5042.3    -7.8 5052.23     .64 5081.97   11.78 5089.42   18.58
 5091.46    19.6 5091.56   19.64 5104.74   24.59 5104.85   24.64 5104.95   24.67
 5105.78   24.99 5132.83   35.16 5157.25   34.76 5157.36   34.76 5157.46   34.76
 5172.91   34.51  5268.6    36.4  5318.6    38.2  5388.6    37.5  5448.6    37.9
  5478.6    39.6  5528.6    40.3  5548.6    41.2  5578.9    41.3  5758.9    38.3
  6061.2      44
BR D #Mann= 3
  4536.2      .2 4896.02     .04 5089.42      .2
BR D Banks=4896.02,5089.42
BC Design=,, 0 ,, 0 ,,,,,,
BC HTab HWMax=44.01

Type RM Length L Ch R = 1 ,111783.7,157,157,157
BEGIN DESCRIPTION:
Downstream Section of Bridge/Culvert/Weir
END DESCRIPTION:
XS GIS Cut Line= 6
      3121912.58     13843710.65       3122069.7     13843631.36
      3122109.95     13843505.26      3121895.31     13843363.06
      3121935.55     13842920.37      3122241.25     13842508.16
#Sta/Elev= 30
  4536.2    45.2  4796.2    42.2  4826.2    34.9 4859.59   32.88 4887.39   32.49
 4887.74   32.94 4896.02    9.82 4902.43    7.28 4935.14     3.7 4935.62     2.6
 4949.49     .44 4977.71     -.5 4993.03   -2.42 5020.22   -8.37 5034.57   -8.67
  5042.3      -8 5052.23     .44 5081.97   11.58 5089.42   18.38 5132.83   34.96
 5172.91   34.31  5268.6    36.2  5318.6      38  5388.6    37.3  5448.6    37.7
  5478.6    39.4  5548.6      41  5578.9    41.1  5758.9    38.1  6061.2    43.8
#Mann= 3 ,-1 , 0
  4536.2      .2       0 4896.02     .04       0 5089.42      .2       0
#XS Ineff= 2 , 0
          4888.2    31.8    5115            33.3
Permanent Ineff=
       F       F
Bank Sta=4896.02,5089.42
XS Rating Curve= 0
Exp/Cntr=.5,.3

Type RM Length L Ch R = 1 ,111626.7,216.2,216.2,216.2
BEGIN DESCRIPTION:
Upstream Section of Bridge/Culvert/Weir
END DESCRIPTION:
XS GIS Cut Line= 6
      3121516.03     13844004.42      3122043.96     13843665.99
      3122113.71     13843566.72      3122172.74      13843459.4
      3122241.66     13843223.79      3122277.66     13842681.25
#Sta/Elev= 30
  4054.8    45.2  4374.8    41.7  4404.8    37.1  4514.8    35.6  4554.8    39.2
  4738.8    38.9  4766.6    32.2  4826.6    32.1    4842    30.5  4864.3   32.31
  4865.9   32.01  4872.5      12  4890.8    5.43  4919.1    7.23  4941.8    5.12
  4952.6    1.01  4974.7    -3.8  4981.2  -11.83  4990.2   -9.68  5007.8  -11.58
  5026.3   -1.71  5041.8    -2.1  5072.7   12.43  5073.4   14.61  5075.4   14.57
  5075.6   21.92  5090.3   22.36  5099.5   29.18  5119.9   31.42  5715.4    44.5
#Mann= 4 ,-1 , 0
  4054.8      .2       0  4864.3     .12       0  4919.1     .04       0
  5075.6      .2       0
#XS Ineff= 2 , 0
            4857    32.2    5106            32.2
Permanent Ineff=
       F       F
Bank Sta=4919.1,5075.6
XS Rating Curve= 0
Exp/Cntr=.5,.3