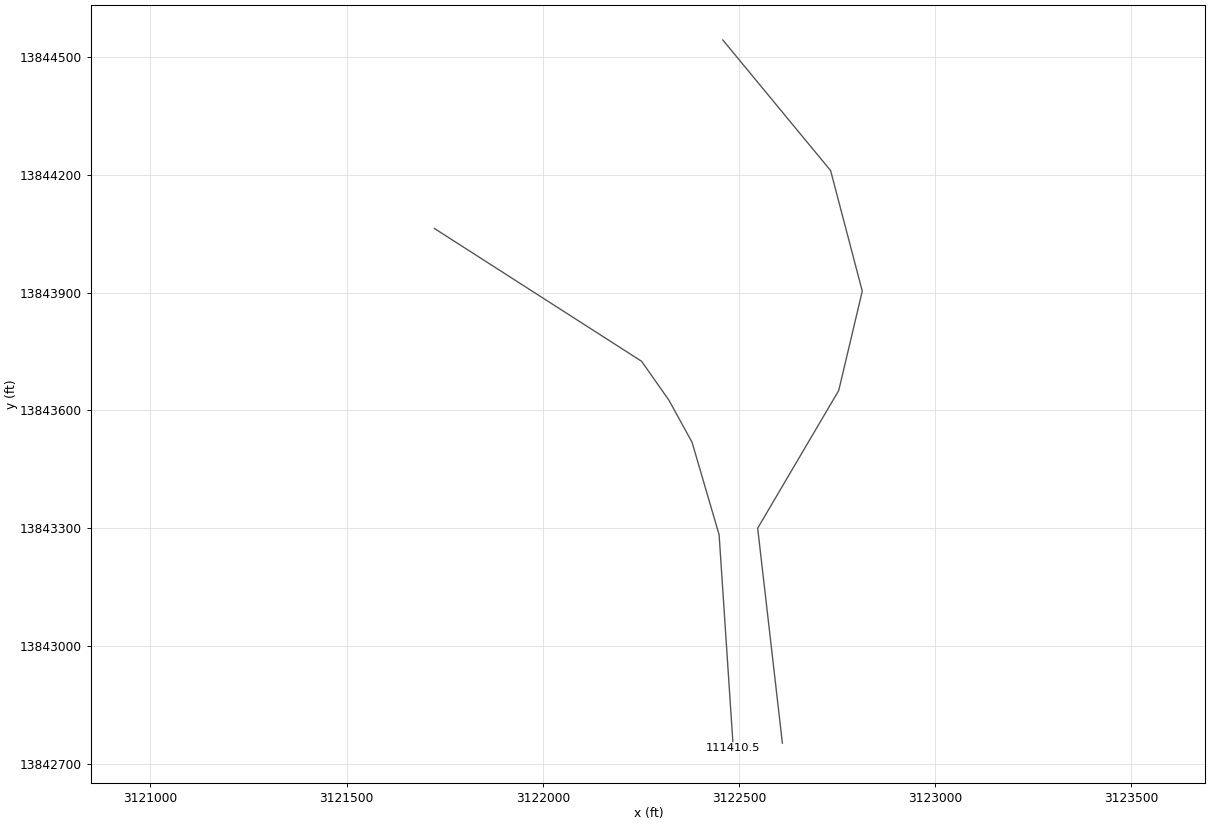
HEC-RAS study W100-00-00.prj: W100-00-00

--- W100-00-00.g01 (geometry) --- (continued)

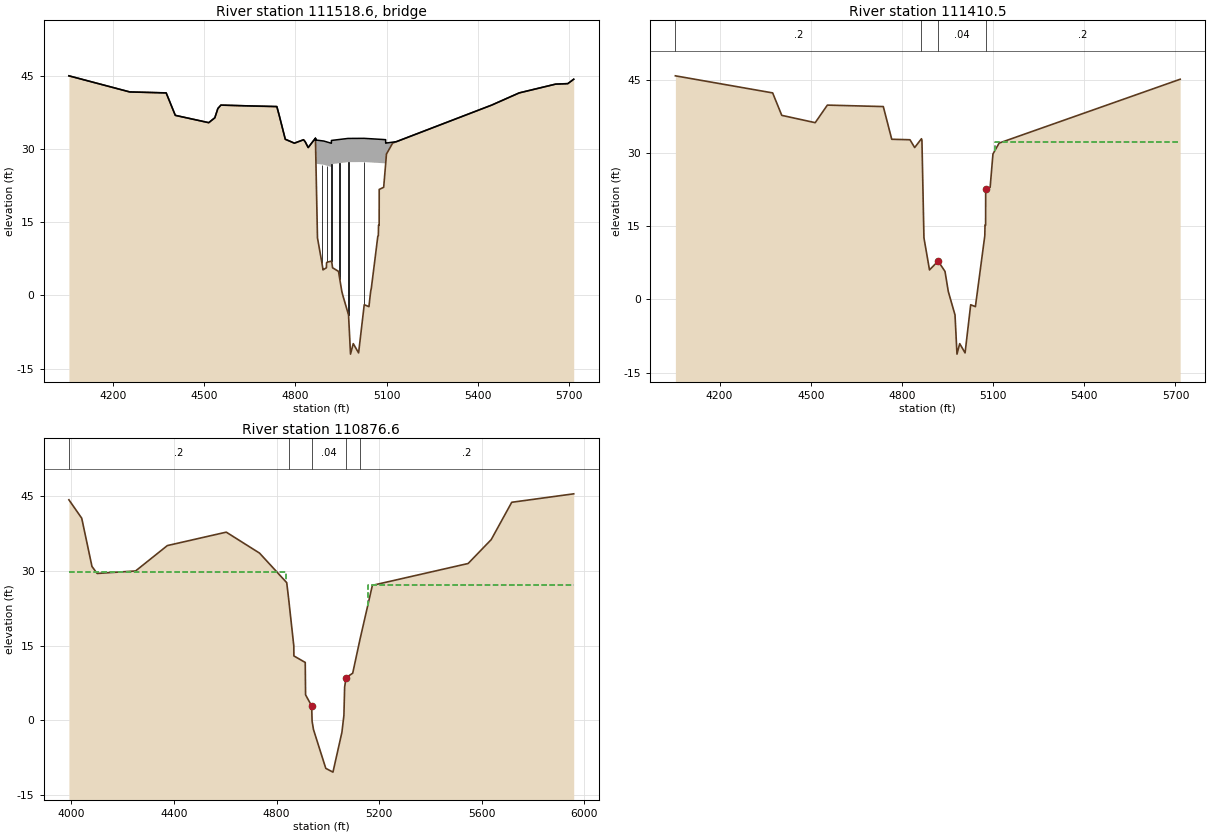
Type RM Length L Ch R = 3 ,111518.6,,,
BEGIN DESCRIPTION:
LOUISIANA AND FRANKLIN
Structure ID: WOO-23
END DESCRIPTION:
Bridge Culvert--1,0,-1,-1, 0
Deck Dist Width WeirC Skew NumUp NumDn MinLoCord MaxHiCord MaxSubmerge Is_Ogee
10,196.2,2.6,0, 35, 36, , , .95, 0, 1,1,,
  4054.8  4254.8  4374.8  4404.8  4514.8  4534.8  4544.8  4554.8  4738.8  4746.6
  4766.6  4796.6  4826.6    4832    4842  4865.3  4865.9    4866  4866.2  4867.9
  4893.2  4918.2  4918.4  4972.5  5026.3  5096.7  5096.9  5099.5  5119.9  5132.2
  5445.5    5536    5656    5696  5715.4
      45    41.7    41.5    36.9    35.4    36.4    38.3      39    38.7    36.9
      32    31.2    31.9    31.5    30.3   32.18   31.81   32.23   32.19   31.84
   31.64   31.18   31.76   32.17   32.19   31.92   31.19   31.24   31.41   31.51
      39    41.5    43.3    43.4    44.3
      45    41.7    41.5    36.9    35.4    36.4    38.3      39    38.7    36.9
      32    31.2    31.9    31.5    30.3   32.18   31.81   31.51    30.9   26.98
   26.78   26.32    26.9   27.31   27.33   27.06   27.05   28.98   31.22   31.51
      39    41.5    43.3    43.4    44.3
  4054.8  4254.8  4374.8  4404.8  4514.8  4534.8  4544.8  4554.8  4738.8  4746.6
  4766.6  4796.6  4826.6    4832    4842  4865.3  4865.9    4866 4866.11  4866.2
  4867.9  4893.2  4918.2  4918.4  4972.5  5026.3  5096.7  5096.9  5099.5 5113.41
  5119.9  5445.5    5536    5656    5696  5715.4
   45.79   42.49   42.29   37.69   36.19   37.19   39.09   39.79   39.49   37.69
   32.79   31.99   32.69   32.29   31.09   32.97    32.6    32.3   32.21   32.19
   31.84   31.64   31.18   31.76   32.17   32.19   31.92   31.19   31.24   31.35
   32.01   39.79   42.29   44.09   44.19   45.09
   45.79   42.49   42.29   37.69   36.19   37.19   39.09   39.79   39.49   37.69
   32.79   31.99   32.69   32.29   31.09   32.97    32.6    32.3   31.96   31.69
   27.77   27.57   27.11   27.69    28.1   28.12   27.85   27.84   29.77    31.3
   32.01   39.79   42.29   44.09   44.19   45.09
Pier Skew, UpSta & Num, DnSta & Num=  ,4887.1, 2 ,4887.1, 2 , 0 , 0 , 0 ,,
     2.5     2.5
    5.18   27.84
     2.5     2.5
    5.97   28.63
Pier Skew, UpSta & Num, DnSta & Num=  ,4904.2, 2 ,4904.2, 2 , 0 , 0 , 0 ,,
     2.5     2.5
    5.73    27.6
     2.5     2.5
    6.52   28.39
Pier Skew, UpSta & Num, DnSta & Num=  ,4919.1, 2 ,4919.1, 2 , 0 , 0 , 0 ,,
     2.5     2.5
    5.47   27.91
     2.5     2.5
    6.26    28.7
Pier Skew, UpSta & Num, DnSta & Num=  ,4946, 2 ,4946, 2 , 0 , 0 , 0 ,,
     2.5     2.5
    1.81   28.12
     2.5     2.5
     2.6   28.91
Pier Skew, UpSta & Num, DnSta & Num=  ,4974.7, 2 ,4974.7, 2 , 0 , 0 , 0 ,,
     1.7     1.7
   -6.05   28.31
     1.7     1.7
   -5.26    29.1
Pier Skew, UpSta & Num, DnSta & Num=  ,5026.3, 2 ,5026.3, 2 , 0 , 0 , 0 ,,
     1.7     1.7
   -3.36   28.33
     1.7     1.7
   -2.57   29.12
Abutment Skew #Up #Dn= , 2 , 2
    4866  4872.6
    30.9   11.76
    4866  4872.6
   31.69   12.55
Abutment Skew #Up #Dn= , 2 , 2
    5071 5097.39
   12.13   27.27
    5071 5097.39
   12.92   28.06
BR Coef= 1 , 1 , 0 ,1.25, 0 ,,,.8,0,2,0,
WSPro=,,,, 1 ,,,, 0 ,,,, 0 ,,,,-1 ,-1 ,-1 , 0 , 0 , 0 , 0 , 0
BR U #Sta/Elev= 77
  4054.8      45  4254.8    41.7  4374.8    41.5  4404.8    36.9  4514.8    35.4
  4534.8    36.4  4544.8    38.3  4554.8      39  4658.8    38.8  4738.8    38.7
  4746.6    36.9  4766.6      32  4796.6    31.2  4826.6    31.9    4832    31.5
    4842    30.3  4864.3   32.11  4865.2   32.18  4865.3   32.18  4865.9   31.81
    4866   31.51 4866.11   31.17  4866.2    30.9  4867.9   25.75  4872.5    11.8
  4872.6   11.76  4887.1    6.67  4890.8    5.23  4893.2    5.33  4901.9    5.67
  4902.4    6.69  4904.2    6.81  4918.2    7.02  4918.4    7.02  4919.1    7.03
 4920.19    6.54  4920.3    6.49 4920.41    6.44  4922.1    5.67  4941.8    4.92
    4946    3.28  4952.6     .81  4956.3    -.07  4972.5   -3.53  4974.7      -4
  4981.2  -12.03  4990.2   -9.88  5007.8  -11.78  5026.3   -1.91  5036.4   -2.16
  5041.8    -2.3  5047.5     .85  5049.6    1.46  5061.6     7.4  5070.9   12.08
    5071   12.13  5072.7   12.23  5073.4   14.41  5075.4   14.37  5075.6   21.72
  5090.3   22.16  5096.7    26.9  5096.9   27.05 5097.19   27.27  5097.3   27.35
  5097.4   27.42  5099.5   28.98 5113.19   30.48  5113.3    30.5 5113.41   30.51
  5119.9   31.22  5132.2   31.51  5445.5      39    5536    41.5    5656    43.3
    5696    43.4  5715.4    44.3
BR U #Mann= 4
  4054.8      .2  4864.3     .12  4919.1     .04  5075.6      .2
BR U Banks=4919.1,5075.6
BR D #Sta/Elev= 77
  4054.8   45.79  4254.8   42.49  4374.8   42.29  4404.8   37.69  4514.8   36.19
  4534.8   37.19  4544.8   39.09  4554.8   39.79  4658.8   39.59  4738.8   39.49
  4746.6   37.69  4766.6   32.79  4796.6   31.99  4826.6   32.69    4832   32.29
    4842   31.09  4864.3    32.9  4865.2   32.97  4865.3   32.97  4865.9    32.6
    4866    32.3 4866.11   31.96  4866.2   31.69  4867.9   26.54  4872.5   12.59
  4872.6   12.55  4887.1    7.46  4890.8    6.02  4893.2    6.12  4901.9    6.46
  4902.4    7.48  4904.2     7.6  4918.2    7.81  4918.4    7.81  4919.1    7.82
 4920.19    7.33  4920.3    7.28 4920.41    7.23  4922.1    6.46  4941.8    5.71
    4946    4.07  4952.6     1.6  4956.3     .72  4972.5   -2.74  4974.7   -3.21
  4981.2  -11.24  4990.2   -9.09  5007.8  -10.99  5026.3   -1.12  5036.4   -1.37
  5041.8   -1.51  5047.5    1.64  5049.6    2.25  5061.6    8.19  5070.9   12.87
    5071   12.92  5072.7   13.02  5073.4    15.2  5075.4   15.16  5075.6   22.51
  5090.3   22.95  5096.7   27.69  5096.9   27.84 5097.19   28.06  5097.3   28.14
  5097.4   28.21  5099.5   29.77 5113.19   31.27  5113.3   31.29 5113.41    31.3
  5119.9   32.01  5132.2    32.3  5445.5   39.79    5536   42.29    5656   44.09
    5696   44.19  5715.4   45.09
BR D #Mann= 4
  4054.8      .2  4864.3     .12  4919.1     .04  5075.6      .2
BR D Banks=4919.1,5075.6
BC Design=,, 0 ,, 0 ,,,,,,
BC HTab HWMax=45.2

Type RM Length L Ch R = 1 ,111410.5,533.9,533.9,533.9
BEGIN DESCRIPTION:
Downstream Section of Bridge/Culvert/Weir
END DESCRIPTION:
XS GIS Cut Line= 6
      3121723.91     13844063.81      3122251.84     13843725.39
      3122321.59     13843626.12      3122380.62      13843518.8
      3122449.54     13843283.19      3122485.54     13842740.65
#Sta/Elev= 30
  4054.8    45.8  4374.8    42.3  4404.8    37.7  4514.8    36.2  4554.8    39.8
  4738.8    39.5  4766.6    32.8  4826.6    32.7    4842    31.1  4864.3   32.91
  4865.9   32.61  4872.5    12.6  4890.8    6.03  4919.1    7.83  4941.8    5.72
  4952.6    1.61  4974.7    -3.2  4981.2  -11.23  4990.2   -9.08  5007.8  -10.98
  5026.3   -1.11  5041.8    -1.5  5072.7   13.03  5073.4   15.21  5075.4   15.17
  5075.6   22.52  5090.3   22.96  5099.5   29.78  5119.9   32.02  5715.4    45.1
#Mann= 4 ,-1 , 0
  4054.8      .2       0  4864.3     .12       0  4919.1     .04       0
  5075.6      .2       0
#XS Ineff= 2 , 0
            4857    32.2    5106            32.2
Permanent Ineff=
       F       F
Bank Sta=4919.1,5075.6
XS Rating Curve= 0
Exp/Cntr=.5,.3

Type RM Length L Ch R = 1 ,110876.6,77.6,77.6,77.6
BEGIN DESCRIPTION:
Upstream Section of Bridge/Culvert/Weir
END DESCRIPTION:
XS GIS Cut Line= 6
      3122458.92     13844544.34      3122733.75     13844211.44
      3122814.45     13843904.08      3122754.41     13843650.76
      3122547.84     13843299.82      3122610.82     13842752.05
#Sta/Elev= 30
  3990.2   44.29  4040.2   40.59  4080.2   30.89  4100.2   29.49  4250.2   29.99
    4374   35.09  4603.8   37.79  4733.5   33.58  4839.6   27.64  4847.1   24.39
  4867.2   14.93  4867.5   12.92  4911.8   11.61  4913.1     5.1  4936.8    2.88
  4938.6    -.21    4944   -1.89  4991.9   -9.67  5019.9  -10.43  5054.8   -2.43
  5062.6     .98  5065.4    6.64    5071    8.55  5096.9    9.45  5125.1    16.2
  5173.6    27.1    5547   31.49    5637   36.29    5717   43.79  5958.7   45.49
#Mann= 5 ,-1 , 0
  3990.2      .2       0  4847.1      .1       0  4936.8     .04       0
    5071     .12       0  5125.1      .2       0
#XS Ineff= 2 , 0
            4835    29.7    5155            27.1
Permanent Ineff=
       F       F
Bank Sta=4936.8,5071
XS Rating Curve= 0
Exp/Cntr=.5,.3