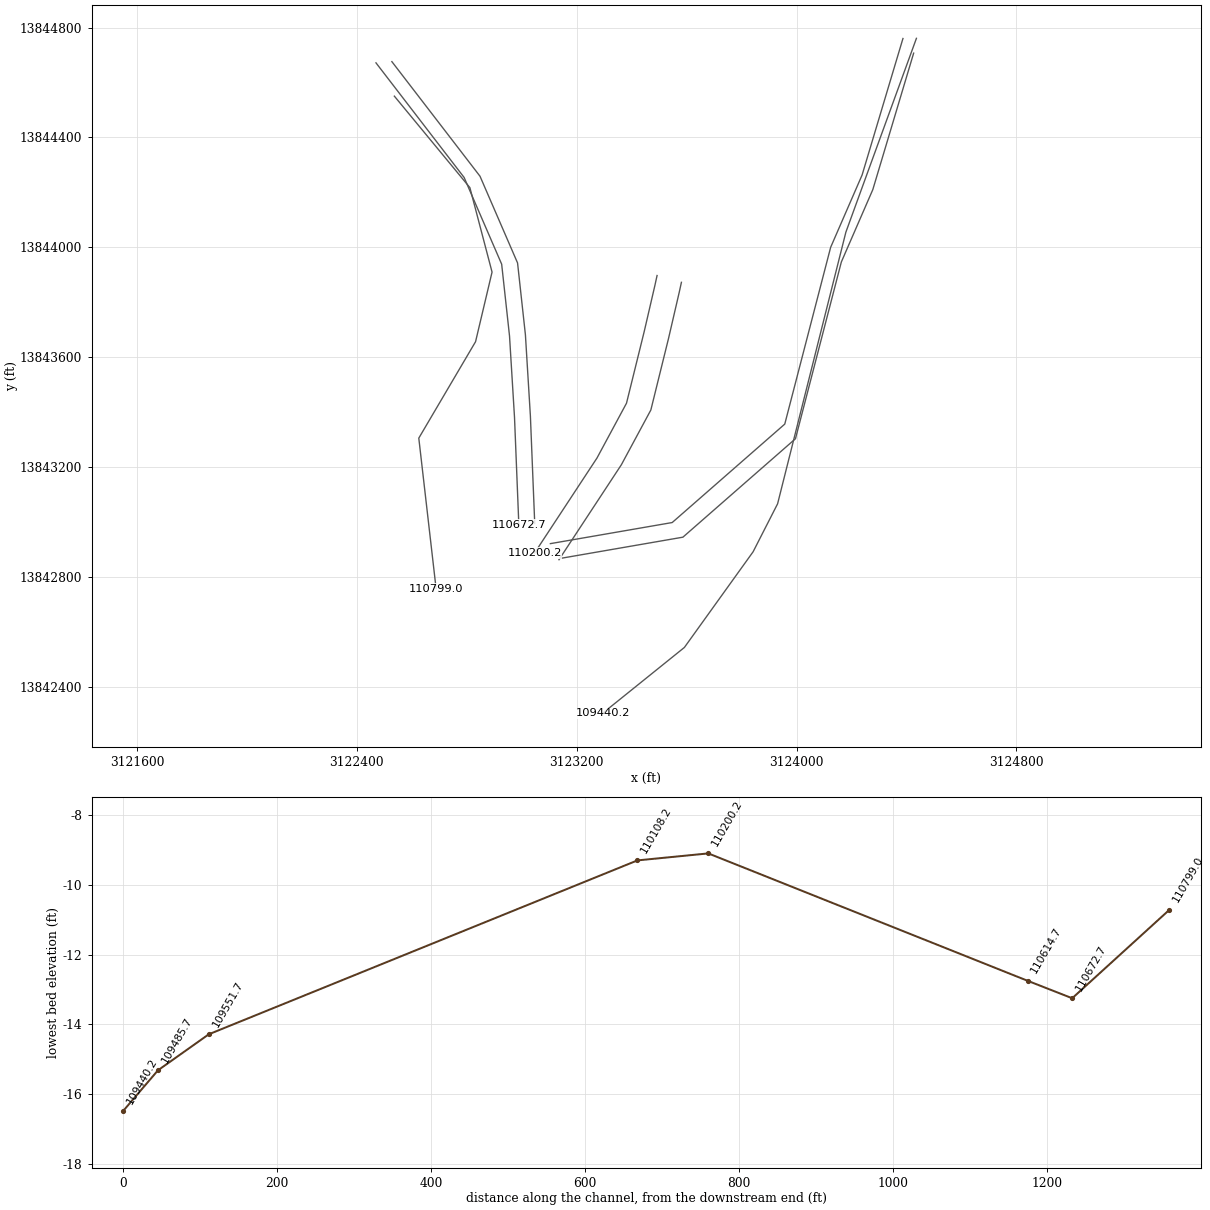
HEC-RAS study W100-00-00.prj: W100-00-00

--- W100-00-00.g01 (geometry) --- (continued)

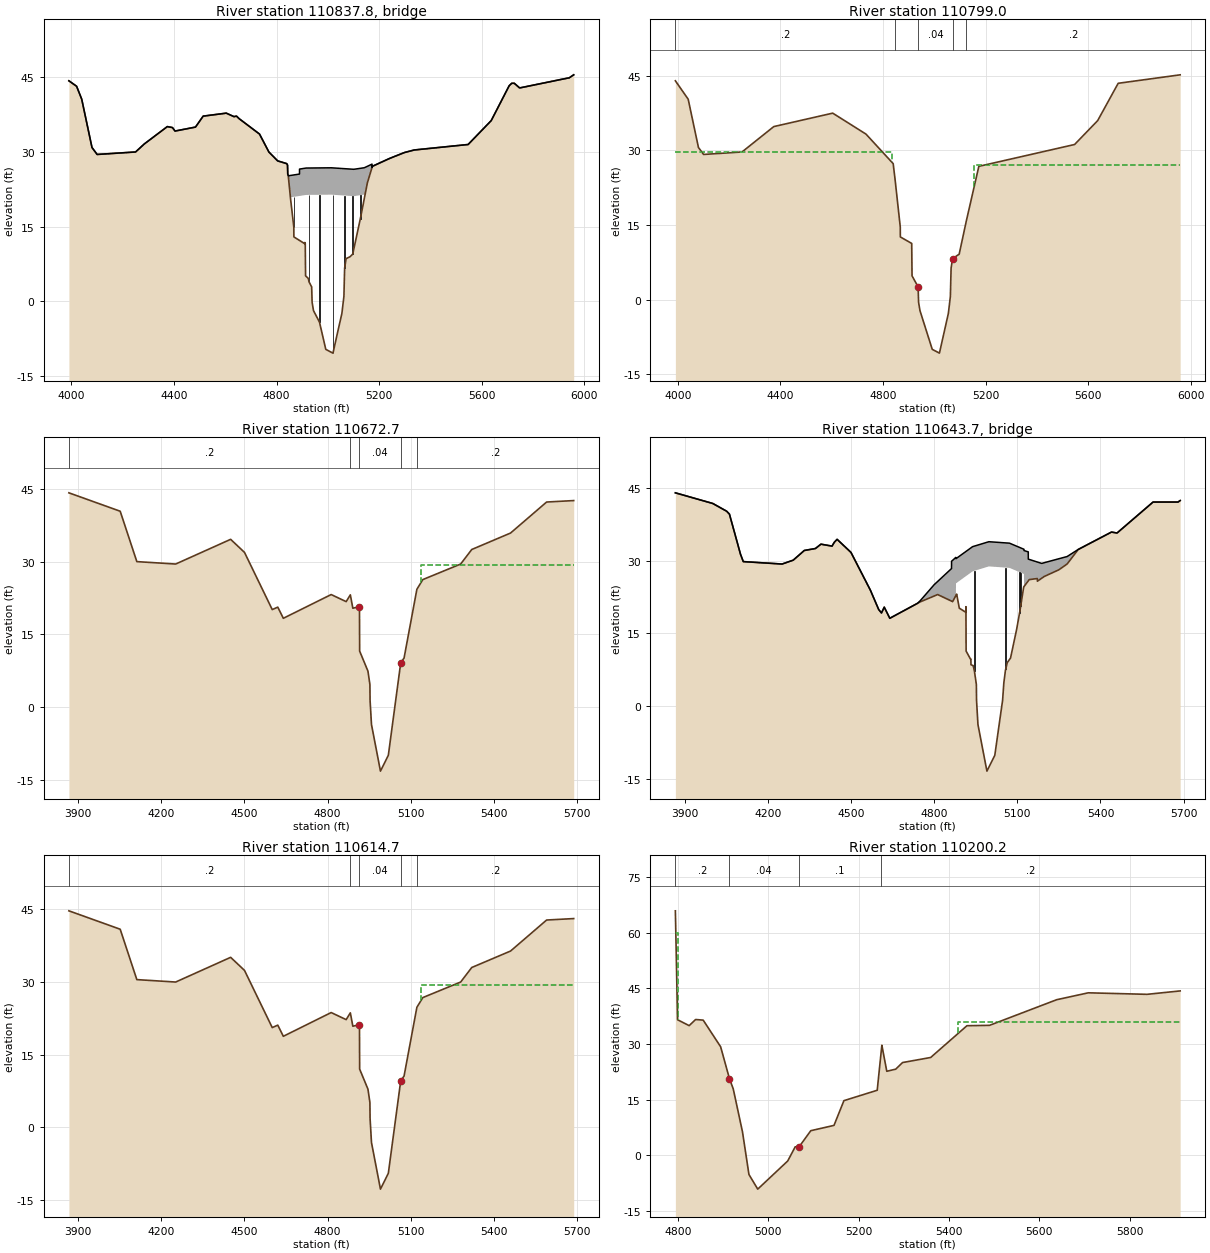
Type RM Length L Ch R = 3 ,110837.8,,,
BEGIN DESCRIPTION:
MILAM
Structure ID: WOO-22
END DESCRIPTION:
Bridge Culvert--1,0,-1,-1, 0
Deck Dist Width WeirC Skew NumUp NumDn MinLoCord MaxHiCord MaxSubmerge Is_Ogee
10,57.6,2.6,0, 50, 50, , , .95, 0, 1,1,,
  3990.2  4020.2  4040.2  4080.2  4100.2  4250.2    4284    4374    4394    4404
  4483.8  4513.8  4603.8  4633.8  4643.8  4653.8  4733.5  4770.1  4804.3  4839.6
  4842.7  4843.6  4846.1  4846.3  4854.2 4889.39  4889.5  4915.3  5013.5  5101.1
 5141.89    5142  5154.2 5172.09  5172.2 5172.31  5173.6  5238.7    5281  5299.6
    5337    5547    5637    5707    5717    5727    5747  5751.3  5941.3  5958.7
    44.3    43.2    40.6    30.9    29.5      30    31.6    35.1    34.9    34.2
      35    37.2    37.8    37.1    37.2    36.7    33.6   29.99   28.21   27.66
   27.36   25.56   25.21   25.21   25.28   25.56   26.56   26.77   26.82   26.52
   26.83   26.83   27.12   27.56   27.56    26.9   27.12   28.66   29.53    29.9
    30.4    31.5    36.3    43.3    43.8    43.8    42.9    42.9    44.9    45.5
    44.3    43.2    40.6    30.9    29.5      30    31.6    35.1    34.9    34.2
      35    37.2    37.8    37.1    37.2    36.7   33.59   29.98    28.2   27.65
   27.35   25.55   25.11   24.81   20.88   21.16   21.16   21.37   21.42   21.12
   21.43    20.6    23.8   26.85   26.87   26.89   27.11   28.65   29.52    29.9
    30.4    31.5    36.3    43.3    43.8    43.8    42.9    42.9    44.9    45.5
  3990.2  4020.2  4040.2  4080.2  4100.2  4250.2    4284    4374    4394    4404
  4483.8  4513.8  4603.8  4633.8  4643.8  4653.8  4733.5  4770.1  4804.3  4839.6
  4842.7  4843.6  4846.1  4846.3  4854.2 4889.39  4889.5  4915.3  5013.5  5101.1
 5141.89    5142  5154.2 5172.09  5172.2 5172.31  5173.6  5238.7    5281  5299.6
    5337    5547    5637    5707    5717    5727    5747  5751.3  5941.3  5958.7
    44.3    43.2    40.6    30.9    29.5      30    31.6    35.1    34.9    34.2
      35    37.2    37.8    37.1    37.2    36.7    33.6   29.99   28.21   27.66
   27.36   25.56   25.21   25.21   25.28   25.56   26.56   26.77   26.82   26.52
   26.83   26.83   27.12   27.56   27.56    26.9   27.12   28.66   29.53    29.9
    30.4    31.5    36.3    43.3    43.8    43.8    42.9    42.9    44.9    45.5
    44.2    43.1    40.5    30.8    29.4    29.9    31.5      35    34.8    34.1
    34.9    37.1    37.7      37    37.1    36.6   33.49   29.88    28.1   27.55
   27.25   25.45   25.01   24.71   20.78   21.06   21.06   21.27   21.32   21.02
   21.33    20.5    23.7   26.75   26.77   26.79   27.01   28.55   29.42    29.8
    30.3    31.4    36.2    43.2    43.7    43.7    42.8    42.8    44.8    45.4
Pier Skew, UpSta & Num, DnSta & Num=  ,4867.2, 2 ,4867.2, 2 , 0 , 0 , 0 ,,
       2       2
   11.91   21.99
       2       2
   11.81   21.89
Pier Skew, UpSta & Num, DnSta & Num=  ,4926.4, 2 ,4926.4, 2 , 0 , 0 , 0 ,,
       2       2
    2.82   22.38
       2       2
    2.72   22.28
Pier Skew, UpSta & Num, DnSta & Num=  ,4967.3, 2 ,4967.3, 2 , 0 , 0 , 0 ,,
       2       2
    -5.4    22.4
       2       2
    -5.5    22.3
Pier Skew, UpSta & Num, DnSta & Num=  ,5019.9, 2 ,5019.9, 2 , 0 , 0 , 0 ,,
       2       2
  -11.39    22.4
       2       2
  -11.49    22.3
Pier Skew, UpSta & Num, DnSta & Num=  ,5065.4, 2 ,5065.4, 2 , 0 , 0 , 0 ,,
       2       2
    3.63   22.24
       2       2
    3.53   22.14
Pier Skew, UpSta & Num, DnSta & Num=  ,5096.8, 2 ,5096.8, 2 , 0 , 0 , 0 ,,
       2       2
    8.42   22.14
       2       2
    8.32   22.04
Pier Skew, UpSta & Num, DnSta & Num=  ,5126.8, 2 ,5126.8, 2 , 0 , 0 , 0 ,,
       2       2
   15.38   22.32
       2       2
   15.28   22.22
Abutment Skew #Up #Dn= , 2 , 2
  5096.9 5142.09
    9.46   21.43
  5096.9 5142.09
    9.36   21.33
BR Coef= 1 , 1 , 0 ,1.25, 0 ,,,.8,0,2,0,
WSPro=,,,, 1 ,,,, 0 ,,,, 0 ,,,,-1 ,-1 ,-1 , 0 , 0 , 0 , 0 , 0
BR U #Sta/Elev= 96
  3990.2    44.3  4020.2    43.2  4040.2    40.6  4080.2    30.9  4100.2    29.5
  4250.2      30    4284    31.6    4374    35.1    4394    34.9    4404    34.2
  4483.8      35  4513.8    37.2  4603.8    37.8  4633.8    37.1  4643.8    37.2
  4653.8    36.7  4696.4   35.04  4713.7   34.36  4733.5   33.59  4733.6   33.58
    4770   29.99  4770.1   29.98  4804.3    28.2  4812.5   28.07  4812.9   28.07
  4839.6   27.65  4839.7   27.64  4839.8   27.63 4839.91   27.62    4840   27.61
  4840.5   27.56  4842.7   27.35  4843.6   25.55  4846.1   25.11  4846.3   24.81
  4847.1    24.4  4854.2   20.74  4867.2   14.94  4867.5   12.93 4889.39   12.23
  4889.5   12.23 4889.61   12.22  4897.2   11.98  4909.5   11.58  4910.2   11.81
  4911.8   11.62  4913.1    5.11  4915.3       5  4923.8    4.59  4926.4    3.92
  4936.8    2.89  4937.5    1.75  4938.6     -.2    4944   -1.88  4967.3   -4.18
  4991.9   -9.66  5013.5  -10.25  5019.9  -10.42  5036.8   -6.53  5054.8   -2.42
  5062.6     .99  5065.4    6.65    5071    8.56  5086.5    8.95  5096.7    9.46
  5096.8    9.46  5096.9    9.46  5101.1   10.47  5125.1   16.21  5126.8   16.62
 5141.89   20.57    5142    20.6  5142.1   20.63  5142.2   20.66  5154.2    23.8
 5172.09   26.85  5172.2   26.87 5172.31   26.89  5173.6   27.11  5212.6   28.03
  5238.6   28.64  5238.7   28.65    5257   29.03    5281   29.52  5299.6    29.9
    5337    30.4    5547    31.5    5637    36.3    5707    43.3    5717    43.8
    5727    43.8    5747    42.9  5751.3    42.9  5911.3    44.6  5941.3    44.9
  5958.7    45.5
BR U #Mann= 5
  3990.2      .2  4847.1      .1  4936.8     .04    5071     .12  5125.1      .2
BR U Banks=4936.8,5071
BR D #Sta/Elev= 96
  3990.2    44.2  4020.2    43.1  4040.2    40.5  4080.2    30.8  4100.2    29.4
  4250.2    29.9    4284    31.5    4374      35    4394    34.8    4404    34.1
  4483.8    34.9  4513.8    37.1  4603.8    37.7  4633.8      37  4643.8    37.1
  4653.8    36.6  4696.4   34.94  4713.7   34.26  4733.5   33.49  4733.6   33.48
    4770   29.89  4770.1   29.88  4804.3    28.1  4812.5   27.97  4812.9   27.97
  4839.6   27.55  4839.7   27.54  4839.8   27.53 4839.91   27.52    4840   27.51
  4840.5   27.46  4842.7   27.25  4843.6   25.45  4846.1   25.01  4846.3   24.71
  4847.1    24.3  4854.2   20.64  4867.2   14.84  4867.5   12.83 4889.39   12.13
  4889.5   12.13 4889.61   12.12  4897.2   11.88  4909.5   11.48  4910.2   11.71
  4911.8   11.52  4913.1    5.01  4915.3     4.9  4923.8    4.49  4926.4    3.82
  4936.8    2.79  4937.5    1.65  4938.6     -.3    4944   -1.98  4967.3   -4.28
  4991.9   -9.76  5013.5  -10.35  5019.9  -10.52  5036.8   -6.63  5054.8   -2.52
  5062.6     .89  5065.4    6.55    5071    8.46  5086.5    8.85  5096.7    9.36
  5096.8    9.36  5096.9    9.36  5101.1   10.37  5125.1   16.11  5126.8   16.52
 5141.89   20.47    5142    20.5  5142.1   20.53  5142.2   20.56  5154.2    23.7
 5172.09   26.75  5172.2   26.77 5172.31   26.79  5173.6   27.01  5212.6   27.93
  5238.6   28.54  5238.7   28.55    5257   28.93    5281   29.42  5299.6    29.8
    5337    30.3    5547    31.4    5637    36.2    5707    43.2    5717    43.7
    5727    43.7    5747    42.8  5751.3    42.8  5911.3    44.5  5941.3    44.8
  5958.7    45.4
BR D #Mann= 5
  3990.2      .2  4847.1      .1  4936.8     .04    5071     .12  5125.1      .2
BR D Banks=4936.8,5071
BC Design=,, 0 ,, 0 ,,,,,,
BC HTab HWMax=45.49

Type RM Length L Ch R = 1 ,110799.0,126.3,126.3,126.3
BEGIN DESCRIPTION:
Downstream Section of Bridge/Culvert/Weir
END DESCRIPTION:
XS GIS Cut Line= 6
      3122536.29     13844550.29      3122811.13      13844217.4
      3122891.83     13843910.04      3122831.79     13843656.72
      3122625.22     13843305.78      3122688.19       13842758.
#Sta/Elev= 30
  3990.2      44  4040.2    40.3  4080.2    30.6  4100.2    29.2  4250.2    29.7
    4374    34.8  4603.8    37.5  4733.5   33.29  4839.6   27.35  4847.1    24.1
  4867.2   14.64  4867.5   12.63  4911.8   11.32  4913.1    4.81  4936.8    2.59
  4938.6     -.5    4944   -2.18  4991.9   -9.96  5019.9  -10.72  5054.8   -2.72
  5062.6     .69  5065.4    6.35    5071    8.26  5096.9    9.16  5125.1   15.91
  5173.6   26.81    5547    31.2    5637      36    5717    43.5  5958.7    45.2
#Mann= 5 ,-1 , 0
  3990.2      .2       0  4847.1      .1       0  4936.8     .04       0
    5071     .12       0  5125.1      .2       0
#XS Ineff= 2 , 0
            4835    29.7    5155            27.1
Permanent Ineff=
       F       F
Bank Sta=4936.8,5071
XS Rating Curve= 0
Exp/Cntr=.5,.3

Type RM Length L Ch R = 1 ,110672.7,58,58,58
BEGIN DESCRIPTION:
Upstream Section of Bridge/Culvert/Weir
END DESCRIPTION:
XS GIS Cut Line= 6
      3122469.42     13844671.45      3122790.19     13844254.35
      3122926.81      13843938.8      3122955.39     13843677.39
      3122973.56      13843381.1      3122989.28     13842990.92
#Sta/Elev= 30
  3866.9    44.2  4051.9    40.4  4111.9      30  4251.9    29.5  4450.2    34.6
  4500.2    31.9  4600.2    20.1  4620.2    20.6  4640.2    18.3  4812.7    23.2
  4866.8   21.74  4881.9   23.14  4890.9   20.38  4914.8   20.69  4915.4   11.53
  4945.4    7.39  4952.4    4.64    4953    1.38  4958.1   -3.63  4990.5  -13.25
  5018.9   -9.98  5063.6    9.13  5075.6   10.09  5121.8   24.28  5143.2   26.29
  5279.7    29.5  5319.7    32.5  5459.7    35.9  5589.7    42.3  5687.4    42.6
#Mann= 5 ,-1 , 0
  3866.9      .2       0  4881.9     .08       0  4914.8     .04       0
  5063.6     .08       0  5121.8      .2       0
#XS Ineff= 2 , 0
          4890.9   20.18    5135            29.4
Permanent Ineff=
       F       F
Bank Sta=4914.8,5063.6
XS Rating Curve= 0
Exp/Cntr=.5,.3

Type RM Length L Ch R = 3 ,110643.7,,,
BEGIN DESCRIPTION:
TRAVIS STREET
Structure ID: WOO-21
END DESCRIPTION:
Bridge Culvert--1,0,-1,-1, 0
Deck Dist Width WeirC Skew NumUp NumDn MinLoCord MaxHiCord MaxSubmerge Is_Ogee
10,38,2.6,0, 51, 50, , , .95, 0, 1,1,,
  3866.9  4001.9  4051.9  4061.9  4101.9  4111.9  4251.9  4291.9  4331.9  4371.9
  4391.9  4431.9  4440.2  4450.2  4500.2  4570.2  4600.2  4610.2  4620.2  4640.2
    4740  4750.1  4800.4  4812.7 4862.79  4862.9  4866.8  4878.2 4878.81  4878.9
  4938.8  4997.5  5071.8    5124 5124.09  5124.2  5139.6 5139.71  5143.2  5172.1
  5172.6  5188.1  5196.8  5249.7  5279.7  5319.7  5439.7  5459.7  5589.7  5679.7
  5687.4
      44    41.8    40.2    39.6    31.3    29.8    29.3    30.1    32.1    32.5
    33.4      33    33.8    34.4    31.7    23.9    19.9    19.2    20.4    18.1
   21.19   21.74   25.05    25.7   28.37   29.87   30.07   30.67    30.4   30.41
   32.89   33.91   33.61   32.35   32.23   32.09   31.81   30.31   30.25   29.72
   29.71   29.43   29.57   30.39   30.85   32.31    35.9    35.7    42.1    42.1
    42.4
      44    41.8    40.2    39.6    31.3    29.8    29.3    30.1    32.1    32.5
    33.4      33    33.8    34.4    31.7    23.9    19.9    19.2    20.4    18.1
   21.18   21.49    22.7      23   21.65   21.65   21.54   22.75   22.82   25.31
   27.79   28.81   28.51   27.25   27.13   24.64   25.82   25.82   26.09    26.3
   25.76   26.37   26.72    28.1    29.3    32.3    35.9    35.7    42.1    42.1
    42.4
  3866.9  4001.9  4051.9  4061.9  4101.9  4111.9  4251.9  4291.9  4331.9  4371.9
  4391.9  4431.9  4440.2  4450.2  4500.2  4570.2  4600.2  4610.2  4620.2  4640.2
  4750.1  4800.4  4812.7 4862.79  4862.9  4866.8  4878.2 4878.81  4878.9  4938.8
  4997.5  5071.8    5124 5124.09  5124.2  5139.6 5139.71  5143.2  5172.1  5172.6
  5188.1  5196.8  5249.7  5279.7  5319.7  5439.7  5459.7  5589.7  5679.7  5687.4
   44.61   42.41   40.81   40.21   31.91   30.41   29.91   30.71   32.71   33.11
   34.01   33.61   34.41   35.01   32.31   24.51   20.51   19.81   21.01   18.71
    22.1   25.05    25.7   28.37   29.87   30.07   30.67    30.4   30.41   32.89
   33.91   33.61   32.35   32.23   32.09   31.81   30.31   30.25   29.72   29.71
   29.43   29.57   30.39   30.85   32.91   36.51   36.31   42.71   42.71   43.01
   44.61   42.41   40.81   40.21   31.91   30.41   29.91   30.71   32.71   33.11
   34.01   33.61   34.41   35.01   32.31   24.51   20.51   19.81   21.01   18.71
    22.1   23.31   23.61   22.26   22.26   22.15   23.36   23.43   25.92    28.4
   29.42   29.12   27.86   27.74   25.25   26.43   26.43    26.7   26.91   26.37
   26.98   27.33   28.71   29.91   32.91   36.51   36.31   42.71   42.71   43.01
Pier Skew, UpSta & Num, DnSta & Num=  ,4945.4, 2 ,4945.4, 2 , 0 , 0 , 0 ,,
       3       3
     5.6   28.93
       3       3
    6.21   29.54
Pier Skew, UpSta & Num, DnSta & Num=  ,5058, 2 ,5058, 2 , 0 , 0 , 0 ,,
       3       3
    6.03   29.57
       3       3
    6.64   30.18
Pier Skew, UpSta & Num, DnSta & Num=  ,5108.4, 2 ,5108.4, 2 , 0 , 0 , 0 ,,
     2.7     2.7
   17.83   28.66
     2.7     2.7
   18.44   29.27
Pier Skew, UpSta & Num, DnSta & Num=  ,5112.2, 2 ,5112.2, 2 , 0 , 0 , 0 ,,
     2.7     2.7
    19.1   28.57
     2.7     2.7
   19.71   29.18
Abutment Skew #Up #Dn= , 2 , 2
  4878.7    4891
   25.31   20.18
  4878.7    4891
   25.92   20.79
Abutment Skew #Up #Dn= , 2 , 2
  5075.7 5124.29
    9.92   27.13
  5075.7 5124.29
   10.53   27.74
BR Coef= 1 , 1 , 0 ,1.25, 0 ,,,.8,0,2,0,
WSPro=,,,, 1 ,,,, 0 ,,,, 0 ,,,,-1 ,-1 ,-1 , 0 , 0 , 0 , 0 , 0
BR U #Sta/Elev= 90
  3866.9      44  4001.9    41.8  4051.9    40.2  4061.9    39.6  4101.9    31.3
  4111.9    29.8  4251.9    29.3  4291.9    30.1  4331.9    32.1  4371.9    32.5
  4391.9    33.4  4431.9      33  4440.2    33.8  4450.2    34.4  4500.2    31.7
  4570.2    23.9  4600.2    19.9  4610.2    19.2  4620.2    20.4  4640.2    18.1
    4740   21.18    4750   21.49  4750.1   21.49  4800.4    22.7  4812.7      23
 4862.79   21.65  4862.9   21.65 4863.01   21.64  4866.8   21.54  4878.2   22.75
  4878.7    22.8 4878.81   22.82  4878.9   22.82  4881.4   23.09  4881.9   22.94
  4890.9   20.18    4891   20.18  4914.6   19.34  4914.8   20.49  4915.4   11.33
  4931.9    9.61  4932.5    9.65    4933    8.51  4938.8    8.38    4941    8.33
  4945.4    7.19  4952.4    4.44    4953    1.18  4958.1   -3.83  4990.5  -13.45
  4997.5  -12.64  5018.9  -10.18  5041.1    -1.2    5047    1.16  5051.4    4.72
  5057.2    7.35    5058    7.55  5063.6    8.93  5071.8    9.59  5075.6    9.89
  5075.7    9.92  5097.6   15.81  5108.4   19.26  5112.2   20.57  5121.8   24.08
  5123.1   24.56    5124   24.63 5124.09   24.64  5124.2   24.64  5124.3   24.65
 5139.49   25.81  5139.6   25.82 5139.71   25.82  5143.2   26.09  5172.1    26.3
  5172.6   25.76  5188.1   26.37  5196.8   26.72  5196.9   26.72  5249.5    28.1
  5249.7    28.1  5279.6    29.3  5279.7    29.3  5319.7    32.3  5325.3   32.47
  5439.7    35.9  5459.7    35.7  5589.7    42.1  5679.7    42.1  5687.4    42.4
BR U #Mann= 5
  3866.9      .2  4881.9     .08  4914.8     .04  5063.6     .08  5121.8      .2
BR U Banks=4914.8,5063.6
BR D #Sta/Elev= 90
  3866.9   44.61  4001.9   42.41  4051.9   40.81  4061.9   40.21  4101.9   31.91
  4111.9   30.41  4251.9   29.91  4291.9   30.71  4331.9   32.71  4371.9   33.11
  4391.9   34.01  4431.9   33.61  4440.2   34.41  4450.2   35.01  4500.2   32.31
  4570.2   24.51  4600.2   20.51  4610.2   19.81  4620.2   21.01  4640.2   18.71
    4740   21.79    4750    22.1  4750.1    22.1  4800.4   23.31  4812.7   23.61
 4862.79   22.26  4862.9   22.26 4863.01   22.25  4866.8   22.15  4878.2   23.36
  4878.7   23.41 4878.81   23.43  4878.9   23.43  4881.4    23.7  4881.9   23.55
  4890.9   20.79    4891   20.79  4914.6   19.95  4914.8    21.1  4915.4   11.94
  4931.9   10.22  4932.5   10.26    4933    9.12  4938.8    8.99    4941    8.94
  4945.4     7.8  4952.4    5.05    4953    1.79  4958.1   -3.22  4990.5  -12.84
  4997.5  -12.03  5018.9   -9.57  5041.1    -.59    5047    1.77  5051.4    5.33
  5057.2    7.96    5058    8.16  5063.6    9.54  5071.8    10.2  5075.6    10.5
  5075.7   10.53  5097.6   16.42  5108.4   19.87  5112.2   21.18  5121.8   24.69
  5123.1   25.17    5124   25.24 5124.09   25.25  5124.2   25.25  5124.3   25.26
 5139.49   26.42  5139.6   26.43 5139.71   26.43  5143.2    26.7  5172.1   26.91
  5172.6   26.37  5188.1   26.98  5196.8   27.33  5196.9   27.33  5249.5   28.71
  5249.7   28.71  5279.6   29.91  5279.7   29.91  5319.7   32.91  5325.3   33.08
  5439.7   36.51  5459.7   36.31  5589.7   42.71  5679.7   42.71  5687.4   43.01
BR D #Mann= 5
  3866.9      .2  4881.9     .08  4914.8     .04  5063.6     .08  5121.8      .2
BR D Banks=4914.8,5063.6
BC Design=,, 0 ,, 0 ,,,,,,
BC HTab HWMax=44.2

Type RM Length L Ch R = 1 ,110614.7,414.5,414.5,414.5
BEGIN DESCRIPTION:
Downstream Section of Bridge/Culvert/Weir
END DESCRIPTION:
XS GIS Cut Line= 6
      3122527.25      13844675.9      3122848.01     13844258.81
      3122984.63     13843943.26      3123013.21     13843681.85
      3123031.38     13843385.56      3123047.11     13842995.37
#Sta/Elev= 30
  3866.9    44.7  4051.9    40.9  4111.9    30.5  4251.9      30  4450.2    35.1
  4500.2    32.4  4600.2    20.6  4620.2    21.1  4640.2    18.8  4812.7    23.7
  4866.8   22.24  4881.9   23.64  4890.9   20.88  4914.8   21.19  4915.4   12.03
  4945.4    7.89  4952.4    5.14    4953    1.88  4958.1   -3.13  4990.5  -12.75
  5018.9   -9.48  5063.6    9.63  5075.6   10.59  5121.8   24.78  5143.2   26.79
  5279.7      30  5319.7      33  5459.7    36.4  5589.7    42.8  5687.4    43.1
#Mann= 5 ,-1 , 0
  3866.9      .2       0  4881.9     .08       0  4914.8     .04       0
  5063.6     .08       0  5121.8      .2       0
#XS Ineff= 2 , 0
          4890.9   20.79    5135            29.4
Permanent Ineff=
       F       F
Bank Sta=4914.8,5063.6
XS Rating Curve= 0
Exp/Cntr=.5,.3

Type RM Length L Ch R = 1 ,110200.2,92,92,92
BEGIN DESCRIPTION:
Upstream Section of Bridge/Culvert/Weir
END DESCRIPTION:
XS GIS Cut Line= 6
      3123492.33     13843897.52      3123484.66     13843862.41
      3123445.51     13843693.55       3123381.1     13843432.84
      3123273.74     13843233.47      3123046.68     13842887.96
#Sta/Elev= 30
    4794   65.91  4798.9   36.55  4824.5   34.96  4838.8   36.61  4855.6   36.45
  4894.2   29.27  4913.8   20.65  4922.1   17.93  4942.6    6.34  4956.9   -5.17
  4976.4   -9.11  5042.7   -1.53  5059.4    2.31  5067.3    2.18  5093.8    6.64
  5145.2    8.07  5167.2   14.74  5240.9   17.54  5249.9   28.15  5251.2   29.68
  5262.1   22.66  5281.9   23.23    5297   25.01  5359.3   26.38  5439.6   34.94
  5489.6   35.04  5638.3   41.95  5708.3   43.81  5838.3    43.4  5911.7   44.32
#Mann= 4 ,-1 , 0
    4794      .2       0  4913.8     .04       0  5067.3      .1       0
  5249.9      .2       0
#XS Ineff= 2 , 0
            4800      60    5420              36
Permanent Ineff=
       F       F
Bank Sta=4913.8,5067.3
XS Rating Curve= 0
Exp/Cntr=.5,.3

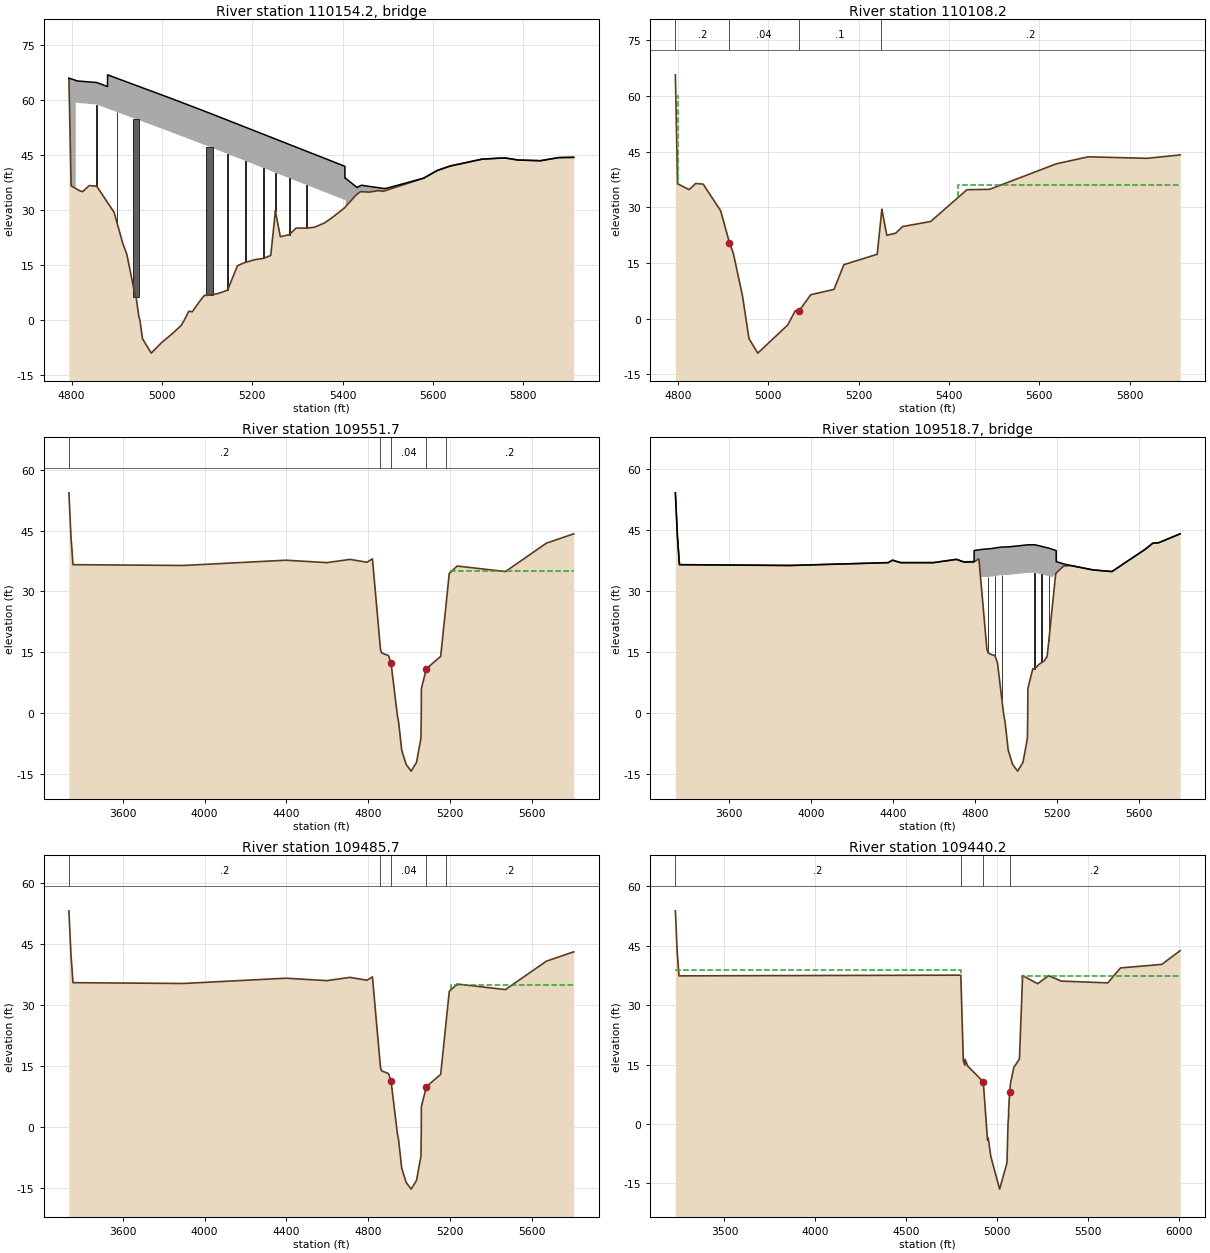
Type RM Length L Ch R = 3 ,110154.2,,,
BEGIN DESCRIPTION:
MAIN STREET
Structure ID: W00-20
END DESCRIPTION:
Bridge Culvert--1,0,-1,-1, 0
Deck Dist Width WeirC Skew NumUp NumDn MinLoCord MaxHiCord MaxSubmerge Is_Ogee
10,72,2.6,0, 34, 34, , , .95, 0, 1,1,,
    4794  4798.9    4809 4809.11  4809.2    4810  4855.6 4879.49  4879.6 4879.71
  5024.7  5105.5    5405 5405.11 5406.59  5406.7  5429.6  5431.8  5439.6  5441.8
  5459.6  5479.6  5489.6  5491.8  5498.2  5579.6  5609.6  5638.3  5708.3  5758.3
  5788.3  5838.3  5878.3  5911.7
      66   65.82   65.44   65.42   65.41   65.29   64.83   63.73   66.93   66.93
   60.29   56.48   41.97   38.77    38.7   38.69   36.42    36.2   36.67    36.8
   36.48   36.12   35.94    35.9      36   38.74   40.83   42.05   43.91   44.27
   43.68   43.49   44.34   44.41
      66   36.64   35.93   35.93   59.41   59.29   58.83   57.73   57.73   57.73
   51.09   47.28   32.77   32.77    32.7   30.94   34.09    34.3   35.03   35.02
   34.93   35.33   35.13   35.22   35.47   38.73   40.82   42.04    43.9   44.27
   43.68   43.49   44.34   44.41
    4794  4798.9    4809 4809.11  4809.2    4810  4855.6 4879.49  4879.6 4879.71
  5024.7  5105.5    5405 5405.11 5406.59  5406.7  5429.6  5431.8  5439.6  5441.8
  5459.6  5479.6  5489.6  5491.8  5498.2  5579.6  5609.6  5638.3  5708.3  5758.3
  5788.3  5838.3  5878.3  5911.7
      66   65.82   65.44   65.42   65.41   65.29   64.83   63.73   66.93   66.93
   60.29   56.48   41.97   38.77    38.7   38.69   36.42    36.2   36.67    36.8
   36.48   36.12   35.94    35.9      36   38.74   40.83   42.05   43.91   44.27
   43.68   43.49   44.34   44.41
    65.8   36.44   35.73   35.73   59.21   59.09   58.63   57.53   57.53   57.53
   50.89   47.08   32.57   32.57    32.5   30.74   33.89    34.1   34.83   34.82
   34.73   35.13   34.93   35.02   35.27   38.53   40.62   41.84    43.7   44.07
   43.48   43.29   44.14   44.21
Pier Skew, UpSta & Num, DnSta & Num=  ,4855.6, 2 ,4855.6, 2 , 0 , 0 , 0 ,,
       2       2
   35.35   59.84
       2       2
   35.15   59.64
Pier Skew, UpSta & Num, DnSta & Num=  ,4900.5, 2 ,4900.5, 2 , 0 , 0 , 0 ,,
       2       2
    25.1   57.83
       2       2
    24.9   57.63
Pier Skew, UpSta & Num, DnSta & Num=  ,4942.6, 2 ,4942.6, 2 , 0 , 0 , 0 ,,
    14.5    14.5
    -.47   56.19
    14.5    14.5
    -.67   55.99
Pier Skew, UpSta & Num, DnSta & Num=  ,5105.5, 2 ,5105.5, 2 , 0 , 0 , 0 ,,
    14.5    14.5
    5.75   48.62
    14.5    14.5
    5.55   48.42
Pier Skew, UpSta & Num, DnSta & Num=  ,5145.2, 2 ,5145.2, 2 , 0 , 0 , 0 ,,
       2       2
    7.12   46.42
       2       2
    6.92   46.22
Pier Skew, UpSta & Num, DnSta & Num=  ,5184.6, 2 ,5184.6, 2 , 0 , 0 , 0 ,,
       2       2
    14.7   44.52
       2       2
    14.5   44.32
Pier Skew, UpSta & Num, DnSta & Num=  ,5224.3, 2 ,5224.3, 2 , 0 , 0 , 0 ,,
       2       2
   15.81    42.6
       2       2
   15.61    42.4
Pier Skew, UpSta & Num, DnSta & Num=  ,5251.2, 2 ,5251.2, 2 , 0 , 0 , 0 ,,
       2       2
   27.59    41.3
       2       2
   27.39    41.1
Pier Skew, UpSta & Num, DnSta & Num=  ,5281.9, 2 ,5281.9, 2 , 0 , 0 , 0 ,,
       2       2
   22.29    39.8
       2       2
   22.09    39.6
Pier Skew, UpSta & Num, DnSta & Num=  ,5320.7, 2 ,5320.7, 2 , 0 , 0 , 0 ,,
       2       2
   24.11   37.91
       2       2
   23.91   37.71
Abutment Skew #Up #Dn= , 2 , 2
    4809  4838.9
   59.41    36.7
    4809  4838.9
   59.21    36.5
Abutment Skew #Up #Dn= , 2 , 2
  5359.4 5406.79
   26.48    32.7
  5359.4 5406.79
   26.28    32.5
BR Coef= 1 , 1 , 0 ,1.25, 0 ,,,.8,0,2,0,
WSPro=,,,, 1 ,,,, 0 ,,,, 0 ,,,,-1 ,-1 ,-1 , 0 , 0 , 0 , 0 , 0
BR U #Sta/Elev= 83
    4794      66  4798.9   36.64    4809   35.93 4809.11   35.93  4809.2   35.92
    4810   35.86  4818.9   35.24  4824.5   35.05  4838.8    36.7  4838.9    36.7
  4855.5   36.54  4855.6   36.54 4879.49    32.1  4879.6   32.08 4879.71   32.06
  4894.2   29.36  4900.5   26.54  4913.8   20.74  4922.1   18.02  4937.3    8.82
  4939.1    7.73  4942.6    6.43  4948.8     .96  4951.2    -.02  4956.9   -5.08
  4976.4   -9.02  4998.2   -6.27  5023.1    -3.7  5024.7   -3.52  5042.7   -1.44
  5048.7    -.18  5059.4     2.4  5067.3    2.27  5081.5    4.78  5093.8    6.73
    5104    6.78  5105.5    6.79  5125.7    7.29  5145.2    8.16  5167.2   14.83
  5184.6   15.75  5206.3    16.5  5210.6   16.58  5224.3   16.83  5240.9   17.63
  5249.9   28.24  5251.2   29.77  5262.1   22.75  5281.9   23.32    5297    25.1
  5320.7   25.11  5337.7   25.34  5359.3   26.47  5359.4   26.48  5374.7   27.76
  5404.7   30.66 5404.89   30.69    5405    30.7 5405.11   30.72 5406.59   30.93
  5406.7   30.94  5406.8   30.96  5406.9   30.97  5409.6   31.35  5429.6   34.09
  5431.8    34.3  5439.6   35.03  5441.8   35.02  5459.6   34.93  5479.6   35.33
  5489.6   35.13  5491.8   35.22  5498.2   35.47  5579.6   38.73  5609.6   40.82
  5638.3   42.04  5708.3    43.9  5755.1   44.25  5758.3   44.27  5788.3   43.68
  5838.3   43.49  5878.3   44.34  5911.7   44.41
BR U #Mann= 4
    4794      .2  4913.8     .04  5067.3      .1  5249.9      .2
BR U Banks=4913.8,5067.3
BR D #Sta/Elev= 83
    4794    65.8  4798.9   36.44    4809   35.73 4809.11   35.73  4809.2   35.72
    4810   35.66  4818.9   35.04  4824.5   34.85  4838.8    36.5  4838.9    36.5
  4855.5   36.34  4855.6   36.34 4879.49    31.9  4879.6   31.88 4879.71   31.86
  4894.2   29.16  4900.5   26.34  4913.8   20.54  4922.1   17.82  4937.3    8.62
  4939.1    7.53  4942.6    6.23  4948.8     .76  4951.2    -.22  4956.9   -5.28
  4976.4   -9.22  4998.2   -6.47  5023.1    -3.9  5024.7   -3.72  5042.7   -1.64
  5048.7    -.38  5059.4     2.2  5067.3    2.07  5081.5    4.58  5093.8    6.53
    5104    6.58  5105.5    6.59  5125.7    7.09  5145.2    7.96  5167.2   14.63
  5184.6   15.55  5206.3    16.3  5210.6   16.38  5224.3   16.63  5240.9   17.43
  5249.9   28.04  5251.2   29.57  5262.1   22.55  5281.9   23.12    5297    24.9
  5320.7   24.91  5337.7   25.14  5359.3   26.27  5359.4   26.28  5374.7   27.56
  5404.7   30.46 5404.89   30.49    5405    30.5 5405.11   30.52 5406.59   30.73
  5406.7   30.74  5406.8   30.76  5406.9   30.77  5409.6   31.15  5429.6   33.89
  5431.8    34.1  5439.6   34.83  5441.8   34.82  5459.6   34.73  5479.6   35.13
  5489.6   34.93  5491.8   35.02  5498.2   35.27  5579.6   38.53  5609.6   40.62
  5638.3   41.84  5708.3    43.7  5755.1   44.05  5758.3   44.07  5788.3   43.48
  5838.3   43.29  5878.3   44.14  5911.7   44.21
BR D #Mann= 4
    4794      .2  4913.8     .04  5067.3      .1  5249.9      .2
BR D Banks=4913.8,5067.3
BC Design=,, 0 ,, 0 ,,,,,,
BC HTab HWMax=65.91

Type RM Length L Ch R = 1 ,110108.2,556.5,556.5,556.5
BEGIN DESCRIPTION:
Downstream Section of Bridge/Culvert/Weir
END DESCRIPTION:
XS GIS Cut Line= 6
      3123580.95     13843872.84      3123573.28     13843837.73
      3123534.13     13843668.87      3123469.72     13843408.16
      3123362.36     13843208.79      3123135.31     13842863.28
#Sta/Elev= 30
    4794   65.71  4798.9   36.35  4824.5   34.76  4838.8   36.41  4855.6   36.25
  4894.2   29.07  4913.8   20.45  4922.1   17.73  4942.6    6.14  4956.9   -5.37
  4976.4   -9.31  5042.7   -1.73  5059.4    2.11  5067.3    1.98  5093.8    6.44
  5145.2    7.87  5167.2   14.54  5240.9   17.34  5249.9   27.95  5251.2   29.48
  5262.1   22.46  5281.9   23.03    5297   24.81  5359.3   26.18  5439.6   34.74
  5489.6   34.84  5638.3   41.75  5708.3   43.61  5838.3    43.2  5911.7   44.12
#Mann= 4 ,-1 , 0
    4794      .2       0  4913.8     .04       0  5067.3      .1       0
  5249.9      .2       0
#XS Ineff= 2 , 0
            4800      60    5420              36
Permanent Ineff=
       F       F
Bank Sta=4913.8,5067.3
XS Rating Curve= 0
Exp/Cntr=.5,.3

Type RM Length L Ch R = 1 ,109551.7,66,66,66
BEGIN DESCRIPTION:
Upstream Section of Bridge/Culvert/Weir
END DESCRIPTION:
XS GIS Cut Line= 6
      3124387.16     13844760.11      3124238.52     13844263.41
      3124124.05      13844000.2      3123957.07     13843356.86
       3123547.4     13842998.58      3123104.14     13842921.83
#Sta/Elev= 30
  3337.8   54.29  3347.8   43.59  3357.8   36.59  3897.8   36.39  4397.8   37.69
  4597.8   37.09  4710.1   37.89  4793.1   37.19    4820   38.02  4859.3   15.67
  4865.3   14.84  4898.2    14.2  4910.7   12.42  4941.5    -.47  4947.9   -2.22
  4963.1   -9.13  4984.6  -12.63    5009  -14.28  5035.1  -12.14  5056.7   -6.21
  5058.4    -.65    5059    6.06  5083.3   10.96  5153.2   13.99  5178.1   26.07
  5195.1   34.43  5233.8   36.25  5469.6   34.89  5669.6   41.89  5802.8   44.19
#Mann= 5 ,-1 , 0
  3337.8      .2       0  4859.3      .1       0  4910.7     .04       0
  5083.3      .1       0  5178.1      .2       0
#XS Ineff= 2 , 0
            4815    36.8    5205              35
Permanent Ineff=
       F       F
Bank Sta=4910.7,5083.3
XS Rating Curve= 0
Exp/Cntr=.5,.3

Type RM Length L Ch R = 3 ,109518.7,,,
BEGIN DESCRIPTION:
FANNIN STREET
Structure ID: WOO-19
END DESCRIPTION:
Bridge Culvert--1,0,-1,-1, 0
Deck Dist Width WeirC Skew NumUp NumDn MinLoCord MaxHiCord MaxSubmerge Is_Ogee
10,46,2.6,0, 34, 34, , , .95, 0, 1,1,,
  3337.8  3347.8  3357.8  3897.8  4377.8  4397.8  4437.8  4597.8  4710.1  4750.1
    4760  4793.1 4796.49  4796.6    4820  4827.8  4856.9  4881.5  4931.2  4963.6
    5059  5092.3  5161.6  5178.1  5197.4 5197.51  5233.8  5268.5  5377.7  5469.6
  5629.6  5669.6  5697.8  5802.8
    54.2    43.5    36.5    36.3      37    37.6      37      37    37.8    37.1
   37.23   37.25   37.28   39.98   40.15   40.22   40.36   40.47   40.85   40.88
   41.39   41.41   40.57   40.29   39.96   37.26   36.69   36.29    35.2    34.8
    40.2    41.8    41.9    44.1
    54.2    43.5    36.5    36.3      37    37.6      37      37    37.8    37.1
    37.1    37.1    37.2   37.21   37.93   33.48   33.46   33.57   33.95   33.98
   34.49   34.51   33.67   33.39   34.45   34.45   36.16   36.28    35.2    34.8
    40.2    41.8    41.9    44.1
  3337.8  3347.8  3357.8  3897.8  4377.8  4397.8  4437.8  4597.8  4710.1  4750.1
    4760  4793.1 4796.49  4796.6    4820  4827.8  4856.9  4881.5  4931.2  4963.6
    5059  5092.3  5161.6  5178.1  5197.4 5197.51  5233.8  5268.5  5377.7  5469.6
  5629.6  5669.6  5697.8  5802.8
    54.2    43.5    36.5    36.3      37    37.6      37      37    37.8    37.1
   37.23   37.25   37.28   39.98   40.15   40.22   40.36   40.47   40.85   40.88
   41.39   41.41   40.57   40.29   39.96   37.26   36.69   36.29    35.2    34.8
    40.2    41.8    41.9    44.1
   53.52   42.82   35.82   35.62   36.32   36.92   36.32   36.32   37.12   36.42
   36.42   36.42   36.52   36.53   37.25    32.8   32.78   32.89   33.27    33.3
   33.81   33.83   32.99   32.71   33.77   33.77   35.48    35.6   34.52   34.12
   39.52   41.12   41.22   43.42
Pier Skew, UpSta & Num, DnSta & Num=  ,4865.3, 2 ,4865.3, 2 , 0 , 0 , 0 ,,
     2.5     2.5
   13.72   34.51
     2.5     2.5
   13.04   33.83
Pier Skew, UpSta & Num, DnSta & Num=  ,4898.2, 2 ,4898.2, 2 , 0 , 0 , 0 ,,
     2.5     2.5
   12.93   34.69
     2.5     2.5
   12.25   34.01
Pier Skew, UpSta & Num, DnSta & Num=  ,4931.6, 2 ,4931.6, 2 , 0 , 0 , 0 ,,
     2.5     2.5
    1.96   34.95
     2.5     2.5
    1.28   34.27
Pier Skew, UpSta & Num, DnSta & Num=  ,5091.6, 2 ,5091.6, 2 , 0 , 0 , 0 ,,
     2.5     2.5
    9.83   35.51
     2.5     2.5
    9.15   34.83
Pier Skew, UpSta & Num, DnSta & Num=  ,5126.8, 2 ,5126.8, 2 , 0 , 0 , 0 ,,
     2.5     2.5
   11.37   35.11
     2.5     2.5
   10.69   34.43
Pier Skew, UpSta & Num, DnSta & Num=  ,5161.4, 2 ,5161.4, 2 , 0 , 0 , 0 ,,
     2.5     2.5
   16.17   34.69
     2.5     2.5
   15.49   34.01
Abutment Skew #Up #Dn= , 2 , 2
  4827.5  4856.9
   33.53   16.87
  4827.5  4856.9
   32.85   16.19
Abutment Skew #Up #Dn= , 2 , 2
  5153.3 5196.89
   13.95   34.41
  5153.3 5196.89
   13.27   33.73
BR Coef= 1 , 1 , 0 ,1.25, 0 ,,,.8,0,2,0,
WSPro=,,,, 1 ,,,, 0 ,,,, 0 ,,,,-1 ,-1 ,-1 , 0 , 0 , 0 , 0 , 0
BR U #Sta/Elev= 74
  3337.8    54.2  3347.8    43.5  3357.8    36.5  3897.8    36.3  4377.8      37
  4397.8    37.6  4437.8      37  4597.8      37  4710.1    37.8  4750.1    37.1
    4760    37.1  4789.6    37.1  4793.1    37.1 4796.49    37.2  4796.6   37.21
 4796.71   37.21    4820   37.93  4827.5   33.65 4827.61   33.59  4827.7   33.53
  4827.8   33.48  4856.9   16.87  4859.1   15.61  4859.3   15.58  4865.3   14.75
  4881.5   14.34  4889.3   14.23  4898.2   14.11  4910.7   12.33  4931.2    3.68
  4931.6    3.51  4934.5    2.24  4941.5    -.56  4947.9   -2.31  4963.1   -9.22
  4963.6    -9.3  4984.6  -12.72    5009  -14.37  5035.1  -12.23  5056.7    -6.3
  5058.4    -.74    5059    5.97  5059.5    6.07    5065    7.21  5083.3   10.87
  5091.6   10.82  5092.3   10.86  5113.2   11.93  5126.8   12.42  5138.5   12.74
  5153.2    13.9  5153.3   13.95  5161.4   17.76  5161.6   17.86  5178.1   25.98
  5195.1   34.34 5196.69   34.41  5196.8   34.42  5196.9   34.42 5197.29   34.44
  5197.4   34.45 5197.51   34.45  5233.8   36.16  5268.2   36.27  5268.5   36.28
  5276.3    36.2  5376.3   35.21  5377.7    35.2  5379.6    35.2  5469.6    34.8
  5629.6    40.2  5669.6    41.8  5697.8    41.9  5802.8    44.1
BR U #Mann= 5
  3337.8      .2  4859.3      .1  4910.7     .04  5083.3      .1  5178.1      .2
BR U Banks=4910.7,5083.3
BR D #Sta/Elev= 74
  3337.8   53.52  3347.8   42.82  3357.8   35.82  3897.8   35.62  4377.8   36.32
  4397.8   36.92  4437.8   36.32  4597.8   36.32  4710.1   37.12  4750.1   36.42
    4760   36.42  4789.6   36.42  4793.1   36.42 4796.49   36.52  4796.6   36.53
 4796.71   36.53    4820   37.25  4827.5   32.97 4827.61   32.91  4827.7   32.85
  4827.8    32.8  4856.9   16.19  4859.1   14.93  4859.3    14.9  4865.3   14.07
  4881.5   13.66  4889.3   13.55  4898.2   13.43  4910.7   11.65  4931.2       3
  4931.6    2.83  4934.5    1.56  4941.5   -1.24  4947.9   -2.99  4963.1    -9.9
  4963.6   -9.98  4984.6   -13.4    5009  -15.05  5035.1  -12.91  5056.7   -6.98
  5058.4   -1.42    5059    5.29  5059.5    5.39    5065    6.53  5083.3   10.19
  5091.6   10.14  5092.3   10.18  5113.2   11.25  5126.8   11.74  5138.5   12.06
  5153.2   13.22  5153.3   13.27  5161.4   17.08  5161.6   17.18  5178.1    25.3
  5195.1   33.66 5196.69   33.73  5196.8   33.74  5196.9   33.74 5197.29   33.76
  5197.4   33.77 5197.51   33.77  5233.8   35.48  5268.2   35.59  5268.5    35.6
  5276.3   35.52  5376.3   34.53  5377.7   34.52  5379.6   34.52  5469.6   34.12
  5629.6   39.52  5669.6   41.12  5697.8   41.22  5802.8   43.42
BR D #Mann= 5
  3337.8      .2  4859.3      .1  4910.7     .04  5083.3      .1  5178.1      .2
BR D Banks=4910.7,5083.3
BC Design=,, 0 ,, 0 ,,,,,,
BC HTab HWMax=54.29

Type RM Length L Ch R = 1 ,109485.7,45.5,45.5,45.5
BEGIN DESCRIPTION:
Downstream Section of Bridge/Culvert/Weir
END DESCRIPTION:
XS GIS Cut Line= 6
       3124426.1     13844706.82      3124277.46     13844210.13
      3124162.99     13843946.92      3123996.01     13843303.58
      3123586.34      13842945.3      3123143.08     13842868.55
#Sta/Elev= 30
  3337.8   53.26  3347.8   42.56  3357.8   35.56  3897.8   35.36  4397.8   36.66
  4597.8   36.06  4710.1   36.86  4793.1   36.16    4820   36.99  4859.3   14.64
  4865.3   13.81  4898.2   13.17  4910.7   11.39  4941.5    -1.5  4947.9   -3.25
  4963.1  -10.16  4984.6  -13.66    5009  -15.31  5035.1  -13.17  5056.7   -7.24
  5058.4   -1.68    5059    5.03  5083.3    9.93  5153.2   12.96  5178.1   25.04
  5195.1    33.4  5233.8   35.22  5469.6   33.86  5669.6   40.86  5802.8   43.16
#Mann= 5 ,-1 , 0
  3337.8      .2       0  4859.3      .1       0  4910.7     .04       0
  5083.3      .1       0  5178.1      .2       0
#XS Ineff= 2 , 0
            4815    36.8    5205              35
Permanent Ineff=
       F       F
Bank Sta=4910.7,5083.3
XS Rating Curve= 0
Exp/Cntr=.5,.3

Type RM Length L Ch R = 1 ,109440.2,90,90,90
BEGIN DESCRIPTION:
Upstream Section of Bridge/Culvert/Weir
END DESCRIPTION:
XS GIS Cut Line= 6
      3124436.18      13844760.7      3124179.47      13844055.4
      3123930.99     13843066.86      3123841.91     13842892.27
      3123591.74     13842543.99      3123293.69     13842304.09
#Sta/Elev= 30
  3229.7   53.82  3239.7   43.45  3249.7   37.39  4799.8   37.57  4801.4   36.52
  4814.5    15.9  4822.8    14.8  4824.1   16.31  4838.6    14.6  4924.3   10.64
  4947.4   -4.08  4951.5   -3.59  4965.9   -8.25  5014.3  -16.48  5054.6   -9.86
  5060.7     .31  5063.7    1.93  5063.8    3.36  5069.6    8.16  5074.1   10.23
  5092.3   14.24  5123.3    16.4  5140.7   37.45  5223.6   35.41  5283.6   37.44
  5353.6   36.07  5609.6   35.62  5679.6    39.4  5906.7   40.29  6007.9   43.76
#Mann= 4 ,-1 , 0
  3229.7      .2       0  4799.8     .08       0  4924.3     .04       0
  5069.6      .2       0
#XS Ineff= 2 , 0
            4800    38.9    5140            37.3
Permanent Ineff=
       F       F
Bank Sta=4924.3,5069.6
XS Rating Curve= 0
Exp/Cntr=.5,.3