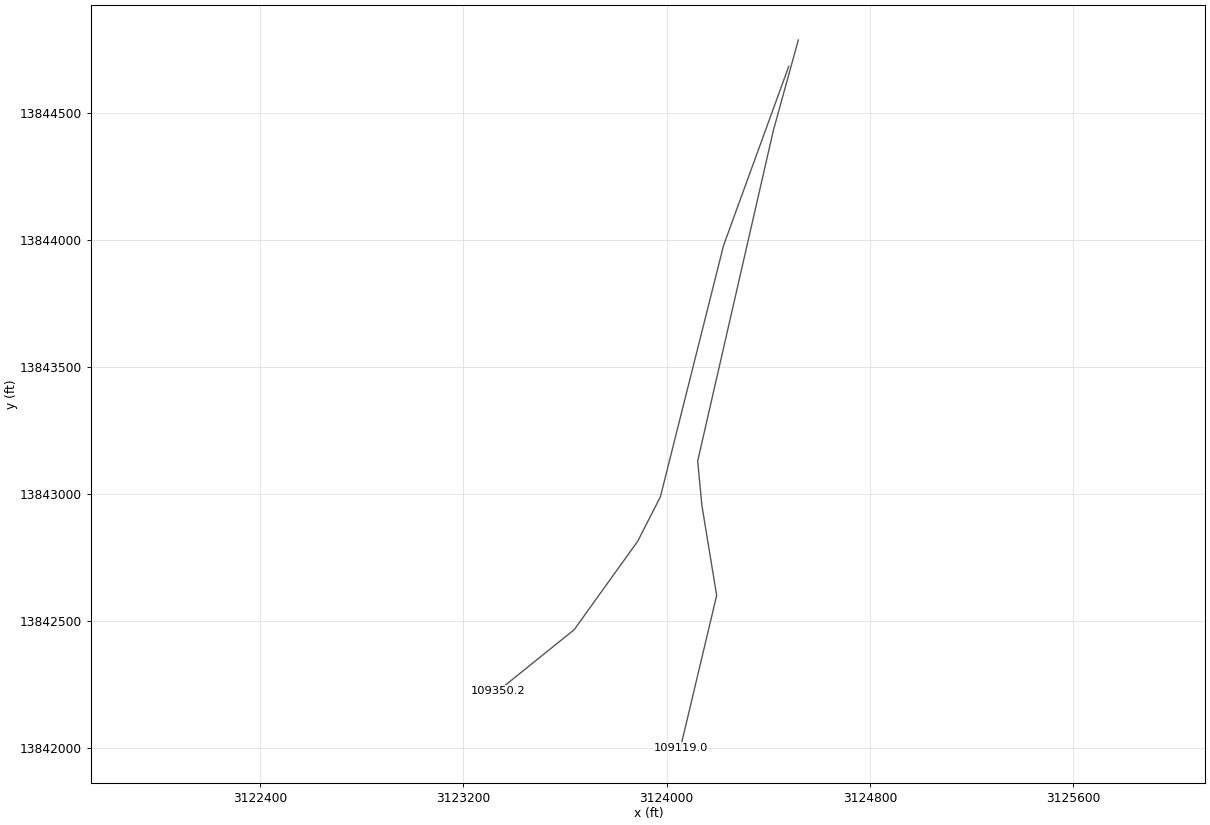
HEC-RAS study W100-00-00.prj: W100-00-00

--- W100-00-00.g01 (geometry) --- (continued)

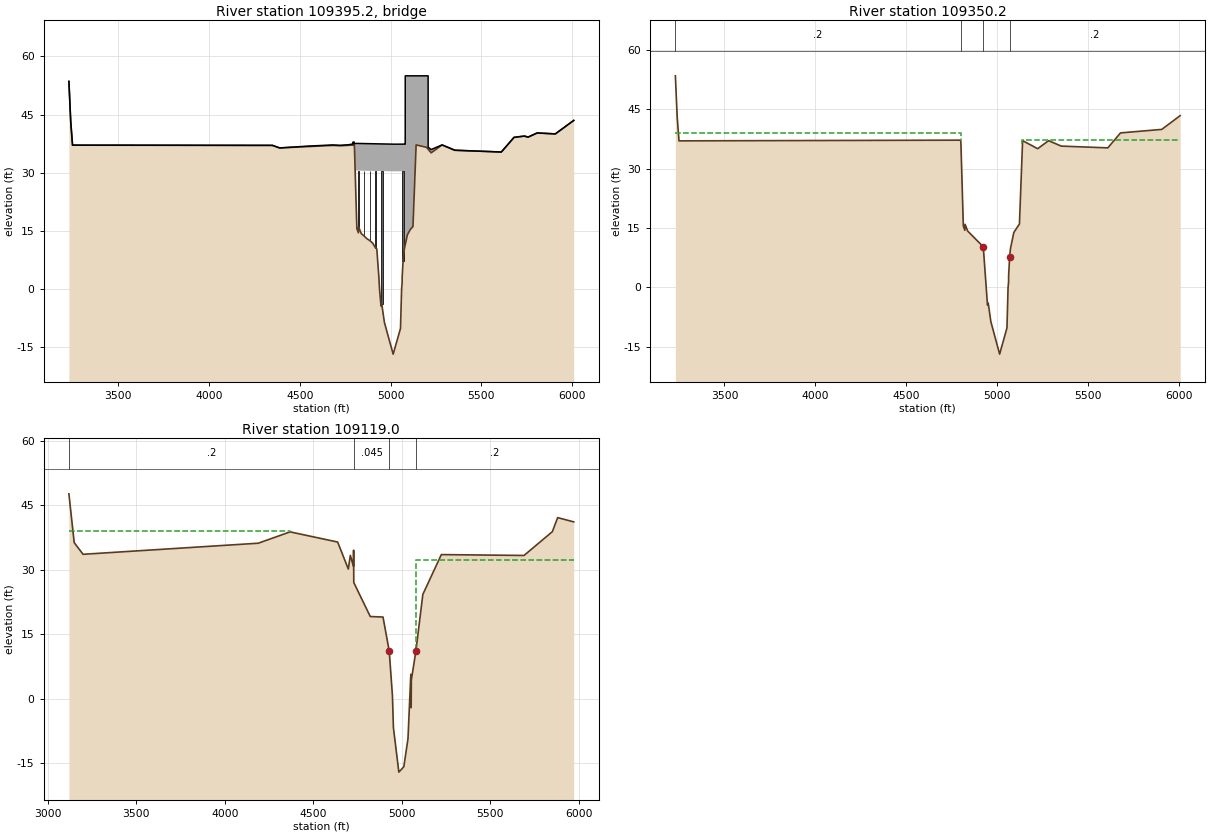
Type RM Length L Ch R = 3 ,109395.2,,,
BEGIN DESCRIPTION:
SAN JACINTO STREET
Structure ID: WOO-18
END DESCRIPTION:
Bridge Culvert--1,0,-1,-1, 0
Deck Dist Width WeirC Skew NumUp NumDn MinLoCord MaxHiCord MaxSubmerge Is_Ogee
10,70,2.6,0, 38, 38, , , .95, 0, 1,1,,
  3229.7  3239.7  3249.7  4349.7  4389.7  4550.9  4680.9  4719.3  4766.6    4792
  4792.4  4798.9  4799.8  4801.4 4810.01  4810.1  5019.6 5076.59  5076.7  5080.6
  5080.8  5092.3  5108.3  5123.3  5140.7  5197.7  5206.7  5206.8  5223.6  5283.6
  5353.6  5609.6  5679.6  5736.7  5756.7  5806.7  5906.7  6007.9
   53.56   43.19   37.13   37.07   36.41    36.9   37.18   37.09   37.22   37.43
   37.83   37.91   37.49    37.5   37.57   37.58   37.38   37.39   37.39   37.39
      55      55      55      55      55      55      55    36.6      36   37.19
   35.82   35.36   39.14   39.47    39.2   40.27   40.03    43.5
   53.56   43.19   37.13   37.07   36.41   36.77   37.06   36.98   37.09   37.13
   37.82    37.9   37.31   36.26   22.71   30.58   30.38   30.39   10.54    11.4
   11.45   13.98   15.36   16.14   37.19   36.57   36.08   36.07   35.15   37.18
   35.81   35.36   39.14   39.47    39.2   40.27   40.03    43.5
  3229.7  3239.7  3249.7  4349.7  4389.7  4550.9  4680.9  4719.3  4766.6    4792
  4792.4  4798.9  4799.8  4801.4 4810.01  4810.1  5019.6 5076.59  5076.7  5080.6
  5080.8  5092.3  5108.3  5123.3  5140.7  5197.7  5206.7  5206.8  5223.6  5283.6
  5353.6  5609.6  5679.6  5736.7  5756.7  5806.7  5906.7  6007.9
   53.56   43.19   37.13   37.07   36.41    36.9   37.18   37.09   37.22   37.43
   37.83   37.91   37.49    37.5   37.57   37.58   37.38   37.39   37.39   37.39
      55      55      55      55      55      55      55    36.6      36   37.19
   35.82   35.36   39.14   39.47    39.2   40.27   40.03    43.5
   53.42   43.05   36.99   36.93   36.27   36.63   36.92   36.84   36.95   36.99
   37.68   37.76   37.17   36.12   22.57   30.44   30.24   30.25    10.4   11.26
   11.31   13.84   15.22      16   37.05   36.43   35.94   35.93   35.01   37.04
   35.67   35.22      39   39.33   39.06   40.13   39.89   43.36
Pier Skew, UpSta & Num, DnSta & Num=  ,4824.1, 2 ,4824.1, 2 , 0 , 0 , 0 ,,
       2       2
   13.89   31.57
       2       2
   13.75   31.43
Pier Skew, UpSta & Num, DnSta & Num=  ,4854.8, 2 ,4854.8, 2 , 0 , 0 , 0 ,,
       2       2
   12.65   31.54
       2       2
   12.51    31.4
Pier Skew, UpSta & Num, DnSta & Num=  ,4886.2, 2 ,4886.2, 2 , 0 , 0 , 0 ,,
       2       2
   11.48   31.51
       2       2
   11.34   31.37
Pier Skew, UpSta & Num, DnSta & Num=  ,4916.6, 2 ,4916.6, 2 , 0 , 0 , 0 ,,
       2       2
    9.65   31.48
       2       2
    9.51   31.34
Pier Skew, UpSta & Num, DnSta & Num=  ,4951.5, 2 ,4951.5, 2 , 0 , 0 , 0 ,,
    12.5    12.5
   -6.87   31.45
    12.5    12.5
   -7.01   31.31
Pier Skew, UpSta & Num, DnSta & Num=  ,5068.9, 2 ,5068.9, 2 , 0 , 0 , 0 ,,
    12.5    12.5
      .1   31.39
    12.5    12.5
    -.04   31.25
Abutment Skew #Up #Dn= , 2 , 2
  4809.9  4814.5
   30.58   15.64
  4809.9  4814.5
   30.44    15.5
BR Coef= 1 , 1 , 0 ,1.25, 0 ,,,.8,0,2,0,
WSPro=,,,, 1 ,,,, 0 ,,,, 0 ,,,,-1 ,-1 ,-1 , 0 , 0 , 0 , 0 , 0
BR U #Sta/Elev= 79
  3229.7   53.56  3239.7   43.19  3249.7   37.13  4349.7   37.07  4389.7   36.41
  4550.9   36.77  4680.9   37.06  4685.7   37.07  4719.3   36.98  4724.9   36.96
  4766.6   37.09  4768.9    37.1    4792   37.13  4792.4   37.82 4798.09   37.89
  4798.2   37.89 4798.31   37.89  4798.9    37.9  4799.8   37.31  4801.4   36.26
  4809.9   22.88 4810.01   22.71  4810.1   22.57  4810.2   22.41  4814.4    15.8
  4814.5   15.64  4822.8   14.54  4824.1   16.05  4838.6   14.34  4854.8   13.69
  4869.8   13.02  4886.2   12.52  4901.9   11.85  4916.6   10.69  4924.3   10.38
  4936.1    2.77  4939.3    -.03  4947.4   -4.34  4951.5   -3.85  4965.9   -8.51
  4986.5  -12.06  5014.3  -16.74  5019.6  -15.87  5054.6  -10.12 5060.39    -.47
  5060.5    -.28 5060.61     -.1  5060.7     .05  5063.7    1.67  5063.8     3.1
  5068.9    7.35  5069.6     7.9  5074.1    9.97  5076.5    10.5 5076.59   10.52
  5076.7   10.54  5080.6    11.4  5080.8   11.45  5092.3   13.98  5108.3   15.36
  5123.3   16.14  5140.7   37.19  5197.7   36.57  5206.7   36.08  5206.8   36.07
  5223.6   35.15  5283.6   37.18    5299   36.88    5309   36.68    5319   36.49
  5353.6   35.81  5455.1   35.63  5609.6   35.36  5679.6   39.14  5736.7   39.47
  5756.7    39.2  5806.7   40.27  5906.7   40.03  6007.9    43.5
BR U #Mann= 4
  3229.7      .2  4799.8     .08  4924.3     .04  5069.6      .2
BR U Banks=4924.3,5069.6
BR D #Sta/Elev= 79
  3229.7   53.42  3239.7   43.05  3249.7   36.99  4349.7   36.93  4389.7   36.27
  4550.9   36.63  4680.9   36.92  4685.7   36.93  4719.3   36.84  4724.9   36.82
  4766.6   36.95  4768.9   36.96    4792   36.99  4792.4   37.68 4798.09   37.75
  4798.2   37.75 4798.31   37.75  4798.9   37.76  4799.8   37.17  4801.4   36.12
  4809.9   22.74 4810.01   22.57  4810.1   22.43  4810.2   22.27  4814.4   15.66
  4814.5    15.5  4822.8    14.4  4824.1   15.91  4838.6    14.2  4854.8   13.55
  4869.8   12.88  4886.2   12.38  4901.9   11.71  4916.6   10.55  4924.3   10.24
  4936.1    2.63  4939.3    -.17  4947.4   -4.48  4951.5   -3.99  4965.9   -8.65
  4986.5   -12.2  5014.3  -16.88  5019.6  -16.01  5054.6  -10.26 5060.39    -.61
  5060.5    -.42 5060.61    -.24  5060.7    -.09  5063.7    1.53  5063.8    2.96
  5068.9    7.21  5069.6    7.76  5074.1    9.83  5076.5   10.36 5076.59   10.38
  5076.7    10.4  5080.6   11.26  5080.8   11.31  5092.3   13.84  5108.3   15.22
  5123.3      16  5140.7   37.05  5197.7   36.43  5206.7   35.94  5206.8   35.93
  5223.6   35.01  5283.6   37.04    5299   36.74    5309   36.54    5319   36.35
  5353.6   35.67  5455.1   35.49  5609.6   35.22  5679.6      39  5736.7   39.33
  5756.7   39.06  5806.7   40.13  5906.7   39.89  6007.9   43.36
BR D #Mann= 4
  3229.7      .2  4799.8     .08  4924.3     .04  5069.6      .2
BR D Banks=4924.3,5069.6
BC Design=,, 0 ,, 0 ,,,,,,
BC HTab HWMax=53.82

Type RM Length L Ch R = 1 ,109350.2,231.2,231.2,231.2
BEGIN DESCRIPTION:
Downstream Section of Bridge/Culvert/Weir
END DESCRIPTION:
XS GIS Cut Line= 6
      3124480.37      13844682.3      3124223.67       13843977.
      3123975.19     13842988.46      3123886.11     13842813.87
      3123635.94     13842465.59      3123337.88     13842225.69
#Sta/Elev= 30
  3229.7   53.41  3239.7   43.04  3249.7   36.98  4799.8   37.16  4801.4   36.11
  4814.5   15.49  4822.8   14.39  4824.1    15.9  4838.6   14.19  4924.3   10.23
  4947.4   -4.49  4951.5      -4  4965.9   -8.66  5014.3  -16.89  5054.6  -10.27
  5060.7     -.1  5063.7    1.52  5063.8    2.95  5069.6    7.75  5074.1    9.82
  5092.3   13.83  5123.3   15.99  5140.7   37.04  5223.6      35  5283.6   37.03
  5353.6   35.66  5609.6   35.21  5679.6   38.99  5906.7   39.88  6007.9   43.35
#Mann= 4 ,-1 , 0
  3229.7      .2       0  4799.8     .08       0  4924.3     .04       0
  5069.6      .2       0
#XS Ineff= 2 , 0
            4800    38.9    5140            37.3
Permanent Ineff=
       F       F
Bank Sta=4924.3,5069.6
XS Rating Curve= 0
Exp/Cntr=.5,.3

Type RM Length L Ch R = 1 ,109119.0,31.8,31.8,31.8
BEGIN DESCRIPTION:
Upstream Section of Bridge/Culvert/Weir
END DESCRIPTION:
XS GIS Cut Line= 6
      3124517.92     13844785.64       3124419.4     13844428.76
      3124121.89     13843129.16      3124138.47     13842955.03
      3124196.59     13842600.66      3124054.41     13842002.09
#Sta/Elev= 30
  3118.6   47.66  3148.6   36.29  3198.6   33.58  4188.6   36.16  4368.6    38.8
  4637.5   36.43  4697.5   30.15 4709.02   33.33 4726.86   30.75 4727.47   34.54
 4728.42      27  4728.9   26.97 4821.69   19.09 4893.66   18.97  4928.9   11.03
    4947     .61 4952.46   -6.79  4983.2  -17.14 5011.34  -15.88 5034.73   -9.36
 5050.83    5.64 5052.74   -2.13 5053.78    4.29 5079.59   11.08 5118.73   24.24
  5223.2   33.51  5690.6   33.31  5850.6   38.85  5880.6   42.12  5971.3   41.13
#Mann= 4 ,-1 , 0
  3118.6      .2       0  4728.9    .045       0  4928.9     .04       0
 5079.59      .2       0
#XS Ineff= 2 , 0
            4370    38.9    5080            32.2
Permanent Ineff=
       F       F
Bank Sta=4928.9,5079.59
XS Rating Curve= 0
Exp/Cntr=.5,.3