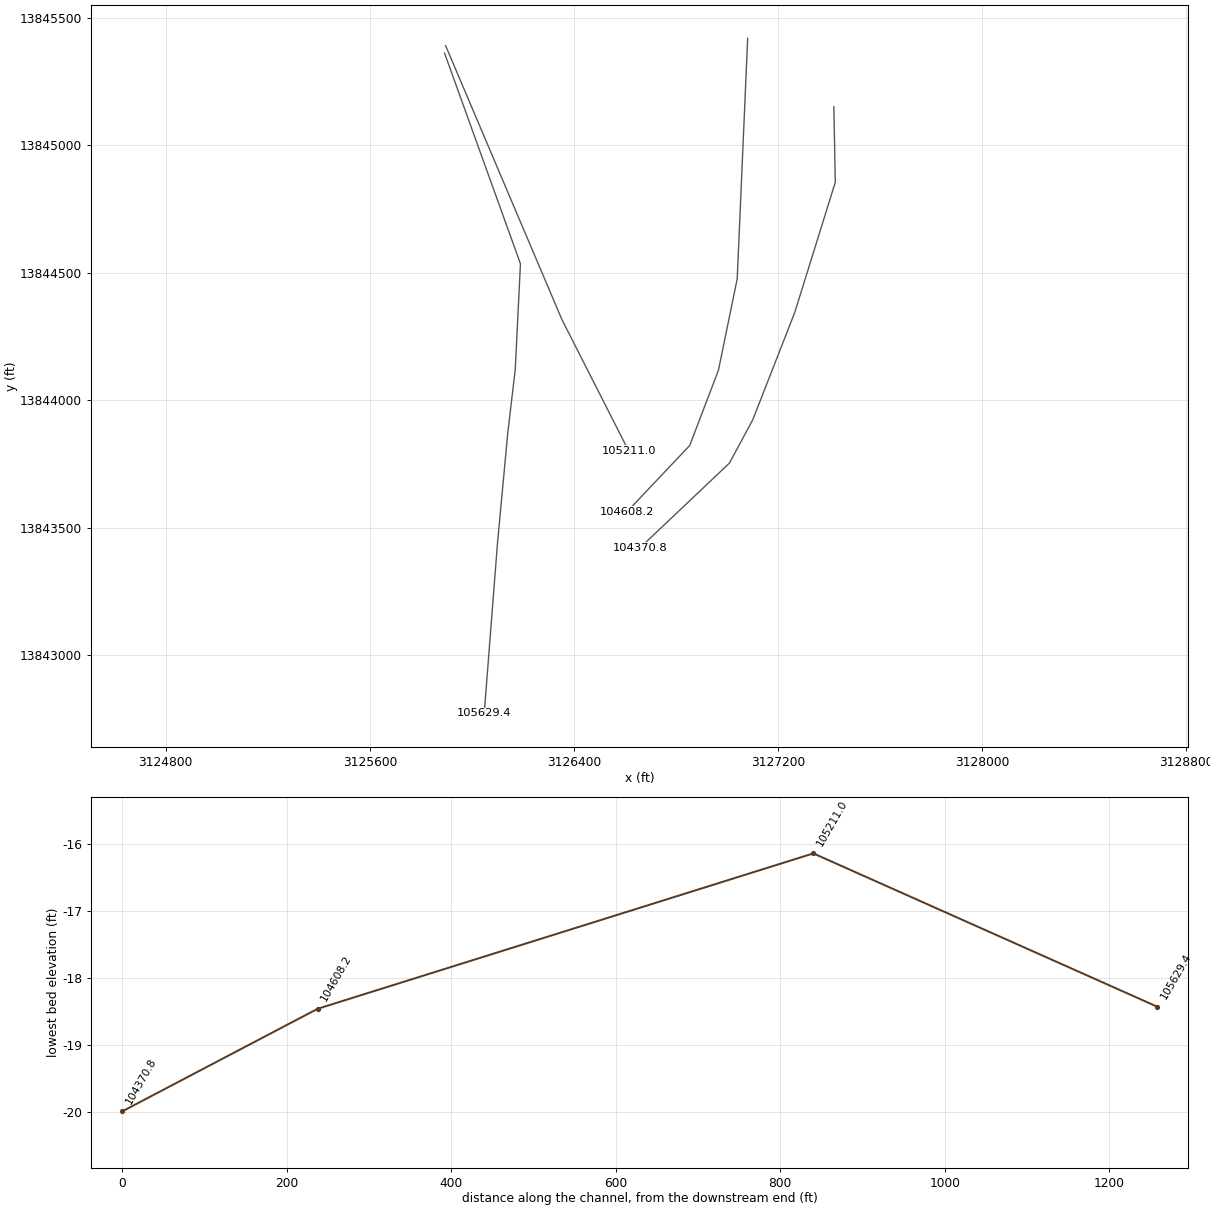
HEC-RAS study W100-00-00.prj: W100-00-00

--- W100-00-00.g01 (geometry) --- (continued)

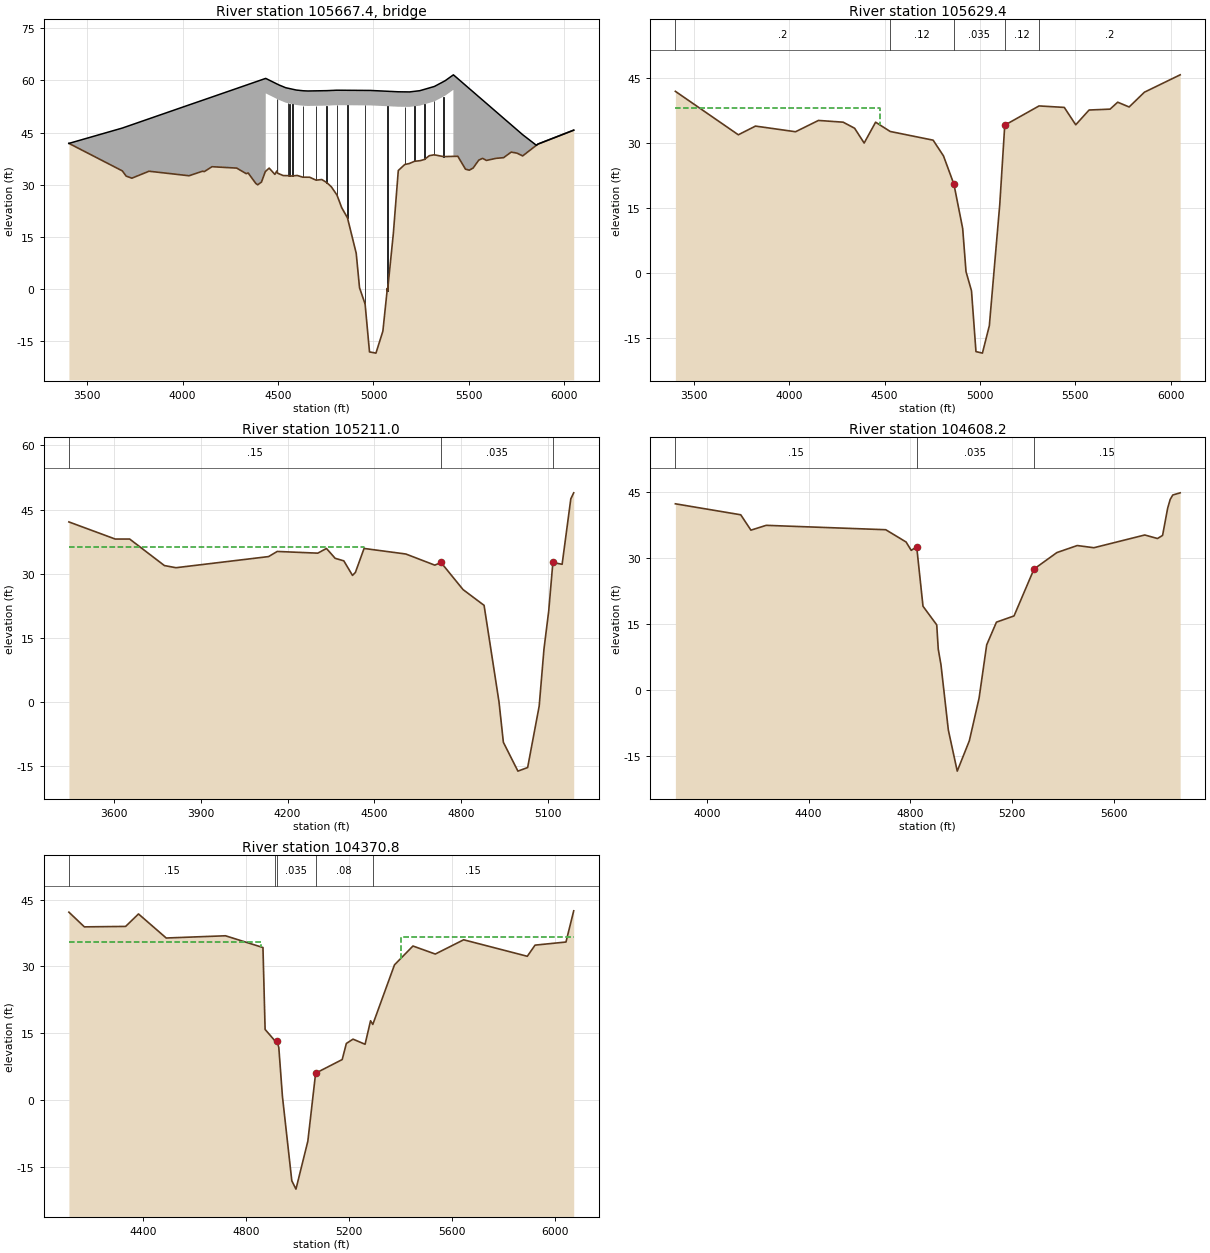
Type RM Length L Ch R = 3 ,105667.4,,,
BEGIN DESCRIPTION:
ELYSIAN STREET
Structure ID: W00-15
END DESCRIPTION:
Bridge Culvert--1,0,-1,-1, 0
Deck Dist Width WeirC Skew NumUp NumDn MinLoCord MaxHiCord MaxSubmerge Is_Ogee
10,56,2.6,0, 48, 48, , , .95, 0, 1,1,,
  3403.6  3683.6  3703.6  3733.6  3823.6  4033.6  4103.6  4113.6  4153.6  4283.2
  4333.2  4343.2  4383.2  4393.2  4413.2  4433.2 4435.31  4435.4  4504.4  4539.8
  4595.2  4631.2  4656.1  4754.7    4808  4985.1  5129.7  5189.6  5242.6  5319.5
  5375.6 5418.99  5419.1  5442.2  5482.2  5502.2  5522.2  5552.2  5572.2  5592.2
  5642.2  5682.2  5722.2  5752.2  5782.2  5853.9  5862.2  6049.7
    41.9   46.31   46.69   47.26   48.97   52.96   54.28   54.47   55.23   57.69
   58.64   58.83   59.59   59.78   60.16   60.54   60.58   60.57    58.7    57.9
   57.23   57.02   56.96   57.05   57.18   57.11   56.73   56.69   57.04   58.26
    59.9    61.6    61.6   60.51   58.61   57.66   56.72   55.29   54.35    53.4
   51.03   49.13   47.24   45.82    44.4   41.36    41.7    45.7
    41.9      34    32.5    31.9    33.9    32.6    33.9    33.8    35.2    34.8
    33.2    33.4    30.4      30    30.8    33.8   33.91   56.27    54.4    53.6
   52.93   52.72   52.66   52.75   52.88   52.81   52.43   52.39   52.74   53.96
    55.6    57.3   38.17    38.2    34.5    34.2    34.8    37.1    37.6      37
    37.6    37.8    39.4    39.1    38.3   41.35    41.7    45.7
  3403.6  3683.6  3703.6  3733.6  3823.6  4033.6  4103.6  4113.6  4153.6  4283.2
  4333.2  4343.2  4383.2  4393.2  4413.2  4433.2 4435.31  4435.4  4504.4  4539.8
  4595.2  4631.2  4656.1  4754.7    4808  4985.1  5129.7  5189.6  5242.6  5319.5
  5375.6 5418.99  5419.1  5442.2  5482.2  5502.2  5522.2  5552.2  5572.2  5592.2
  5642.2  5682.2  5722.2  5752.2  5782.2  5853.9  5862.2  6049.7
    41.9   46.31   46.69   47.26   48.97   52.96   54.28   54.47   55.23   57.69
   58.64   58.83   59.59   59.78   60.16   60.54   60.58   60.57    58.7    57.9
   57.23   57.02   56.96   57.05   57.18   57.11   56.73   56.69   57.04   58.26
    59.9    61.6    61.6   60.51   58.61   57.66   56.72   55.29   54.35    53.4
   51.03   49.13   47.24   45.82    44.4   41.36    41.7    45.7
   41.78   33.88   32.38   31.78   33.78   32.48   33.78   33.68   35.08   34.68
   33.08   33.28   30.28   29.88   30.68   33.68   33.79   56.15   54.28   53.48
   52.81    52.6   52.54   52.63   52.76   52.69   52.31   52.27   52.62   53.84
   55.48   57.18   38.05   38.08   34.38   34.08   34.68   36.98   37.48   36.88
   37.48   37.68   39.28   38.98   38.18   41.23   41.58   45.58
Pier Skew, UpSta & Num, DnSta & Num=  ,4493.4, 2 ,4493.4, 2 , 0 , 0 , 0 ,,
       3       3
    32.7   55.73
       3       3
   32.58   55.61
Pier Skew, UpSta & Num, DnSta & Num=  ,4551.8, 2 ,4551.8, 2 , 0 , 0 , 0 ,,
       3       3
   31.61   54.47
       3       3
   31.49   54.35
Pier Skew, UpSta & Num, DnSta & Num=  ,4560.7, 2 ,4560.7, 2 , 0 , 0 , 0 ,,
       3       3
   31.53   54.37
       3       3
   31.41   54.25
Pier Skew, UpSta & Num, DnSta & Num=  ,4574.8, 2 ,4574.8, 2 , 0 , 0 , 0 ,,
       3       3
   31.54    54.2
       3       3
   31.42   54.08
Pier Skew, UpSta & Num, DnSta & Num=  ,4629.8, 2 ,4629.8, 2 , 0 , 0 , 0 ,,
       3       3
   31.19   53.74
       3       3
   31.07   53.62
Pier Skew, UpSta & Num, DnSta & Num=  ,4699.6, 2 ,4699.6, 2 , 0 , 0 , 0 ,,
       3       3
   30.34    53.7
       3       3
   30.22   53.58
Pier Skew, UpSta & Num, DnSta & Num=  ,4754.7, 2 ,4754.7, 2 , 0 , 0 , 0 ,,
       3       3
   29.58   53.75
       3       3
   29.46   53.63
Pier Skew, UpSta & Num, DnSta & Num=  ,4808.9, 2 ,4808.9, 2 , 0 , 0 , 0 ,,
       3       3
   25.83   53.88
       3       3
   25.71   53.76
Pier Skew, UpSta & Num, DnSta & Num=  ,4863.8, 2 ,4863.8, 2 , 0 , 0 , 0 ,,
       3       3
   19.18   53.84
       3       3
   19.06   53.72
Pier Skew, UpSta & Num, DnSta & Num=  ,4954.8, 2 ,4954.8, 2 , 0 , 0 , 0 ,,
       3       3
   -5.31   53.81
       3       3
   -5.43   53.69
Pier Skew, UpSta & Num, DnSta & Num=  ,5073.7, 2 ,5073.7, 2 , 0 , 0 , 0 ,,
       3       3
   -1.09   53.57
       3       3
   -1.21   53.45
Pier Skew, UpSta & Num, DnSta & Num=  ,5164.3, 2 ,5164.3, 2 , 0 , 0 , 0 ,,
       3       3
   34.76   53.41
       3       3
   34.64   53.29
Pier Skew, UpSta & Num, DnSta & Num=  ,5215.6, 2 ,5215.6, 2 , 0 , 0 , 0 ,,
       3       3
   35.73   53.57
       3       3
   35.61   53.45
Pier Skew, UpSta & Num, DnSta & Num=  ,5267.5, 2 ,5267.5, 2 , 0 , 0 , 0 ,,
       3       3
   36.27   54.16
       3       3
   36.15   54.04
Pier Skew, UpSta & Num, DnSta & Num=  ,5318.1, 2 ,5318.1, 2 , 0 , 0 , 0 ,,
       3       3
   37.61   54.96
       3       3
   37.49   54.84
Pier Skew, UpSta & Num, DnSta & Num=  ,5367.8, 2 ,5367.8, 2 , 0 , 0 , 0 ,,
       3       3
    37.1   56.41
       3       3
   36.98   56.29
Abutment Skew #Up #Dn= , 2 , 2
  4435.2  4496.9
   56.27   33.35
  4435.2  4496.9
   56.15   33.23
Abutment Skew #Up #Dn= , 2 , 2
  5293.2 5419.19
   38.38    57.3
  5293.2 5419.19
   38.26   57.18
BR Coef= 1 , 1 , 0 ,1.25, 0 ,,,.8,0,2,0,
WSPro=,,,, 1 ,,,, 0 ,,,, 0 ,,,,-1 ,-1 ,-1 , 0 , 0 , 0 , 0 , 0
BR U #Sta/Elev= 102
  3403.6    41.9  3403.9   41.89  3683.6      34  3703.6    32.5  3733.6    31.9
  3823.6    33.9  4033.6    32.6  4103.6    33.9  4113.6    33.8  4153.6    35.2
  4283.2    34.8  4333.2    33.2  4343.2    33.4  4383.2    30.4  4393.2      30
  4413.2    30.8  4433.2    33.8  4435.2    33.9 4435.31   33.91  4435.4   33.91
 4439.69   34.12  4439.8   34.13 4439.91   34.14  4453.2    34.8  4469.6   33.82
  4483.2      33  4493.4   33.97  4496.8   33.35  4496.9   33.35  4504.4   33.18
  4526.9   32.66  4529.7   32.66  4539.8   32.64  4551.8   32.63  4560.7   32.53
  4574.8   32.54  4595.2   32.66  4599.7   32.69  4629.8   32.19  4631.2   32.19
  4656.1   32.18  4665.5   32.18  4699.6   31.33  4729.2   31.52  4754.6   30.66
  4754.7   30.66  4779.2   29.43    4808   27.12  4808.9   27.05  4833.5   23.44
  4863.2   20.57  4863.8   20.51  4909.6   10.34  4909.9   10.17  4927.1      .4
  4954.8   -4.01  4955.8   -4.01  4979.3  -18.01  4985.1  -18.07  5013.1  -18.36
  5049.4  -12.04  5072.5     .07  5072.9     .28  5073.7    -.51  5104.1   15.91
  5129.7   33.76  5130.2   34.11  5164.3   35.84  5186.9    36.1  5189.6   36.16
  5215.6   36.76  5242.6   36.92  5244.6   36.93  5267.5   37.29  5293.1   38.38
  5293.2   38.38    5310   38.54  5318.1   38.62  5319.5   38.61  5367.8    38.1
  5375.6   38.11 5416.99   38.17  5417.1   38.17 5417.21   38.17 5418.99   38.17
  5419.1   38.17  5419.2   38.17  5442.2    38.2  5482.2    34.5  5502.2    34.2
  5522.2    34.8  5552.2    37.1  5572.2    37.6  5592.2      37  5642.2    37.6
  5682.2    37.8  5722.2    39.4  5752.2    39.1  5782.2    38.3  5853.9   41.35
  5862.2    41.7  6049.7    45.7
BR U #Mann= 5
  3403.6      .2  4529.7     .12  4863.8    .035  5130.2     .12    5310      .2
BR U Banks=4863.8,5130.2
BR D #Sta/Elev= 102
  3403.6   41.78  3403.9   41.77  3683.6   33.88  3703.6   32.38  3733.6   31.78
  3823.6   33.78  4033.6   32.48  4103.6   33.78  4113.6   33.68  4153.6   35.08
  4283.2   34.68  4333.2   33.08  4343.2   33.28  4383.2   30.28  4393.2   29.88
  4413.2   30.68  4433.2   33.68  4435.2   33.78 4435.31   33.79  4435.4   33.79
 4439.69      34  4439.8   34.01 4439.91   34.02  4453.2   34.68  4469.6    33.7
  4483.2   32.88  4493.4   33.85  4496.8   33.23  4496.9   33.23  4504.4   33.06
  4526.9   32.54  4529.7   32.54  4539.8   32.52  4551.8   32.51  4560.7   32.41
  4574.8   32.42  4595.2   32.54  4599.7   32.57  4629.8   32.07  4631.2   32.07
  4656.1   32.06  4665.5   32.06  4699.6   31.21  4729.2    31.4  4754.6   30.54
  4754.7   30.54  4779.2   29.31    4808      27  4808.9   26.93  4833.5   23.32
  4863.2   20.45  4863.8   20.39  4909.6   10.22  4909.9   10.05  4927.1     .28
  4954.8   -4.13  4955.8   -4.13  4979.3  -18.13  4985.1  -18.19  5013.1  -18.48
  5049.4  -12.16  5072.5    -.05  5072.9     .16  5073.7    -.63  5104.1   15.79
  5129.7   33.64  5130.2   33.99  5164.3   35.72  5186.9   35.98  5189.6   36.04
  5215.6   36.64  5242.6    36.8  5244.6   36.81  5267.5   37.17  5293.1   38.26
  5293.2   38.26    5310   38.42  5318.1    38.5  5319.5   38.49  5367.8   37.98
  5375.6   37.99 5416.99   38.05  5417.1   38.05 5417.21   38.05 5418.99   38.05
  5419.1   38.05  5419.2   38.05  5442.2   38.08  5482.2   34.38  5502.2   34.08
  5522.2   34.68  5552.2   36.98  5572.2   37.48  5592.2   36.88  5642.2   37.48
  5682.2   37.68  5722.2   39.28  5752.2   38.98  5782.2   38.18  5853.9   41.23
  5862.2   41.58  6049.7   45.58
BR D #Mann= 5
  3403.6      .2  4529.7     .12  4863.8    .035  5130.2     .12    5310      .2
BR D Banks=4863.8,5130.2
BC Design=,, 0 ,, 0 ,,,,,,
BC HTab HWMax=45.84

Type RM Length L Ch R = 1 ,105629.4,418.4,418.4,418.4
BEGIN DESCRIPTION:
Downstream Section of Bridge/Culvert/Weir
END DESCRIPTION:
XS GIS Cut Line= 6
      3125892.67     13845360.38      3126190.16     13844534.67
      3126169.72     13844119.28      3126140.41     13843871.53
      3126099.75     13843434.46      3126048.16     13842772.41
#Sta/Elev= 30
  3403.6   41.83  3733.6   31.83  3823.6   33.83  4033.6   32.53  4153.6   35.13
  4283.2   34.73  4343.2   33.33  4393.2   29.93  4453.2   34.73  4529.7   32.59
  4754.7   30.59  4808.9   26.98  4863.8   20.44  4909.6   10.27  4927.1     .33
  4955.8   -4.08  4979.3  -18.08  5013.1  -18.43  5049.4  -12.11  5104.1   15.84
  5130.2   34.04    5310   38.47  5442.2   38.13  5502.2   34.13  5572.2   37.53
  5682.2   37.73  5722.2   39.33  5782.2   38.23  5862.2   41.63  6049.7   45.63
#Mann= 5 ,-1 , 0
  3403.6      .2       0  4529.7     .12       0  4863.8    .035       0
  5130.2     .12       0    5310      .2       0
#XS Ineff= 2 , 0
            4475      38    5305              38
Permanent Ineff=
       F       F
Bank Sta=4863.8,5130.2
XS Rating Curve= 0
Exp/Cntr=.5,.3

Type RM Length L Ch R = 1 ,105211.0,674,602.8,515.3
BEGIN DESCRIPTION:
Cross Section 105211.0
END DESCRIPTION:
XS GIS Cut Line= 3
      3125896.86     13845389.75      3126351.85     13844317.88
      3126614.51     13843800.78
#Sta/Elev= 30
  3444.4    42.1  3604.4    38.1  3654.4    38.1  3774.4    31.9  3814.4    31.4
  4134.4      34  4164.4    35.2  4304.4    34.8  4334.4    35.9  4364.4    33.6
  4394.4      33  4424.4    29.6  4434.4    30.3  4464.4    35.9  4608.8    34.6
  4708.8      32  4730.2   32.62  4806.4   26.29  4879.1    22.6  4930.6     .07
  4945.8   -9.41    4996  -16.14  5029.6   -15.3  5069.5    -.94  5086.1   12.41
  5102.5   21.32  5116.8   32.62  5148.8    32.2  5178.8    47.5  5188.8    48.9
#Mann= 3 ,-1 , 0
  3444.4     .15       0  4730.2    .035       0  5116.8      .2       0
#XS Ineff= 2 , 0
            4465    36.2
Permanent Ineff=
       F       F
Bank Sta=4730.2,5116.8
XS Rating Curve= 0
Exp/Cntr=.3,.1

Type RM Length L Ch R = 1 ,104608.2,251.2,237.4,237.3
BEGIN DESCRIPTION:
Cross Section 104608.2
END DESCRIPTION:
XS GIS Cut Line= 5
      3127080.82     13845418.35      3127039.83     13844475.53
      3126966.15     13844117.09      3126853.64     13843822.38
      3126606.72     13843561.52
#Sta/Elev= 30
    3876    42.4    4133    39.9    4173    36.4    4233    37.5    4703    36.5
    4783    33.7    4803    31.8  4824.6    32.6  4849.4   19.08  4903.4   14.83
  4909.4     9.3    4920    5.78    4949    -9.1    4984  -18.46  5031.6  -11.54
  5069.8   -1.86  5099.7   10.28  5138.1   15.46  5207.2   16.87  5285.8   27.55
  5375.7    31.3  5455.7    32.9  5521.1    32.4  5721.1    35.3  5771.1    34.5
  5791.1    35.2  5811.1    41.4  5821.1    43.4  5831.1    44.4  5860.3    44.9
#Mann= 3 ,-1 , 0
    3876     .15       0  4824.6    .035       0  5285.8     .15       0
Bank Sta=4824.6,5285.8
XS Rating Curve= 0
Exp/Cntr=.5,.3

Type RM Length L Ch R = 1 ,104370.8,41.6,41.6,41.6
BEGIN DESCRIPTION:
Upstream Section of Bridge/Culvert/Weir
END DESCRIPTION:
XS GIS Cut Line= 6
      3127418.58     13845150.78      3127424.33     13844854.49
      3127265.44     13844344.11      3127100.96      13843923.5
       3127009.4     13843753.55      3126658.93     13843421.54
#Sta/Elev= 30
  4113.5   42.17  4173.5   38.87  4333.5   38.97  4383.5   41.77    4491   36.37
    4721   36.87  4866.4   34.23  4874.7   15.85  4912.5   13.32  4921.1   13.35
    4928   11.73    4942     .77  4978.3  -18.11  4994.4  -19.99  5040.5   -9.23
  5070.7    6.03  5173.8    9.09  5189.9    12.7  5215.8   13.67  5262.6   12.52
  5283.8    17.8  5292.6   16.97  5376.7   30.35  5448.3   34.57    5535   32.77
    5645   35.97    5892   32.27    5922   34.77    6042   35.47    6072   42.47
#Mann= 5 ,-1 , 0
  4113.5     .15       0  4912.5     .08       0  4921.1    .035       0
  5070.7     .08       0  5292.6     .15       0
#XS Ineff= 2 , 0
            4860    35.5    5400            36.6
Permanent Ineff=
       F       F
Bank Sta=4921.1,5070.7
XS Rating Curve= 0
Exp/Cntr=.5,.3