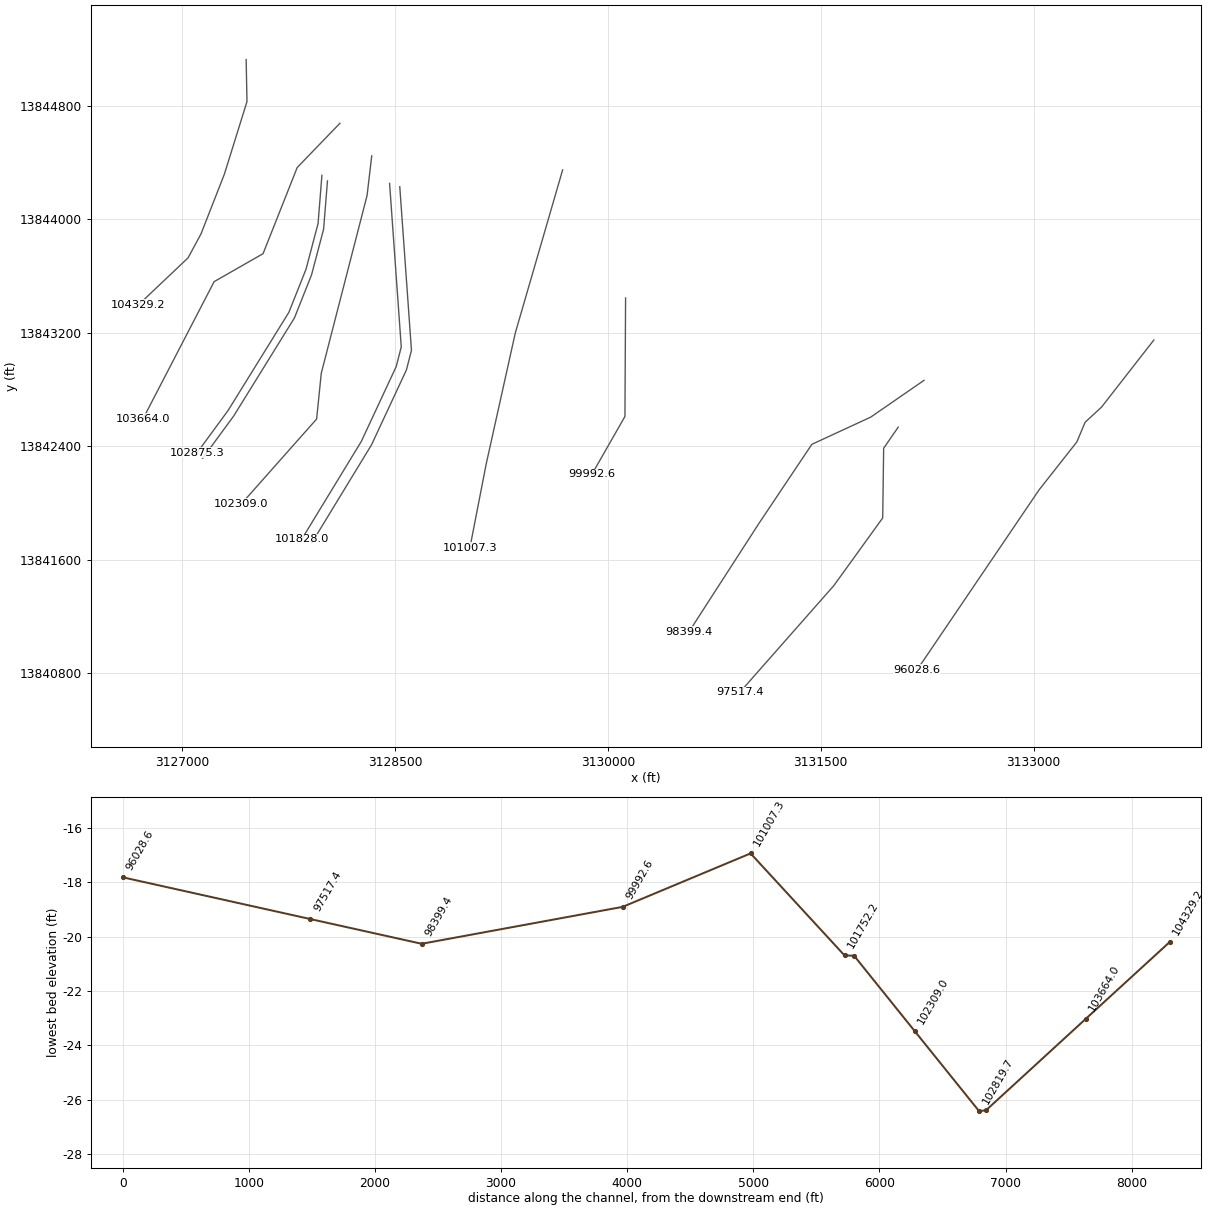
HEC-RAS study W100-00-00.prj: W100-00-00

--- W100-00-00.g01 (geometry) --- (continued)

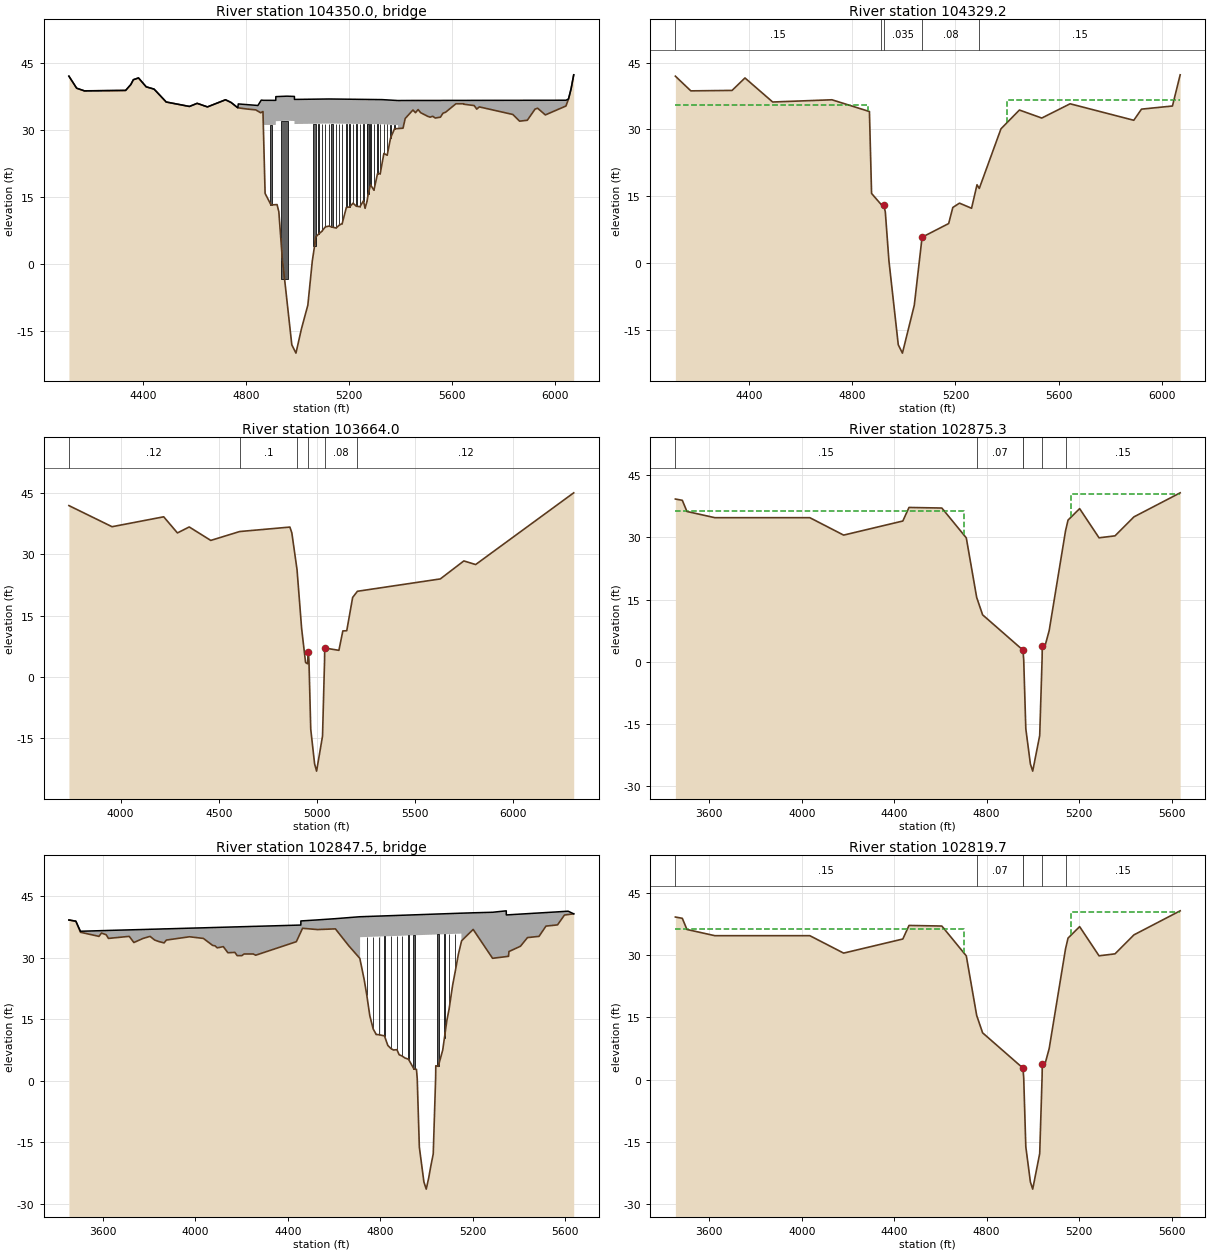
Type RM Length L Ch R = 3 ,104350.0,,,
BEGIN DESCRIPTION:
RAILROAD BRIDGE
Structure ID: W00-13
END DESCRIPTION:
Bridge Culvert--1,0,-1,-1, 0
Deck Dist Width WeirC Skew NumUp NumDn MinLoCord MaxHiCord MaxSubmerge Is_Ogee
10,21.6,2.6,0, 60, 60, , , .95, 0, 1,1,,
  4113.5  4143.5  4173.5  4333.5  4353.5  4363.5  4383.5  4413.5  4443.5    4491
    4581    4611    4651    4721  4742.6  4768.7  4770.6  4838.5  4846.6  4857.6
  4859.8  4866.4  4867.8    4916  4916.3  4959.3  4988.5  4988.7  5122.2  5328.5
 5390.19  5390.3  5409.8  5418.3  5448.3  5458.3  5468.3  5478.3    5505    5515
    5525    5535    5555    5565    5575    5615    5645  5685.8  5695.8  5705.8
  5835.8    5862    5892    5922    5932    5962    6042    6052    6062    6072
    42.1    39.4    38.8    38.9    40.2    41.3    41.7    39.7    39.2    36.3
    35.3      36    35.2    36.8    36.2      35   35.87   35.56   35.52   36.53
   36.73   36.69   36.68   36.67   37.51   37.61   37.55   36.88   36.98   36.84
   36.63   36.63   36.64   36.64   36.65   36.65   36.65   36.65   36.65   36.65
   36.65   36.65   36.65   36.66   36.66   36.66   36.66   36.67   36.67   36.67
   36.68   36.68   36.69   36.69   36.69   36.69    36.7      37    39.3    42.4
    42.1    39.4    38.8    38.9    40.2    41.3    41.7    39.7    39.2    36.3
    35.3      36    35.2    36.8    36.2      35   34.99   34.53   34.25   33.88
   33.95   34.16   31.16   31.15   31.99   32.09   32.03   31.36   31.46   31.32
   31.11   30.34   30.42    32.6    34.5    33.9    34.6    33.9    33.1    32.9
    33.1    32.7    32.9    33.8      34    35.9    35.9    35.5    34.7    35.2
    33.5      32    32.2    34.7    34.9    33.4    35.4      37    39.3    42.4
  4113.5  4143.5  4173.5  4333.5  4353.5  4363.5  4383.5  4413.5  4443.5    4491
    4581    4611    4651    4721  4742.6  4768.7  4770.6  4838.5  4846.6  4857.6
  4859.8  4866.4  4867.8    4916  4916.3  4959.3  4988.5  4988.7  5122.2  5328.5
 5390.19  5390.3  5409.8  5418.3  5448.3  5458.3  5468.3  5478.3    5505    5515
    5525    5535    5555    5565    5575    5615    5645  5685.8  5695.8  5705.8
  5835.8    5862    5892    5922    5932    5962    6042    6052    6062    6072
    42.1    39.4    38.8    38.9    40.2    41.3    41.7    39.7    39.2    36.3
    35.3      36    35.2    36.8    36.2      35   35.87   35.56   35.52   36.53
   36.73   36.69   36.68   36.67   37.51   37.61   37.55   36.88   36.98   36.84
   36.63   36.63   36.64   36.64   36.65   36.65   36.65   36.65   36.65   36.65
   36.65   36.65   36.65   36.66   36.66   36.66   36.66   36.67   36.67   36.67
   36.68   36.68   36.69   36.69   36.69   36.69    36.7      37    39.3    42.4
      42    39.3    38.7    38.8    40.1    41.2    41.6    39.6    39.1    36.2
    35.2    35.9    35.1    36.7    36.1    34.9   34.89   34.43   34.15   33.78
   33.85   34.06   31.06   31.05   31.89   31.99   31.93   31.26   31.36   31.22
   31.01   30.24   30.32    32.5    34.4    33.8    34.5    33.8      33    32.8
      33    32.6    32.8    33.7    33.9    35.8    35.8    35.4    34.6    35.1
    33.4    31.9    32.1    34.6    34.8    33.3    35.3    36.9    39.2    42.3
Pier Skew, UpSta & Num, DnSta & Num=  ,4897.6, 2 ,4897.6, 2 , 0 , 0 , 0 ,,
       7       7
   12.21   32.15
       7       7
   12.11   32.05
Pier Skew, UpSta & Num, DnSta & Num=  ,4950.1, 2 ,4950.1, 2 , 0 , 0 , 0 ,,
    29.7    29.7
  -12.16   33.08
    29.7    29.7
  -12.26   32.98
Pier Skew, UpSta & Num, DnSta & Num=  ,5066.4, 2 ,5066.4, 2 , 0 , 0 , 0 ,,
       9       9
    1.19   32.34
       9       9
    1.09   32.24
Pier Skew, UpSta & Num, DnSta & Num=  ,5081.6, 2 ,5081.6, 2 , 0 , 0 , 0 ,,
     1.2     1.2
    5.58   32.37
     1.2     1.2
    5.48   32.27
Pier Skew, UpSta & Num, DnSta & Num=  ,5094.7, 2 ,5094.7, 2 , 0 , 0 , 0 ,,
     1.2     1.2
    6.24    32.4
     1.2     1.2
    6.14    32.3
Pier Skew, UpSta & Num, DnSta & Num=  ,5108.3, 2 ,5108.3, 2 , 0 , 0 , 0 ,,
     1.2     1.2
    7.23   32.44
     1.2     1.2
    7.13   32.34
Pier Skew, UpSta & Num, DnSta & Num=  ,5122.2, 2 ,5122.2, 2 , 0 , 0 , 0 ,,
     1.2     1.2
    7.44   32.46
     1.2     1.2
    7.34   32.36
Pier Skew, UpSta & Num, DnSta & Num=  ,5134.6, 2 ,5134.6, 2 , 0 , 0 , 0 ,,
      10      10
    7.16   32.45
      10      10
    7.06   32.35
Pier Skew, UpSta & Num, DnSta & Num=  ,5150.4, 2 ,5150.4, 2 , 0 , 0 , 0 ,,
     1.2     1.2
    7.03   32.45
     1.2     1.2
    6.93   32.35
Pier Skew, UpSta & Num, DnSta & Num=  ,5162.6, 2 ,5162.6, 2 , 0 , 0 , 0 ,,
     1.2     1.2
    7.64   32.45
     1.2     1.2
    7.54   32.35
Pier Skew, UpSta & Num, DnSta & Num=  ,5173.8, 2 ,5173.8, 2 , 0 , 0 , 0 ,,
     1.2     1.2
       8   32.44
     1.2     1.2
     7.9   32.34
Pier Skew, UpSta & Num, DnSta & Num=  ,5189.9, 2 ,5189.9, 2 , 0 , 0 , 0 ,,
     1.2     1.2
    11.5   32.44
     1.2     1.2
    11.4   32.34
Pier Skew, UpSta & Num, DnSta & Num=  ,5202.7, 2 ,5202.7, 2 , 0 , 0 , 0 ,,
     1.2     1.2
   11.74   32.43
     1.2     1.2
   11.64   32.33
Pier Skew, UpSta & Num, DnSta & Num=  ,5215.8, 2 ,5215.8, 2 , 0 , 0 , 0 ,,
     1.2     1.2
   12.56   32.43
     1.2     1.2
   12.46   32.33
Pier Skew, UpSta & Num, DnSta & Num=  ,5228.8, 2 ,5228.8, 2 , 0 , 0 , 0 ,,
     1.2     1.2
    11.9   32.43
     1.2     1.2
    11.8   32.33
Pier Skew, UpSta & Num, DnSta & Num=  ,5242.8, 2 ,5242.8, 2 , 0 , 0 , 0 ,,
     1.2     1.2
    11.8   32.42
     1.2     1.2
    11.7   32.32
Pier Skew, UpSta & Num, DnSta & Num=  ,5256.2, 2 ,5256.2, 2 , 0 , 0 , 0 ,,
     1.2     1.2
   12.96   32.42
     1.2     1.2
   12.86   32.32
Pier Skew, UpSta & Num, DnSta & Num=  ,5270, 2 ,5270, 2 , 0 , 0 , 0 ,,
     1.2     1.2
   12.87   32.41
     1.2     1.2
   12.77   32.31
Pier Skew, UpSta & Num, DnSta & Num=  ,5275, 2 ,5275, 2 , 0 , 0 , 0 ,,
       8       8
   13.33   32.41
       8       8
   13.23   32.31
Pier Skew, UpSta & Num, DnSta & Num=  ,5283.8, 2 ,5283.8, 2 , 0 , 0 , 0 ,,
     1.2     1.2
   16.59   32.39
     1.2     1.2
   16.49   32.29
Pier Skew, UpSta & Num, DnSta & Num=  ,5296.9, 2 ,5296.9, 2 , 0 , 0 , 0 ,,
     1.2     1.2
   15.56   32.37
     1.2     1.2
   15.46   32.27
Pier Skew, UpSta & Num, DnSta & Num=  ,5310.8, 2 ,5310.8, 2 , 0 , 0 , 0 ,,
     1.2     1.2
   19.04   32.35
     1.2     1.2
   18.94   32.25
Pier Skew, UpSta & Num, DnSta & Num=  ,5321.3, 2 ,5321.3, 2 , 0 , 0 , 0 ,,
     1.2     1.2
    19.2   32.33
     1.2     1.2
    19.1   32.23
Pier Skew, UpSta & Num, DnSta & Num=  ,5335.5, 2 ,5335.5, 2 , 0 , 0 , 0 ,,
     1.2     1.2
   23.57    32.3
     1.2     1.2
   23.47    32.2
Pier Skew, UpSta & Num, DnSta & Num=  ,5348.3, 2 ,5348.3, 2 , 0 , 0 , 0 ,,
     1.2     1.2
   23.37   32.25
     1.2     1.2
   23.27   32.15
Pier Skew, UpSta & Num, DnSta & Num=  ,5361.5, 2 ,5361.5, 2 , 0 , 0 , 0 ,,
     1.2     1.2
   27.04   32.21
     1.2     1.2
   26.94   32.11
Pier Skew, UpSta & Num, DnSta & Num=  ,5376.8, 2 ,5376.8, 2 , 0 , 0 , 0 ,,
     1.2     1.2
   29.21   32.16
     1.2     1.2
   29.11   32.06
Abutment Skew #Up #Dn= , 2 , 2
  4867.6  4874.7
   31.16   15.78
  4867.6  4874.7
   31.06   15.68
Abutment Skew #Up #Dn= , 2 , 2
  5376.8 5390.39
   30.29   31.11
  5376.8 5390.39
   30.19   31.01
BR Coef= 1 , 1 , 0 ,1.25, 0 ,,,.8,0,2,0,
WSPro=,,,, 1 ,,,, 0 ,,,, 0 ,,,,-1 ,-1 ,-1 , 0 , 0 , 0 , 0 , 0
BR U #Sta/Elev= 120
  4113.5    42.1  4143.5    39.4  4173.5    38.8  4333.5    38.9  4353.5    40.2
  4363.5    41.3  4383.5    41.7  4413.5    39.7  4443.5    39.2    4451    38.8
    4491    36.3    4581    35.3    4611      36    4651    35.2    4721    36.8
  4742.6    36.2  4768.6   35.01  4768.7      35  4770.6   34.99  4803.6   34.73
  4810.8   34.69  4838.5   34.53  4846.6   34.25  4857.6   33.88  4859.8   33.95
  4866.4   34.16  4867.4   31.95 4867.51    31.7 4867.59   31.52  4867.7   31.28
  4867.8   31.06 4867.91   30.82  4874.6      16  4874.7   15.78  4897.6    13.2
  4912.5   13.25    4916   13.26  4916.3   13.26  4921.1   13.28    4928   11.66
    4942      .7  4950.1   -3.36  4959.3   -8.19  4978.3  -18.18  4988.5  -19.37
  4988.7  -19.39  4994.4  -20.06  5015.4  -14.67  5040.5    -9.3  5057.9     .67
  5066.4    3.91    5070    5.63  5070.7    5.96  5081.6    6.62  5094.7    7.27
  5108.3    8.27  5116.8    8.38  5122.2    8.45  5134.6    8.23  5150.4    8.02
  5162.6    8.67  5173.8    9.02  5182.1   10.88  5189.9   12.63  5202.7   12.75
  5215.8    13.6  5228.8    12.9  5242.8    12.8  5256.2   14.12  5260.7   12.95
  5262.6   12.45    5270   13.99    5275    15.7  5283.8   17.73  5292.6    16.9
  5296.9    16.5  5310.8    20.2  5321.3    20.2  5328.5   22.51  5335.5   24.76
  5348.3   24.35  5361.5   28.22  5376.7   30.28  5376.8   30.29 5390.19   30.34
  5390.3   30.34 5390.39   30.34  5390.5   30.34  5390.6   30.34 5390.71   30.34
  5409.8   30.42  5418.3    32.6  5448.3    34.5  5458.3    33.9  5468.3    34.6
  5478.3    33.9    5505    33.1    5515    32.9    5525    33.1    5535    32.7
    5555    32.9    5565    33.8    5575      34    5615    35.9    5645    35.9
  5645.8    35.8  5685.8    35.5  5695.8    34.7  5705.8    35.2  5835.8    33.5
    5862      32    5892    32.2    5922    34.7    5932    34.9    5962    33.4
    6042    35.4  6051.1   36.86    6052      37    6062    39.3    6072    42.4
BR U #Mann= 5
  4113.5     .15  4912.5     .08  4921.1    .035  5070.7     .08  5292.6     .15
BR U Banks=4921.1,5070.7
BR D #Sta/Elev= 120
  4113.5      42  4143.5    39.3  4173.5    38.7  4333.5    38.8  4353.5    40.1
  4363.5    41.2  4383.5    41.6  4413.5    39.6  4443.5    39.1    4451    38.7
    4491    36.2    4581    35.2    4611    35.9    4651    35.1    4721    36.7
  4742.6    36.1  4768.6   34.91  4768.7    34.9  4770.6   34.89  4803.6   34.63
  4810.8   34.59  4838.5   34.43  4846.6   34.15  4857.6   33.78  4859.8   33.85
  4866.4   34.06  4867.4   31.85 4867.51    31.6 4867.59   31.42  4867.7   31.18
  4867.8   30.96 4867.91   30.72  4874.6    15.9  4874.7   15.68  4897.6    13.1
  4912.5   13.15    4916   13.16  4916.3   13.16  4921.1   13.18    4928   11.56
    4942      .6  4950.1   -3.46  4959.3   -8.29  4978.3  -18.28  4988.5  -19.47
  4988.7  -19.49  4994.4  -20.16  5015.4  -14.77  5040.5    -9.4  5057.9     .57
  5066.4    3.81    5070    5.53  5070.7    5.86  5081.6    6.52  5094.7    7.17
  5108.3    8.17  5116.8    8.28  5122.2    8.35  5134.6    8.13  5150.4    7.92
  5162.6    8.57  5173.8    8.92  5182.1   10.78  5189.9   12.53  5202.7   12.65
  5215.8    13.5  5228.8    12.8  5242.8    12.7  5256.2   14.02  5260.7   12.85
  5262.6   12.35    5270   13.89    5275    15.6  5283.8   17.63  5292.6    16.8
  5296.9    16.4  5310.8    20.1  5321.3    20.1  5328.5   22.41  5335.5   24.66
  5348.3   24.25  5361.5   28.12  5376.7   30.18  5376.8   30.19 5390.19   30.24
  5390.3   30.24 5390.39   30.24  5390.5   30.24  5390.6   30.24 5390.71   30.24
  5409.8   30.32  5418.3    32.5  5448.3    34.4  5458.3    33.8  5468.3    34.5
  5478.3    33.8    5505      33    5515    32.8    5525      33    5535    32.6
    5555    32.8    5565    33.7    5575    33.9    5615    35.8    5645    35.8
  5645.8    35.7  5685.8    35.4  5695.8    34.6  5705.8    35.1  5835.8    33.4
    5862    31.9    5892    32.1    5922    34.6    5932    34.8    5962    33.3
    6042    35.3  6051.1   36.76    6052    36.9    6062    39.2    6072    42.3
BR D #Mann= 5
  4113.5     .15  4912.5     .08  4921.1    .035  5070.7     .08  5292.6     .15
BR D Banks=4921.1,5070.7
BC Design=,, 0 ,, 0 ,,,,,,
BC HTab HWMax=42.47

Type RM Length L Ch R = 1 ,104329.2,665.2,665.2,665.2
BEGIN DESCRIPTION:
Downstream Section of Bridge/Culvert/Weir
END DESCRIPTION:
XS GIS Cut Line= 6
      3127451.45      13845125.3      3127457.21     13844829.01
      3127298.32     13844318.63      3127133.84     13843898.02
      3127042.28     13843728.07      3126691.81     13843396.05
#Sta/Elev= 30
  4113.5   41.96  4173.5   38.66  4333.5   38.76  4383.5   41.56    4491   36.16
    4721   36.66  4866.4   34.02  4874.7   15.64  4912.5   13.11  4921.1   13.14
    4928   11.52    4942     .56  4978.3  -18.32  4994.4   -20.2  5040.5   -9.44
  5070.7    5.82  5173.8    8.88  5189.9   12.49  5215.8   13.46  5262.6   12.31
  5283.8   17.59  5292.6   16.76  5376.7   30.14  5448.3   34.36    5535   32.56
    5645   35.76    5892   32.06    5922   34.56    6042   35.26    6072   42.26
#Mann= 5 ,-1 , 0
  4113.5     .15       0  4912.5     .08       0  4921.1    .035       0
  5070.7     .08       0  5292.6     .15       0
#XS Ineff= 2 , 0
            4860    35.5    5400            36.6
Permanent Ineff=
       F       F
Bank Sta=4921.1,5070.7
XS Rating Curve= 0
Exp/Cntr=.5,.3

Type RM Length L Ch R = 1 ,103664.0,622.8,788.7,665.6
BEGIN DESCRIPTION:
Cross Section 103664.0-Interpolated
END DESCRIPTION:
XS GIS Cut Line= 5
      3128112.12     13844676.27      3127811.24     13844364.45
      3127570.54     13843757.22      3127225.89     13843560.28
      3126724.12     13842592.58
#Sta/Elev= 30
  3736.4   41.86  3956.4    36.7  4219.7   39.12  4289.7   35.18  4349.7   36.64
  4459.7   33.35    4607   35.52  4862.9   36.61  4872.9    35.2  4899.4   26.21
  4922.9   11.79  4942.9    3.51  4952.9    3.21  4956.9    6.18  4960.2    3.86
  4969.3   -12.8  4989.1  -21.29  4999.1  -23.03  5029.4  -14.45  5039.8    4.13
  5040.5    7.06  5112.9    6.49  5132.9   11.23  5152.9   11.28  5182.9   19.41
  5207.2   20.92  5629.9   23.94  5749.9   28.34  5809.9   27.45  6309.9   44.98
#Mann= 6 ,-1 , 0
  3736.4     .12       0    4607      .1       0  4899.4     .08       0
  4956.9    .035       0  5040.5     .08       0  5207.2     .12       0
Bank Sta=4956.9,5040.5
XS Rating Curve= 0
Exp/Cntr=.5,.3

Type RM Length L Ch R = 1 ,102875.3,55.6,55.6,55.6
BEGIN DESCRIPTION:
Upstream Section of Bridge/Culvert/Weir
END DESCRIPTION:
XS GIS Cut Line= 6
      3127985.33     13844309.67      3127958.12     13843969.43
      3127873.28     13843647.96      3127752.73     13843344.35
       3127324.1     13842652.29      3127105.88     13842354.95
#Sta/Elev= 30
  3453.5   39.25  3483.5   38.95  3503.5   36.25  3624.5   34.75  4035.2   34.75
  4181.3   30.55  4437.3   33.95  4464.1   37.22  4606.2   37.08  4711.9   29.88
  4756.7   15.54  4782.4   11.32  4956.7    2.82  4956.9    2.82  4960.2      .5
  4969.3  -16.16  4989.1  -24.65  4999.1  -26.39  5029.4  -17.81  5039.8     .77
  5040.5     3.7  5051.2    3.56  5070.4    7.52  5141.2    31.6    5152   34.17
  5202.1   36.94    5286    29.9  5355.1   30.37    5437   34.95    5637   40.75
#Mann= 6 ,-1 , 0
  3453.5     .15       0  4756.7     .07       0  4956.7     .04       0
  4956.9    .035       0  5040.5     .04       0  5141.2     .15       0
#XS Ineff= 2 , 0
            4700    36.4    5165            40.5
Permanent Ineff=
       F       F
Bank Sta=4956.9,5040.5
XS Rating Curve= 0
Exp/Cntr=.5,.3

Type RM Length L Ch R = 3 ,102847.5,,,
BEGIN DESCRIPTION:
HOUSTON BELT AND TERMINAL RR
Structure ID: WOO-12
END DESCRIPTION:
Bridge Culvert--1,0,-1,-1, 0
Deck Dist Width WeirC Skew NumUp NumDn MinLoCord MaxHiCord MaxSubmerge Is_Ogee
10,35.6,2.6,0, 55, 55, , , .95, 0, 1,1,,
  3453.5  3483.5  3503.5  3583.5  3594.5  3614.5  3624.5  3714.5  3734.5  3774.5
  3804.5  3824.5  3844.5  3865.2  3875.2  3975.2  4035.2  4075.2  4085.2  4095.2
  4121.3  4141.3  4171.3  4181.3  4201.3  4211.3  4251.3  4261.3  4437.3 4456.69
  4456.8  4464.1  4528.4  4606.2  4664.1  4711.9 4713.01  4713.1 5151.19  5151.3
    5152  5202.1    5286  5345.3 5345.41  5355.1    5357    5407    5437    5487
    5517    5567    5597  5613.1    5637
   39.21   38.91   36.46   36.59   36.61   36.64   36.66    36.8   36.83   36.89
   36.94   36.97      37   37.04   37.05   37.21    37.3   37.37   37.38    37.4
   37.44   37.47   37.52   37.53   37.57   37.58   37.65   37.66   37.94   37.97
   38.97      39   39.23   39.53   39.79      40      40      40   40.87   40.87
   40.87   40.96   41.09   41.44   40.44   40.47   40.48   40.65   40.75   40.92
   41.02   41.19    41.3   41.35   40.71
   39.21   38.91   36.21   35.21   36.01   35.61   34.71   35.21   33.71   34.71
   35.21   34.31   33.91   33.61   34.31   35.11   34.71   33.01   32.91   32.41
   32.71   31.21   31.31   30.51   30.51   30.91   30.91   30.61   33.91   36.28
   36.29   37.18   36.87   37.04   32.91   29.84   29.53   35.01   35.88   33.96
   34.13    36.9   29.86   30.27   30.28   30.33   31.51   32.81   34.91   35.21
   37.71   38.01   40.41   40.53   40.71
  3453.5  3483.5  3503.5  3583.5  3594.5  3614.5  3624.5  3714.5  3734.5  3774.5
  3804.5  3824.5  3844.5  3865.2  3875.2  3975.2  4035.2  4075.2  4085.2  4095.2
  4121.3  4141.3  4171.3  4181.3  4201.3  4211.3  4251.3  4261.3  4437.3 4456.69
  4456.8  4464.1  4528.4  4606.2  4664.1  4711.9 4713.01  4713.1 5151.19  5151.3
    5152  5202.1    5286  5345.3 5345.41  5355.1    5357    5407    5437    5487
    5517    5567    5597  5613.1    5637
    39.2   38.91   36.46   36.59   36.61   36.64   36.66    36.8   36.83   36.89
   36.94   36.97      37   37.04   37.05   37.21    37.3   37.37   37.38    37.4
   37.44   37.47   37.52   37.53   37.57   37.58   37.65   37.66   37.94   37.97
   38.97      39   39.23   39.53   39.79      40      40      40   40.87   40.87
   40.87   40.96   41.09   41.44   40.44   40.47   40.48   40.65   40.75   40.92
   41.02   41.19    41.3   41.35    40.7
   39.15   38.85   36.15   35.15   35.95   35.55   34.65   35.15   33.65   34.65
   35.15   34.25   33.85   33.55   34.25   35.05   34.65   32.95   32.85   32.35
   32.65   31.15   31.25   30.45   30.45   30.85   30.85   30.55   33.85   36.22
   36.23   37.12   36.81   36.98   32.85   29.78   29.47   34.95   35.82    33.9
   34.07   36.84    29.8   30.21   30.22   30.27   31.45   32.75   34.85   35.15
   37.65   37.95   40.35   40.47   40.65
Pier Skew, UpSta & Num, DnSta & Num=  ,4741.8, 2 ,4741.8, 2 , 0 , 0 , 0 ,,
       2       2
   19.57   36.07
       2       2
   19.51   36.01
Pier Skew, UpSta & Num, DnSta & Num=  ,4769.7, 2 ,4769.7, 2 , 0 , 0 , 0 ,,
       2       2
   11.53   36.12
       2       2
   11.47   36.06
Pier Skew, UpSta & Num, DnSta & Num=  ,4795.4, 2 ,4795.4, 2 , 0 , 0 , 0 ,,
       2       2
   10.22   36.17
       2       2
   10.16   36.11
Pier Skew, UpSta & Num, DnSta & Num=  ,4818.5, 2 ,4818.5, 2 , 0 , 0 , 0 ,,
       2       2
    9.78   36.22
       2       2
    9.72   36.16
Pier Skew, UpSta & Num, DnSta & Num=  ,4846.5, 2 ,4846.5, 2 , 0 , 0 , 0 ,,
       2       2
    6.82   36.28
       2       2
    6.76   36.22
Pier Skew, UpSta & Num, DnSta & Num=  ,4872.4, 2 ,4872.4, 2 , 0 , 0 , 0 ,,
       2       2
    6.45   36.33
       2       2
    6.39   36.27
Pier Skew, UpSta & Num, DnSta & Num=  ,4894.4, 2 ,4894.4, 2 , 0 , 0 , 0 ,,
       2       2
    5.01   36.37
       2       2
    4.95   36.31
Pier Skew, UpSta & Num, DnSta & Num=  ,4921.7, 2 ,4921.7, 2 , 0 , 0 , 0 ,,
       2       2
    4.18   36.42
       2       2
    4.12   36.36
Pier Skew, UpSta & Num, DnSta & Num=  ,4946.4, 2 ,4946.4, 2 , 0 , 0 , 0 ,,
       8       8
    1.82   36.48
       8       8
    1.76   36.42
Pier Skew, UpSta & Num, DnSta & Num=  ,5051.2, 2 ,5051.2, 2 , 0 , 0 , 0 ,,
       8       8
    2.57   36.69
       8       8
    2.51   36.63
Pier Skew, UpSta & Num, DnSta & Num=  ,5077.8, 2 ,5077.8, 2 , 0 , 0 , 0 ,,
       2       2
    9.03   36.73
       2       2
    8.97   36.67
Pier Skew, UpSta & Num, DnSta & Num=  ,5098.1, 2 ,5098.1, 2 , 0 , 0 , 0 ,,
       2       2
   16.23   36.77
       2       2
   16.17   36.71
Pier Skew, UpSta & Num, DnSta & Num=  ,5124, 2 ,5124, 2 , 0 , 0 , 0 ,,
       2       2
   25.19   36.83
       2       2
   25.13   36.77
Abutment Skew #Up #Dn= , 2 , 2
  4712.9  4782.5
   35.01   11.28
  4712.9  4782.5
   34.95   11.22
BR Coef= 1 , 1 , 0 ,1.25, 0 ,,,.8,0,2,0,
WSPro=,,,, 1 ,,,, 0 ,,,, 0 ,,,,-1 ,-1 ,-1 , 0 , 0 , 0 , 0 , 0
BR U #Sta/Elev= 115
  3453.5   39.21  3458.9   39.16  3463.1   39.11  3483.5   38.91  3503.5   36.21
  3583.5   35.21  3594.5   36.01  3614.5   35.61  3624.5   34.71  3714.5   35.21
  3734.5   33.71  3774.5   34.71  3804.5   35.21  3824.5   34.31  3844.5   33.91
  3845.2   33.91  3865.2   33.61  3875.2   34.31  3975.2   35.11  4035.2   34.71
  4075.2   33.01  4085.2   32.91  4095.2   32.41  4121.3   32.71  4141.3   31.21
  4171.3   31.31  4181.3   30.51  4201.3   30.51  4211.3   30.91  4251.3   30.91
  4261.3   30.61  4437.3   33.91  4456.6   36.26 4456.69   36.28  4456.8   36.29
 4456.91    36.3  4464.1   37.18  4509.7   36.96  4528.4   36.87  4570.3   36.96
  4606.2   37.04  4642.2   34.47  4664.1   32.91  4711.9   29.84  4712.8   29.59
  4712.9   29.57 4713.01   29.53  4713.1   29.51  4730.7   24.67  4741.8   20.96
    4755   15.87  4756.7    15.5  4769.7   12.63  4778.6   11.73  4782.4   11.28
  4782.5   11.28  4795.4   11.23  4805.4    11.1  4818.5   10.94    4833    8.61
  4846.5    7.85  4857.6     7.5  4872.4    7.58    4882    6.34  4894.4    6.05
  4906.7    5.56  4921.7    5.26  4923.9    5.09  4946.4    2.84  4956.7    2.78
  4956.9    2.78  4960.2     .46  4969.3   -16.2  4989.1  -24.69  4999.1  -26.43
  5009.3  -23.82  5019.3   -20.7  5029.4  -17.85  5039.8     .73  5040.5    3.66
  5051.2    3.52  5070.4    7.48  5077.8   10.43  5088.1   14.62  5098.1   17.52
  5113.1   23.25    5124   26.49  5137.9   30.78  5141.2   31.56    5151   33.89
  5151.1   33.92 5151.19   33.94  5151.3   33.96  5151.4   33.99    5152   34.13
  5202.1    36.9  5204.7   36.68    5246   33.22    5286   29.86  5295.8   29.93
  5345.1   30.27 5345.19   30.27  5345.3   30.27 5345.41   30.28  5354.7   30.34
  5355.1   30.33    5357   31.51    5407   32.81    5437   34.91    5487   35.21
    5517   37.71    5567   38.01    5597   40.41  5613.1   40.53    5637   40.71
BR U #Mann= 6
  3453.5     .15  4756.7     .07  4956.7     .04  4956.9    .035  5040.5     .04
  5141.2     .15
BR U Banks=4956.9,5040.5
BR D #Sta/Elev= 115
  3453.5   39.15  3458.9    39.1  3463.1   39.05  3483.5   38.85  3503.5   36.15
  3583.5   35.15  3594.5   35.95  3614.5   35.55  3624.5   34.65  3714.5   35.15
  3734.5   33.65  3774.5   34.65  3804.5   35.15  3824.5   34.25  3844.5   33.85
  3845.2   33.85  3865.2   33.55  3875.2   34.25  3975.2   35.05  4035.2   34.65
  4075.2   32.95  4085.2   32.85  4095.2   32.35  4121.3   32.65  4141.3   31.15
  4171.3   31.25  4181.3   30.45  4201.3   30.45  4211.3   30.85  4251.3   30.85
  4261.3   30.55  4437.3   33.85  4456.6    36.2 4456.69   36.22  4456.8   36.23
 4456.91   36.24  4464.1   37.12  4509.7    36.9  4528.4   36.81  4570.3    36.9
  4606.2   36.98  4642.2   34.41  4664.1   32.85  4711.9   29.78  4712.8   29.53
  4712.9   29.51 4713.01   29.47  4713.1   29.45  4730.7   24.61  4741.8    20.9
    4755   15.81  4756.7   15.44  4769.7   12.57  4778.6   11.67  4782.4   11.22
  4782.5   11.22  4795.4   11.17  4805.4   11.04  4818.5   10.88    4833    8.55
  4846.5    7.79  4857.6    7.44  4872.4    7.52    4882    6.28  4894.4    5.99
  4906.7     5.5  4921.7     5.2  4923.9    5.03  4946.4    2.78  4956.7    2.72
  4956.9    2.72  4960.2      .4  4969.3  -16.26  4989.1  -24.75  4999.1  -26.49
  5009.3  -23.88  5019.3  -20.76  5029.4  -17.91  5039.8     .67  5040.5     3.6
  5051.2    3.46  5070.4    7.42  5077.8   10.37  5088.1   14.56  5098.1   17.46
  5113.1   23.19    5124   26.43  5137.9   30.72  5141.2    31.5    5151   33.83
  5151.1   33.86 5151.19   33.88  5151.3    33.9  5151.4   33.93    5152   34.07
  5202.1   36.84  5204.7   36.62    5246   33.16    5286    29.8  5295.8   29.87
  5345.1   30.21 5345.19   30.21  5345.3   30.21 5345.41   30.22  5354.7   30.28
  5355.1   30.27    5357   31.45    5407   32.75    5437   34.85    5487   35.15
    5517   37.65    5567   37.95    5597   40.35  5613.1   40.47    5637   40.65
BR D #Mann= 6
  3453.5     .15  4756.7     .07  4956.7     .04  4956.9    .035  5040.5     .04
  5141.2     .15
BR D Banks=4956.9,5040.5
BC Design=,, 0 ,, 0 ,,,,,,
BC HTab HWMax=40.75

Type RM Length L Ch R = 1 ,102819.7,510.7,510.7,510.7
BEGIN DESCRIPTION:
Downstream Section of Bridge/Culvert/Weir
END DESCRIPTION:
XS GIS Cut Line= 6
      3128024.47     13844270.18      3127997.26     13843929.93
      3127912.42     13843608.46      3127791.87     13843304.85
      3127363.24     13842612.79      3127145.02     13842315.46
#Sta/Elev= 30
  3453.5   39.21  3483.5   38.91  3503.5   36.21  3624.5   34.71  4035.2   34.71
  4181.3   30.51  4437.3   33.91  4464.1   37.18  4606.2   37.04  4711.9   29.84
  4756.7    15.5  4782.4   11.28  4956.7    2.78  4956.9    2.78  4960.2     .46
  4969.3   -16.2  4989.1  -24.69  4999.1  -26.43  5029.4  -17.85  5039.8     .73
  5040.5    3.66  5051.2    3.52  5070.4    7.48  5141.2   31.56    5152   34.13
  5202.1    36.9    5286   29.86  5355.1   30.33    5437   34.91    5637   40.71
#Mann= 6 ,-1 , 0
  3453.5     .15       0  4756.7     .07       0  4956.7     .04       0
  4956.9    .035       0  5040.5     .04       0  5141.2     .15       0
#XS Ineff= 2 , 0
            4700    36.4    5165            40.5
Permanent Ineff=
       F       F
Bank Sta=4956.9,5040.5
XS Rating Curve= 0
Exp/Cntr=.5,.3

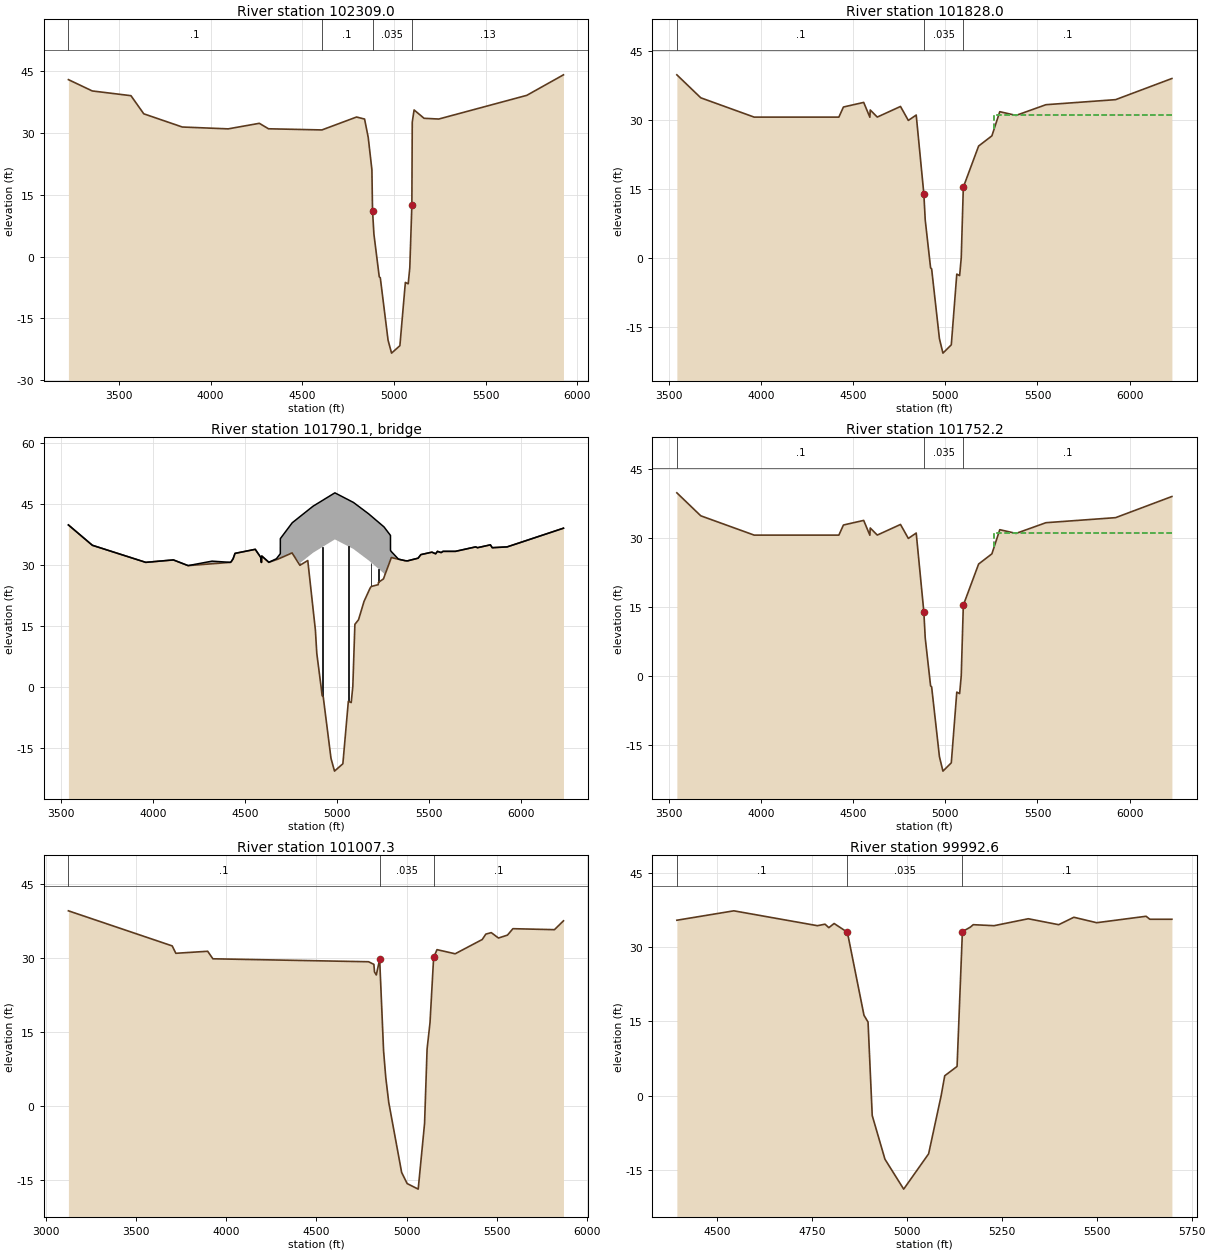
Type RM Length L Ch R = 1 ,102309.0,505.9,481,414.8
BEGIN DESCRIPTION:
Cross Section 102309.0-Interpolated
END DESCRIPTION:
XS GIS Cut Line= 5
      3128336.42     13844446.51      3128303.59     13844167.51
      3127980.83     13842914.75      3127948.01     13842591.99
      3127417.15     13841993.48
#Sta/Elev= 30
  3224.9   43.02  3354.9   40.27  3565.8   39.12  3635.8   34.71  3845.8    31.5
  4095.8   31.05  4265.8    32.4  4315.8   31.07    4607   30.79  4795.8   33.93
  4839.5   33.44  4859.5   28.96  4879.5   21.12  4882.9    11.2  4890.5    5.46
  4919.6   -4.93  4925.3   -5.15  4967.6  -20.33  4986.7  -23.48  5032.1  -21.67
  5061.9   -6.29  5077.4   -6.62  5086.1   -2.73  5097.4   12.62  5099.5   32.69
  5109.5   35.65  5163.9   33.62  5243.9   33.44  5723.9    39.2  5923.9   44.19
#Mann= 4 ,-1 , 0
  3224.9      .1       0    4607      .1       0  4882.9    .035       0
  5097.4     .13       0
Bank Sta=4882.9,5097.4
XS Rating Curve= 0
Exp/Cntr=.5,.3

Type RM Length L Ch R = 1 ,101828.0,75.8,75.8,75.8
BEGIN DESCRIPTION:
Upstream Section of Bridge/Culvert/Weir
END DESCRIPTION:
XS GIS Cut Line= 5
      3128462.15      13844252.9      3128544.51     13843099.98
      3128508.79     13842961.57      3128263.22     13842434.71
      3127842.48     13841743.94
#Sta/Elev= 30
  3541.4   39.84  3671.4   34.84  3961.4   30.64  4421.4   30.64  4446.2   32.84
  4556.2   33.84  4589.8   30.62  4591.8   32.19    4630   30.65  4756.2   32.96
  4798.7   29.92  4841.5   31.09  4882.9   13.98  4890.5    8.24  4919.6   -2.15
  4925.3   -2.37  4967.6  -17.55  4986.7   -20.7  5032.1  -18.89  5061.9   -3.51
  5077.4   -3.84  5086.1     .05  5097.4    15.4  5180.5   24.35  5252.6   26.57
  5295.4   31.82  5383.7   31.01  5545.9   33.34  5924.5   34.44  6230.3   39.04
#Mann= 3 ,-1 , 0
  3541.4      .1       0  4882.9    .035       0  5097.4      .1       0
#XS Ineff= 2 , 0
          4783.2   30.95    5265            31.1
Permanent Ineff=
       F       F
Bank Sta=4882.9,5097.4
XS Rating Curve= 0
Exp/Cntr=.5,.3

Type RM Length L Ch R = 3 ,101790.1,,,
BEGIN DESCRIPTION:
JENSEN ROAD
Structure ID: W00-11
END DESCRIPTION:
Bridge Culvert--1,0,-1,-1, 0
Deck Dist Width WeirC Skew NumUp NumDn MinLoCord MaxHiCord MaxSubmerge Is_Ogee
10,55.8,2.6,0, 47, 47, , , .95, 0, 1,1,,
  3541.4  3671.4  3961.4  4111.4  4191.4  4321.3  4421.4  4426.2  4436.2  4446.2
  4556.2  4586.2  4589.8  4591.8    4630  4671.1 4692.39  4692.5  4756.2  4756.8
  4798.7  4870.1  4988.7  5089.4  5171.9 5255.29  5255.4  5290.7 5290.81  5295.4
    5334  5371.1  5383.7  5440.7  5455.9  5515.9  5535.9  5545.9  5565.9  5575.9
  5643.4  5753.4  5763.4  5833.4  5843.4  5924.5  6230.3
    39.9    34.9    30.7    31.3    29.9      31    30.7   30.91   31.61   32.91
   33.91   31.91   30.69   32.26   30.72   31.59   32.84   36.54   40.39   40.43
   41.94   44.51    47.8   45.44   42.64   39.43   39.43   37.32   33.62   33.35
   31.49   31.11   31.08   31.73   32.61   33.21   32.81   33.41   33.11   33.41
   33.41   34.51   34.31   35.01   34.31   34.51    39.1
    39.9    34.9    30.7    31.3    29.9   30.35    30.7    30.9    31.6    32.9
    33.9    31.9   30.68   32.25   30.71   31.36   31.75   31.75   33.02   32.98
   30.49   33.06   36.35   33.99   31.19   27.98   26.97    31.3   31.32   31.88
   31.48    31.1   31.07   31.72    32.6    33.2    32.8    33.4    33.1    33.4
    33.4    34.5    34.3      35    34.3    34.5    39.1
  3541.4  3671.4  3961.4  4111.4  4191.4  4321.3  4421.4  4426.2  4436.2  4446.2
  4556.2  4586.2  4589.8  4591.8    4630  4671.1 4692.39  4692.5  4756.2  4756.8
  4798.7  4870.1  4988.7  5089.4  5171.9 5255.29  5255.4  5290.7 5290.81  5295.4
    5334  5371.1  5383.7  5440.7  5455.9  5515.9  5535.9  5545.9  5565.9  5575.9
  5643.4  5753.4  5763.4  5833.4  5843.4  5924.5  6230.3
    39.9    34.9    30.7    31.3    29.9      31    30.7   30.91   31.61   32.91
   33.91   31.91   30.69   32.26   30.72   31.59   32.84   36.54   40.39   40.43
   41.94   44.51    47.8   45.44   42.64   39.43   39.43   37.32   33.62   33.35
   31.49   31.11   31.08   31.73   32.61   33.21   32.81   33.41   33.11   33.41
   33.41   34.51   34.31   35.01   34.31   34.51    39.1
    39.8    34.8    30.6    31.2    29.8   30.25    30.6    30.8    31.5    32.8
    33.8    31.8   30.58   32.15   30.61   31.26   31.65   31.65   32.92   32.88
   30.39   32.96   36.25   33.89   31.09   27.88   26.87    31.2   31.22   31.78
   31.38      31   30.97   31.62    32.5    33.1    32.7    33.3      33    33.3
    33.3    34.4    34.2    34.9    34.2    34.4      39
Pier Skew, UpSta & Num, DnSta & Num=  ,4798.7, 2 ,4798.7, 2 , 0 , 0 , 0 ,,
     1.5     1.5
      29   31.53
     1.5     1.5
    28.9   31.43
Pier Skew, UpSta & Num, DnSta & Num=  ,4919.6, 2 ,4919.6, 2 , 0 , 0 , 0 ,,
       5       5
   -3.19    35.5
       5       5
   -3.29    35.4
Pier Skew, UpSta & Num, DnSta & Num=  ,5061.9, 2 ,5061.9, 2 , 0 , 0 , 0 ,,
       5       5
   -5.74   35.69
       5       5
   -5.84   35.59
Pier Skew, UpSta & Num, DnSta & Num=  ,5186.5, 2 ,5186.5, 2 , 0 , 0 , 0 ,,
     1.5     1.5
   23.73   31.66
     1.5     1.5
   23.62   31.56
Pier Skew, UpSta & Num, DnSta & Num=  ,5225.6, 2 ,5225.6, 2 , 0 , 0 , 0 ,,
     1.5     1.5
   24.52   30.15
     1.5     1.5
   24.42   30.05
Abutment Skew #Up #Dn= , 2 , 2
  5252.7 5255.49
   26.64   27.98
  5252.7 5255.49
   26.54   27.88
BR Coef= 1 , 1 , 0 ,1.25, 0 ,,,.8,0,2,0,
WSPro=,,,, 1 ,,,, 0 ,,,, 0 ,,,,-1 ,-1 ,-1 , 0 , 0 , 0 , 0 , 0
BR U #Sta/Elev= 83
  3541.4    39.9  3671.4    34.9  3961.4    30.7  4111.4    31.3  4191.4    29.9
  4321.3   30.35  4421.4    30.7  4426.2    30.9  4436.2    31.6  4446.2    32.9
  4556.2    33.9  4586.2    31.9  4588.3   31.19  4589.8   30.68  4591.8   32.25
  4623.9   30.96    4630   30.71  4671.1   31.36  4678.4   31.47  4691.7   31.73
 4692.39   31.75  4692.5   31.75 4692.61   31.75  4756.2   33.02  4756.8   32.98
  4756.9   32.97 4757.01   32.96  4757.1   32.96  4757.2   32.95  4798.7   29.98
  4841.5   31.15  4870.1   19.33  4882.9   14.04  4890.5     8.3  4913.8      .1
  4919.6   -2.09  4925.3   -2.31  4967.6  -17.49  4986.7  -20.64  4988.7  -20.56
  5032.1  -18.83  5061.9   -3.45  5077.4   -3.78  5086.1     .11  5089.4    4.59
  5097.4   15.46  5117.1   16.58    5147   21.09  5171.9   23.56  5180.5   24.41
  5186.5   24.77    5224   25.21  5225.6   25.79  5252.6   26.63  5252.7   26.64
    5253   26.68 5255.29   26.96  5255.4   26.97  5255.5   26.99 5290.59   31.29
  5290.7    31.3 5290.81   31.32  5295.4   31.88    5334   31.48  5371.1    31.1
  5382.3   31.07  5383.7   31.07  5426.6   31.56  5440.7   31.72  5455.9    32.6
  5515.9    33.2  5535.9    32.8  5545.9    33.4  5565.9    33.1  5575.9    33.4
  5643.4    33.4  5753.4    34.5  5763.4    34.3  5833.4      35  5843.4    34.3
  5924.5    34.5  5996.6   35.58  6230.3    39.1
BR U #Mann= 3
  3541.4      .1  4882.9    .035  5097.4      .1
BR U Banks=4882.9,5097.4
BR D #Sta/Elev= 83
  3541.4    39.8  3671.4    34.8  3961.4    30.6  4111.4    31.2  4191.4    29.8
  4321.3   30.25  4421.4    30.6  4426.2    30.8  4436.2    31.5  4446.2    32.8
  4556.2    33.8  4586.2    31.8  4588.3   31.09  4589.8   30.58  4591.8   32.15
  4623.9   30.86    4630   30.61  4671.1   31.26  4678.4   31.37  4691.7   31.63
 4692.39   31.65  4692.5   31.65 4692.61   31.65  4756.2   32.92  4756.8   32.88
  4756.9   32.87 4757.01   32.86  4757.1   32.86  4757.2   32.85  4798.7   29.88
  4841.5   31.05  4870.1   19.23  4882.9   13.94  4890.5     8.2  4913.8       0
  4919.6   -2.19  4925.3   -2.41  4967.6  -17.59  4986.7  -20.74  4988.7  -20.66
  5032.1  -18.93  5061.9   -3.55  5077.4   -3.88  5086.1     .01  5089.4    4.49
  5097.4   15.36  5117.1   16.48    5147   20.99  5171.9   23.46  5180.5   24.31
  5186.5   24.67    5224   25.11  5225.6   25.69  5252.6   26.53  5252.7   26.54
    5253   26.58 5255.29   26.86  5255.4   26.87  5255.5   26.89 5290.59   31.19
  5290.7    31.2 5290.81   31.22  5295.4   31.78    5334   31.38  5371.1      31
  5382.3   30.97  5383.7   30.97  5426.6   31.46  5440.7   31.62  5455.9    32.5
  5515.9    33.1  5535.9    32.7  5545.9    33.3  5565.9      33  5575.9    33.3
  5643.4    33.3  5753.4    34.4  5763.4    34.2  5833.4    34.9  5843.4    34.2
  5924.5    34.4  5996.6   35.48  6230.3      39
BR D #Mann= 3
  3541.4      .1  4882.9    .035  5097.4      .1
BR D Banks=4882.9,5097.4
BC Design=,, 0 ,, 0 ,,,,,,
BC HTab HWMax=39.84

Type RM Length L Ch R = 1 ,101752.2,744.9,744.9,744.9
BEGIN DESCRIPTION:
Downstream Section of Bridge/Culvert/Weir
END DESCRIPTION:
XS GIS Cut Line= 5
      3128534.04     13844228.86      3128616.39     13843075.94
      3128580.67     13842937.53       3128335.1     13842410.67
      3127914.36      13841719.9
#Sta/Elev= 30
  3541.4   39.85  3671.4   34.85  3961.4   30.65  4421.4   30.65  4446.2   32.85
  4556.2   33.85  4589.8   30.63  4591.8    32.2    4630   30.66  4756.2   32.97
  4798.7   29.93  4841.5    31.1  4882.9   13.99  4890.5    8.25  4919.6   -2.14
  4925.3   -2.36  4967.6  -17.54  4986.7  -20.69  5032.1  -18.88  5061.9    -3.5
  5077.4   -3.83  5086.1     .06  5097.4   15.41  5180.5   24.36  5252.6   26.58
  5295.4   31.83  5383.7   31.02  5545.9   33.35  5924.5   34.45  6230.3   39.05
#Mann= 3 ,-1 , 0
  3541.4      .1       0  4882.9    .035       0  5097.4      .1       0
#XS Ineff= 2 , 0
          4783.2   30.95    5265            31.1
Permanent Ineff=
       F       F
Bank Sta=4882.9,5097.4
XS Rating Curve= 0
Exp/Cntr=.5,.3

Type RM Length L Ch R = 1 ,101007.3,975,1014.7,1005.4
BEGIN DESCRIPTION:
Cross Section 101007.3
END DESCRIPTION:
XS GIS Cut Line= 4
      3129681.77     13844347.83      3129348.41     13843199.58
      3129143.02     13842275.35      3129028.51     13841686.41
#Sta/Elev= 30
  3126.3   39.63  3701.3    32.5  3721.3      31  3897.8   31.41  3926.6   29.88
  4788.8   29.28  4818.5   28.75  4821.9    27.2  4831.9    26.6  4850.5   29.78
  4872.2   11.19  4884.2     5.8  4900.8      .7  4972.2  -13.53  5002.8   -15.8
    5064  -16.93  5099.3   -3.57  5113.2   11.54  5129.4   16.89  5149.5   30.15
  5168.2   31.74  5268.7    30.9  5418.7    33.8  5438.7    34.9  5468.7    35.2
  5508.7    34.1  5558.7    34.7  5588.7      36  5818.7    35.8  5868.7    37.6
#Mann= 3 ,-1 , 0
  3126.3      .1       0  4850.5    .035       0  5149.5      .1       0
Bank Sta=4850.5,5149.5
XS Rating Curve= 0
Exp/Cntr=.3,.1

Type RM Length L Ch R = 1 ,99992.6 ,1796.9,1593.2,1447.1
BEGIN DESCRIPTION:
Cross Section 99992.6
END DESCRIPTION:
XS GIS Cut Line= 3
       3130125.3     13843445.15      3130120.84     13842610.21
      3129888.66     13842203.91
#Sta/Elev= 27
  4395.1    35.4  4545.1    37.3  4765.1    34.3  4785.1    34.6  4795.1    33.9
    4809   34.74  4843.9   32.98  4887.6   16.21  4898.3   14.83  4909.3   -4.04
  4942.8  -12.86  4992.1   -18.9  5057.7  -11.77  5090.7    -.03  5100.1    3.99
  5132.6    5.88  5146.6    33.1  5167.6   34.01  5175.1    34.5    5230    34.3
    5320    35.7    5400    34.5    5440      36    5500    34.9    5630    36.2
    5640    35.6    5698    35.6
#Mann= 3 ,-1 , 0
  4395.1      .1       0  4843.9    .035       0  5146.6      .1       0
Bank Sta=4843.9,5146.6
XS Rating Curve= 0
Exp/Cntr=.3,.1

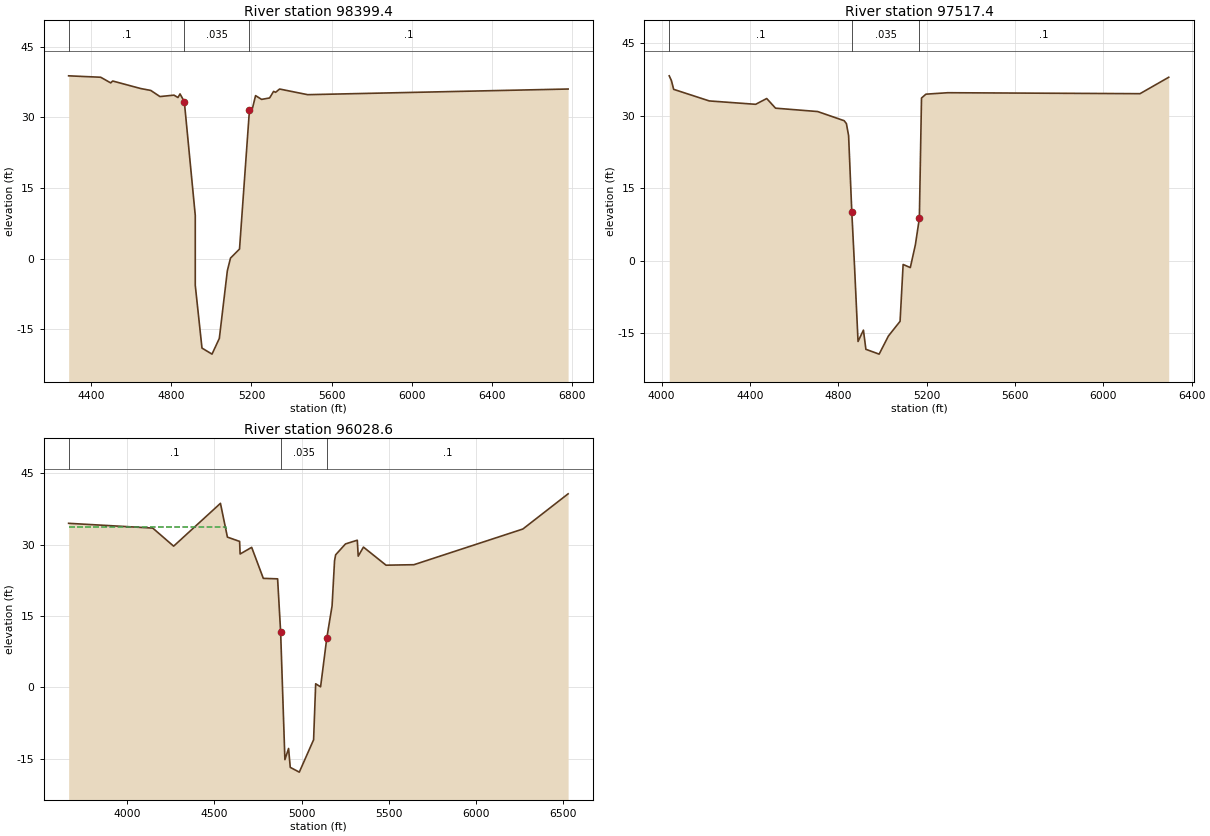
Type RM Length L Ch R = 1 ,98399.4 ,754.1,882,938.1
BEGIN DESCRIPTION:
Cross Section 98399.4
END DESCRIPTION:
XS GIS Cut Line= 5
      3132228.27     13842864.71      3131853.22     13842605.75
      3131437.98     13842413.76       3131067.4     13841860.11
      3130571.79     13841092.15
#Sta/Elev= 29
  4287.7    38.8  4447.7    38.5  4497.7    37.3  4507.7    37.7  4647.7    36.1
  4697.7    35.7  4743.5    34.4  4813.5    34.7  4833.5    34.2  4843.8   34.96
  4865.2   33.32  4919.8    9.21  4919.9   -5.68  4953.4  -18.98  5003.5  -20.26
    5040  -16.92    5080   -2.57  5095.8     .12  5140.8    2.04  5190.3   31.51
  5205.4   31.91  5220.9    34.6  5250.9    33.8  5290.9    34.1  5310.9    35.5
  5320.9    35.3  5340.9      36  5480.9    34.8  6781.2      36
#Mann= 3 ,-1 , 0
  4287.7      .1       0  4865.2    .035       0  5190.3      .1       0
Bank Sta=4865.2,5190.3
XS Rating Curve= 0
Exp/Cntr=.3,.1

Type RM Length L Ch R = 1 ,97517.4 ,1470,1488.8,1328.3
BEGIN DESCRIPTION:
Cross Section 97517.4-Interpolated
END DESCRIPTION:
XS GIS Cut Line= 5
      3132046.69     13842535.09      3131943.95     13842385.87
      3131937.32     13841895.08      3131592.44     13841417.55
      3130931.21     13840667.31
#Sta/Elev= 28
    4035    38.3    4045    37.3    4055    35.5  4216.2    33.1  4426.2    32.4
  4476.2    33.6  4516.2    31.6    4707    30.9    4827      29    4837    28.4
    4847    25.9  4861.4   10.13  4873.7   -1.07  4889.7  -16.73  4914.1  -14.38
  4925.2  -18.35  4985.2  -19.35  5027.3  -15.59    5080  -12.55  5093.8    -.78
  5126.3   -1.42  5149.2    3.28  5167.3    8.78    5177    33.7    5197    34.5
  5296.1    34.8  6166.1    34.6  6296.1      38
#Mann= 3 ,-1 , 0
    4035      .1       0  4861.4    .035       0  5167.3      .1       0
Bank Sta=4861.4,5167.3
XS Rating Curve= 0
Exp/Cntr=.5,.3

Type RM Length L Ch R = 1 ,96028.6 ,87,87,87
BEGIN DESCRIPTION:
Upstream Section of Bridge/Culvert/Weir
END DESCRIPTION:
XS GIS Cut Line= 6
      3133848.17       13843149.       3133479.6     13842676.28
      3133363.51     13842569.12      3133305.47     13842430.71
      3133039.48      13842093.1      3132180.79     13840826.11
#Sta/Elev= 30
  3662.7   34.49  4145.6   33.49  4265.6   29.69  4534.4   38.69  4574.4   31.59
  4644.4   30.69 4647.35   28.04  4713.7   29.44 4780.56   22.92 4862.65   22.82
 4879.97   11.67 4904.48  -15.19 4925.61  -12.84 4935.22  -16.81 4987.18  -17.81
 5069.28  -11.01 5081.23     .76 5109.38     .12 5144.88   10.32 5175.36   17.14
 5189.57   26.62 5195.89   27.87 5252.35   30.16 5320.16   30.94  5325.5   27.59
  5355.5   29.49  5485.2   25.69  5645.2   25.79  6270.8   33.29  6530.7   40.69
#Mann= 3 ,-1 , 0
  3662.7      .1       0 4879.97    .035       0 5144.88      .1       0
#XS Ineff= 2 , 0
            4565    33.7    5400            27.7
Permanent Ineff=
       F       F
Bank Sta=4879.97,5144.88
XS Rating Curve= 0
Exp/Cntr=.5,.3