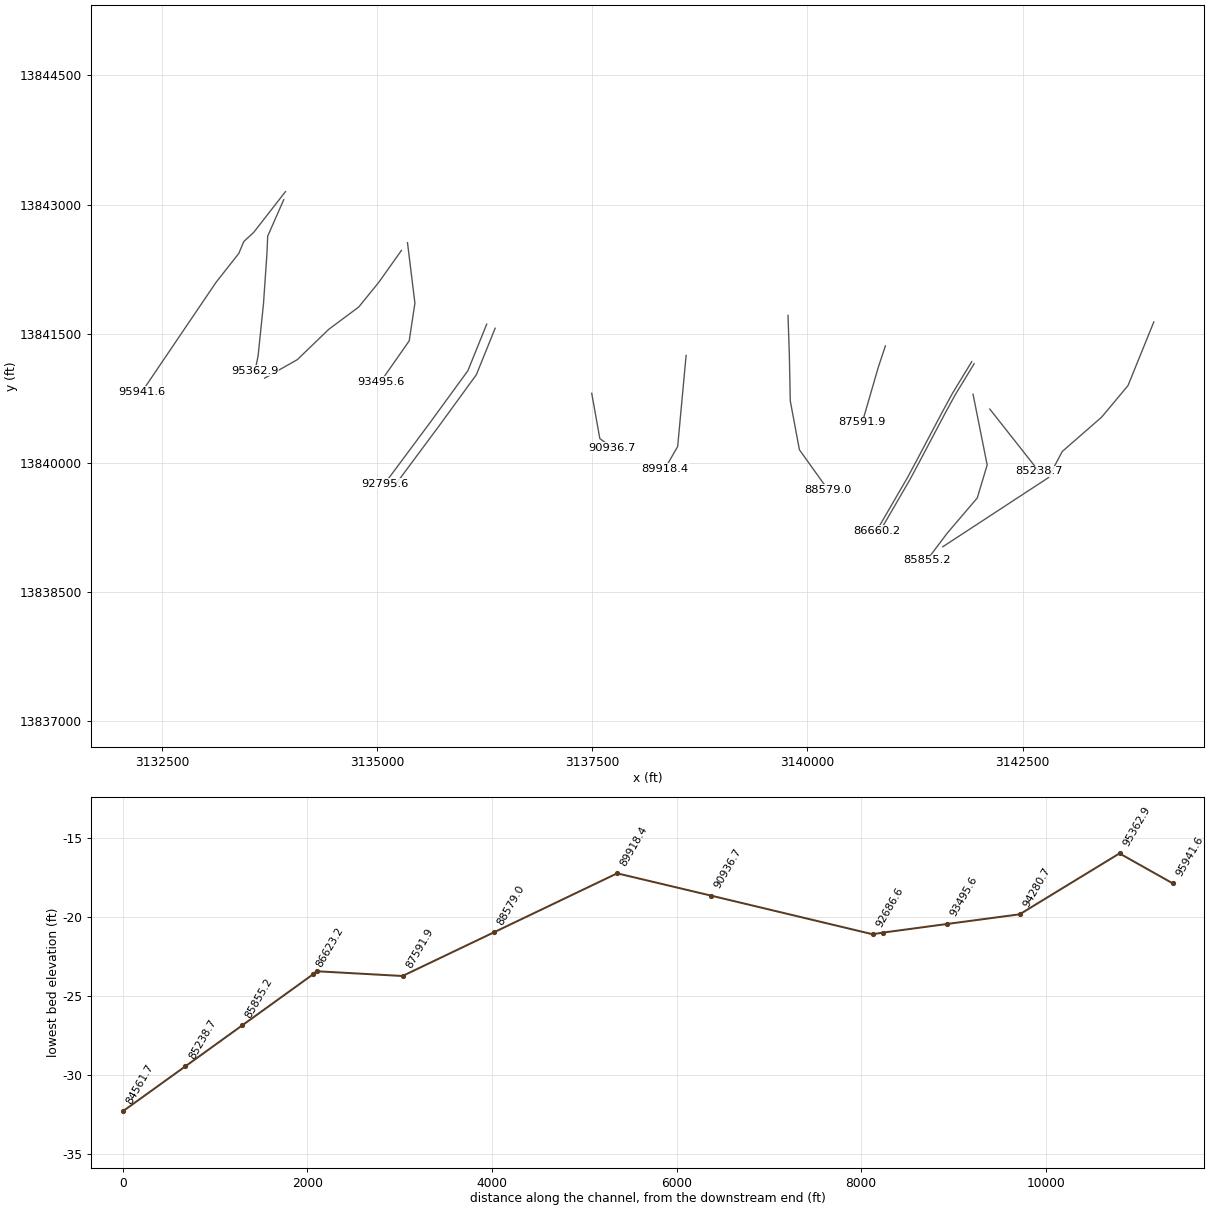
HEC-RAS study W100-00-00.prj: W100-00-00

--- W100-00-00.g01 (geometry) --- (continued)

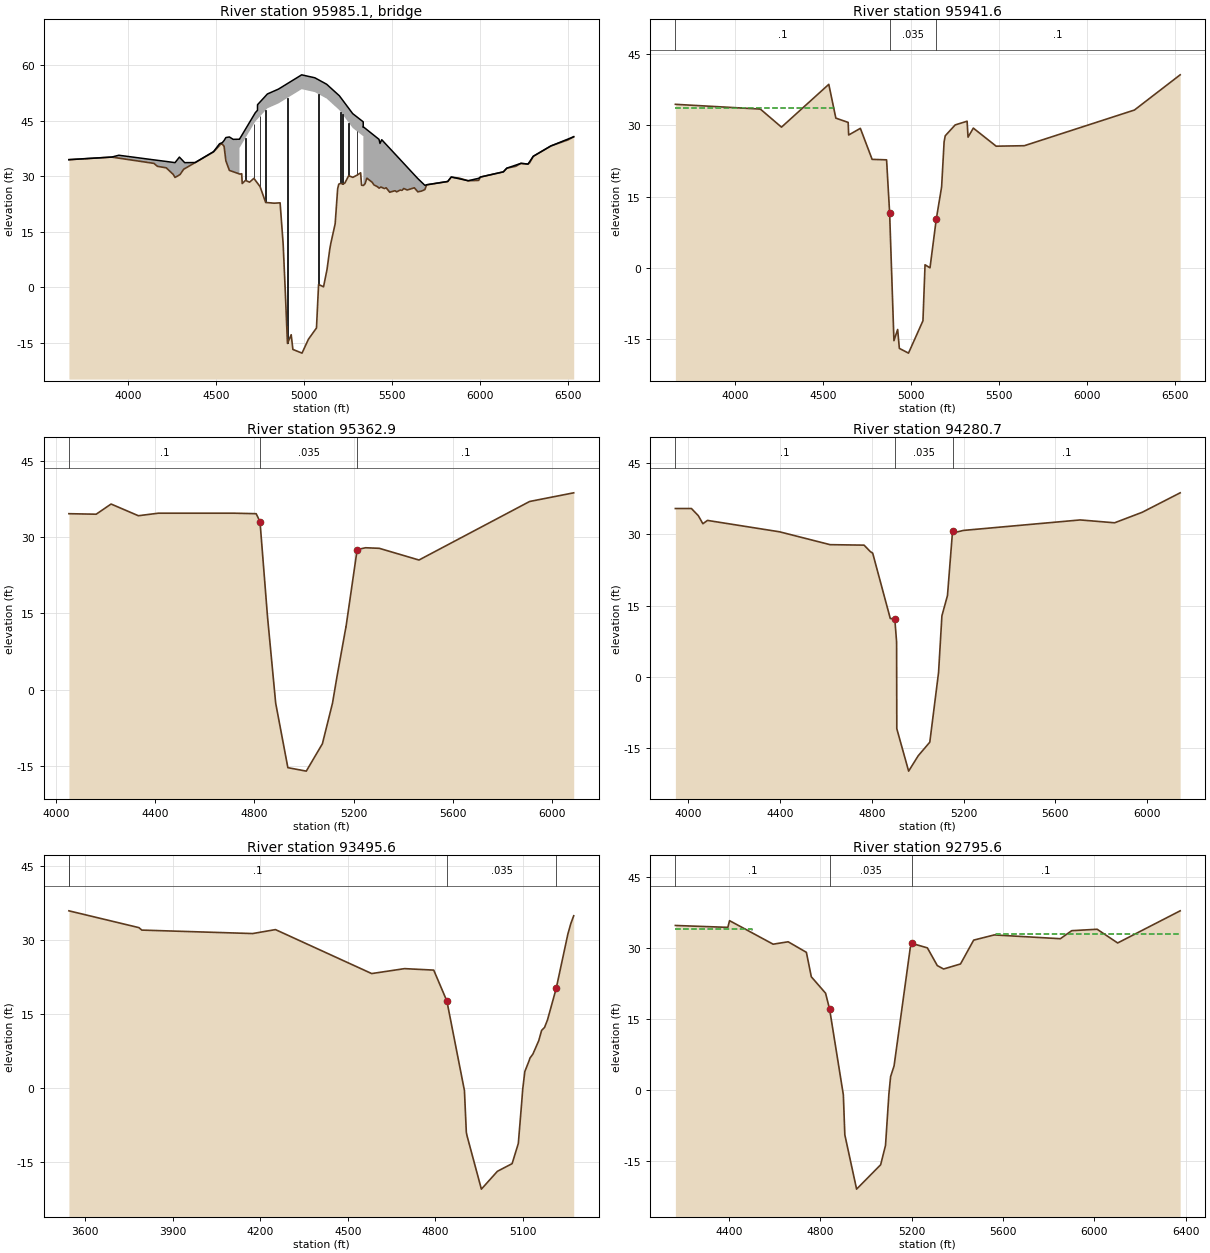
Type RM Length L Ch R = 3 ,95985.1 ,,,
BEGIN DESCRIPTION:
YORK DRIVE - 30 Degree Skew
Structure ID: W00-9
END DESCRIPTION:
Bridge Culvert--1,0,-1,-1, 0
Deck Dist Width WeirC Skew NumUp NumDn MinLoCord MaxHiCord MaxSubmerge Is_Ogee
10,67,2.6,0, 60, 60, , , .95, 0, 1,1,,
  3662.7  3905.6  3946.4  4145.6  4165.6  4215.6  4265.6  4290.4  4320.4  4380.4
  4484.5  4518.4  4534.4  4544.4  4554.4  4574.4 4595.75 4631.77 4631.86 4721.75
 4734.19  4734.3 4790.51 4852.78  4985.1 5059.93 5126.96 5199.27 5275.04 5334.87
 5334.98 5335.62 5335.73  5345.5  5355.5 5424.51  5430.1  5440.1  5465.2  5485.2
  5515.2  5525.2  5565.2  5585.2  5625.2  5645.2    5685    5695    5815    5835
  5930.8  5990.8  6000.8  6130.8  6150.8  6230.8  6270.8  6300.8  6400.8  6530.7
    34.5    35.2    35.7   34.45   34.33   34.02    33.7    35.2    33.7   33.73
   36.68    38.8   39.12   39.68   40.48   40.64      40   40.03   40.04    47.2
   47.86   49.36   52.27   53.57   57.44   56.64    54.9   51.78   46.95   44.73
   43.23   43.35   43.37      43   42.62      40    38.9    39.9   38.61   37.59
   36.05   35.54   33.49   32.46   30.41   29.39   27.57   27.71   28.61   29.81
   28.81   29.47   29.81   31.21   32.21   33.51   33.31   35.41   38.21    40.7
    34.5    35.2   34.91    33.5    32.7    32.3    29.7   30.38   32.06   33.72
    36.6   38.34    38.7    38.1    34.2    31.6   31.24   30.64   37.66   44.82
   45.48   45.48   48.39   49.69   53.56   52.76   51.02    47.9   43.07   40.85
   40.85   40.97   27.51      28    29.5   26.83   26.95      27    26.9    25.7
    26.1    25.8    26.7    26.3    26.9    25.8    26.4    27.7    28.6    29.8
    28.8    28.9    29.8    31.2    32.2    33.5    33.3    35.4    38.2    40.7
  3662.7  3905.6  3946.4  4145.6  4165.6  4215.6  4265.6  4290.4  4320.4  4380.4
  4484.5  4518.4  4534.4  4544.4  4554.4  4574.4 4595.75 4631.77 4631.86 4721.75
 4734.19  4734.3 4790.51 4852.78  4985.1 5059.93 5126.96 5199.27 5275.04 5334.87
 5334.98 5335.62 5335.73  5345.5  5355.5 5424.51  5430.1  5440.1  5465.2  5485.2
  5515.2  5525.2  5565.2  5585.2  5625.2  5645.2    5685    5695    5815    5835
  5930.8  5990.8  6000.8  6130.8  6150.8  6230.8  6270.8  6300.8  6400.8  6530.7
    34.5    35.2    35.7   34.45   34.33   34.02    33.7    35.2    33.7   33.73
   36.68    38.8   39.12   39.68   40.48   40.64      40   40.03   40.04    47.2
   47.86   49.36   52.27   53.57   57.44   56.64    54.9   51.78   46.95   44.73
   43.23   43.35   43.37      43   42.62      40    38.9    39.9   38.61   37.59
   36.05   35.54   33.49   32.46   30.41   29.39   27.57   27.71   28.61   29.81
   28.81   29.47   29.81   31.21   32.21   33.51   33.31   35.41   38.21    40.7
    34.4    35.1   34.81    33.4    32.6    32.2    29.6   30.28   31.96   33.62
    36.5   38.24    38.6      38    34.1    31.5   31.14   30.54   37.56   44.72
   45.38   45.38   48.29   49.59   53.46   52.66   50.92    47.8   42.97   40.75
   40.75   40.87   27.41    27.9    29.4   26.73   26.85    26.9    26.8    25.6
      26    25.7    26.6    26.2    26.8    25.7    26.3    27.6    28.5    29.7
    28.7    28.8    29.7    31.1    32.1    33.4    33.2    35.3    38.1    40.6
Pier Skew, UpSta & Num, DnSta & Num=  ,4665.9, 2 ,4665.9, 2 , 0 , 0 , 0 ,,
     2.5     2.5
   27.85   41.47
     2.5     2.5
   27.75   41.37
Pier Skew, UpSta & Num, DnSta & Num=  ,4713.7, 2 ,4713.7, 2 , 0 , 0 , 0 ,,
     2.5     2.5
   28.37   45.28
     2.5     2.5
   28.27   45.18
Pier Skew, UpSta & Num, DnSta & Num=  ,4748.8, 2 ,4748.8, 2 , 0 , 0 , 0 ,,
     2.5     2.5
   26.05   47.29
     2.5     2.5
   25.95   47.19
Pier Skew, UpSta & Num, DnSta & Num=  ,4780.6, 2 ,4780.6, 2 , 0 , 0 , 0 ,,
     2.5     2.5
   21.92   48.94
     2.5     2.5
   21.82   48.84
Pier Skew, UpSta & Num, DnSta & Num=  ,4904.5, 2 ,4904.5, 2 , 0 , 0 , 0 ,,
     2.5     2.5
  -16.04   52.24
     2.5     2.5
  -16.14   52.14
Pier Skew, UpSta & Num, DnSta & Num=  ,5081.2, 2 ,5081.2, 2 , 0 , 0 , 0 ,,
     2.5     2.5
   -1.46   53.24
     2.5     2.5
   -1.56   53.14
Pier Skew, UpSta & Num, DnSta & Num=  ,5206.5, 2 ,5206.5, 2 , 0 , 0 , 0 ,,
     2.5     2.5
   27.08   48.52
     2.5     2.5
   26.98   48.42
Pier Skew, UpSta & Num, DnSta & Num=  ,5217.5, 2 ,5217.5, 2 , 0 , 0 , 0 ,,
     2.5     2.5
   26.91   47.82
     2.5     2.5
   26.81   47.72
Pier Skew, UpSta & Num, DnSta & Num=  ,5252.4, 2 ,5252.4, 2 , 0 , 0 , 0 ,,
     2.5     2.5
   29.06    45.6
     2.5     2.5
   28.96    45.5
Pier Skew, UpSta & Num, DnSta & Num=  ,5300.1, 2 ,5300.1, 2 , 0 , 0 , 0 ,,
     2.5     2.5
    29.3   43.19
     2.5     2.5
    29.2   43.09
Abutment Skew #Up #Dn= , 2 , 2
 4631.66 4647.45
   37.66   28.05
 4631.66 4647.45
   37.56   27.95
Abutment Skew #Up #Dn= , 2 , 2
 5320.25 5335.82
   30.89   40.97
 5320.25 5335.82
   30.79   40.87
BR Coef= 1 , 1 , 0 ,1.25, 0 ,,,.8,0,2,0,
WSPro=,,,, 1 ,,,, 0 ,,,, 0 ,,,,-1 ,-1 ,-1 , 0 , 0 , 0 , 0 , 0
BR U #Sta/Elev= 146
  3662.7    34.5  3905.6    35.2  3946.4   34.91  4145.6    33.5  4165.6    32.7
  4215.6    32.3  4255.6    30.5  4265.6    29.7  4266.4   29.72  4274.5    29.9
  4280.4   30.08  4290.4   30.38  4294.5    30.5  4300.4   30.91  4314.5    31.9
  4320.4   32.06  4340.4   32.62  4350.4   32.89  4370.4   33.45  4380.4   33.72
  4400.4   34.27  4410.4   34.55  4420.4   34.83  4438.4   35.33  4468.4   36.15
  4478.4   36.43  4484.5    36.6  4498.4    37.3  4514.4    38.1  4518.4   38.34
  4524.4    38.7  4534.4    38.7  4538.4   38.46  4544.4    38.1  4554.4    34.2
  4558.4   33.68  4574.4    31.6  4588.4   31.37  4588.5   31.36 4595.75   31.24
 4631.66   30.65 4631.77   30.64 4631.86   30.64  4634.4    30.6  4644.4    30.7
 4647.35   28.05 4647.45   28.05  4665.9   28.91 4689.02   28.42  4713.7   29.45
 4721.75   28.94 4734.19   28.15  4734.3   28.14 4734.41   28.13 4748.77   27.22
 4780.56   22.93 4790.51   22.89 4829.05   22.74 4852.78    22.8 4862.65   22.83
 4879.97   11.68 4890.62     .48 4904.48  -15.18 4925.61  -12.83 4935.22   -16.8
  4985.1  -17.76 4987.18   -17.8 5023.64  -14.04 5059.93  -11.62 5069.28     -11
 5081.23     .77 5109.38     .13 5126.96     4.3 5129.21    4.83 5144.88   10.33
  5150.6   11.85 5175.36   17.15 5189.57   26.63 5195.89   27.88 5199.27   27.95
 5206.45   28.11 5214.68   28.02 5217.54   27.88 5230.36   28.17 5252.35   30.17
 5275.04   29.73 5275.82   29.72 5300.07   30.33 5320.16   30.95 5320.25   30.89
  5325.5    27.6 5334.76   27.51 5334.87   27.51 5334.98   27.51  5335.5    27.5
 5335.62   27.51 5335.73   27.51 5335.83   27.52  5345.5      28  5355.5    29.5
  5385.5    28.4  5395.5    27.7  5415.2    27.2 5424.51   26.83  5425.2    26.8
  5430.1   26.95  5435.2    27.1  5440.1      27  5455.2    26.7  5465.2    26.9
  5485.2    25.7  5515.2    26.1  5525.2    25.8  5545.2    26.3  5555.2    26.2
  5565.2    26.7  5585.2    26.3  5625.2    26.9  5645.2    25.8    5665      26
  5680.1    26.3    5685    26.4    5695    27.7  5790.1   28.41    5815    28.6
    5835    29.8  5850.8    29.7  5880.8    29.5  5930.8    28.8  5990.8    28.9
  5992.9   29.09  6000.8    29.8  6122.9   31.11  6130.8    31.2  6132.9    31.3
  6150.8    32.2  6200.8    32.7  6230.8    33.5  6270.8    33.3  6280.8    33.7
  6300.8    35.4  6362.9   37.14  6400.8    38.2  6407.1   38.31  6500.8    39.9
  6530.7    40.7
BR U #Mann= 3
  3662.7      .1 4879.97    .035 5144.88      .1
BR U Banks=4879.97,5144.88
BR D #Sta/Elev= 146
  3662.7    34.4  3905.6    35.1  3946.4   34.81  4145.6    33.4  4165.6    32.6
  4215.6    32.2  4255.6    30.4  4265.6    29.6  4266.4   29.62  4274.5    29.8
  4280.4   29.98  4290.4   30.28  4294.5    30.4  4300.4   30.81  4314.5    31.8
  4320.4   31.96  4340.4   32.52  4350.4   32.79  4370.4   33.35  4380.4   33.62
  4400.4   34.17  4410.4   34.45  4420.4   34.73  4438.4   35.23  4468.4   36.05
  4478.4   36.33  4484.5    36.5  4498.4    37.2  4514.4      38  4518.4   38.24
  4524.4    38.6  4534.4    38.6  4538.4   38.36  4544.4      38  4554.4    34.1
  4558.4   33.58  4574.4    31.5  4588.4   31.27  4588.5   31.26 4595.75   31.14
 4631.66   30.55 4631.77   30.54 4631.86   30.54  4634.4    30.5  4644.4    30.6
 4647.35   27.95 4647.45   27.95  4665.9   28.81 4689.02   28.32  4713.7   29.35
 4721.75   28.84 4734.19   28.05  4734.3   28.04 4734.41   28.03 4748.77   27.12
 4780.56   22.83 4790.51   22.79 4829.05   22.64 4852.78    22.7 4862.65   22.73
 4879.97   11.58 4890.62     .38 4904.48  -15.28 4925.61  -12.93 4935.22   -16.9
  4985.1  -17.86 4987.18   -17.9 5023.64  -14.14 5059.93  -11.72 5069.28   -11.1
 5081.23     .67 5109.38     .03 5126.96     4.2 5129.21    4.73 5144.88   10.23
  5150.6   11.75 5175.36   17.05 5189.57   26.53 5195.89   27.78 5199.27   27.85
 5206.45   28.01 5214.68   27.92 5217.54   27.78 5230.36   28.07 5252.35   30.07
 5275.04   29.63 5275.82   29.62 5300.07   30.23 5320.16   30.85 5320.25   30.79
  5325.5    27.5 5334.76   27.41 5334.87   27.41 5334.98   27.41  5335.5    27.4
 5335.62   27.41 5335.73   27.41 5335.83   27.42  5345.5    27.9  5355.5    29.4
  5385.5    28.3  5395.5    27.6  5415.2    27.1 5424.51   26.73  5425.2    26.7
  5430.1   26.85  5435.2      27  5440.1    26.9  5455.2    26.6  5465.2    26.8
  5485.2    25.6  5515.2      26  5525.2    25.7  5545.2    26.2  5555.2    26.1
  5565.2    26.6  5585.2    26.2  5625.2    26.8  5645.2    25.7    5665    25.9
  5680.1    26.2    5685    26.3    5695    27.6  5790.1   28.31    5815    28.5
    5835    29.7  5850.8    29.6  5880.8    29.4  5930.8    28.7  5990.8    28.8
  5992.9   28.99  6000.8    29.7  6122.9   31.01  6130.8    31.1  6132.9    31.2
  6150.8    32.1  6200.8    32.6  6230.8    33.4  6270.8    33.2  6280.8    33.6
  6300.8    35.3  6362.9   37.04  6400.8    38.1  6407.1   38.21  6500.8    39.8
  6530.7    40.6
BR D #Mann= 3
  3662.7      .1 4879.97    .035 5144.88      .1
BR D Banks=4879.97,5144.88
BC Design=,, 0 ,, 0 ,,,,,,
BC HTab HWMax=40.69

Type RM Length L Ch R = 1 ,95941.6 ,578.7,578.7,578.7
BEGIN DESCRIPTION:
Downstream Section of Bridge/Culvert/Weir
END DESCRIPTION:
XS GIS Cut Line= 6
      3133935.15     13843150.83      3133566.58      13842678.1
      3133450.49     13842570.94      3133392.45     13842432.53
      3133126.46     13842094.92      3132267.77     13840827.93
#Sta/Elev= 30
  3662.7   34.43  4145.6   33.43  4265.6   29.63  4534.4   38.63  4574.4   31.53
  4644.4   30.63 4647.35   27.98  4713.7   29.38 4780.56   22.86 4862.65   22.76
 4879.97   11.61 4904.48  -15.25 4925.61   -12.9 4935.22  -16.87 4987.18  -17.87
 5069.28  -11.07 5081.23      .7 5109.38     .06 5144.88   10.26 5175.36   17.08
 5189.57   26.56 5195.89   27.81 5252.35    30.1 5320.16   30.88  5325.5   27.53
  5355.5   29.43  5485.2   25.63  5645.2   25.73  6270.8   33.23  6530.7   40.63
#Mann= 3 ,-1 , 0
  3662.7      .1       0 4879.97    .035       0 5144.88      .1       0
#XS Ineff= 2 , 0
            4565    33.7    5400            27.7
Permanent Ineff=
       F       F
Bank Sta=4879.97,5144.88
XS Rating Curve= 0
Exp/Cntr=.5,.3

Type RM Length L Ch R = 1 ,95362.9 ,1333,1082.2,987.9
BEGIN DESCRIPTION:
Cross Section 95362.9
END DESCRIPTION:
XS GIS Cut Line= 6
      3133914.87     13843056.88      3133728.47     13842633.84
      3133719.55     13842431.62      3133679.36     13841846.72
      3133616.86     13841243.95      3133581.14     13841069.82
#Sta/Elev= 25
  4052.1    34.6  4162.1    34.5  4222.1    36.5  4332.1    34.2  4412.9    34.7
  4716.8    34.7  4806.8    34.6  4813.8   33.92  4822.6    32.9  4852.7   14.32
  4885.6   -2.63  4934.7  -15.29  5008.9  -15.97  5073.8   -10.6  5114.5   -2.63
  5132.7    2.61  5168.8   12.37  5168.9   12.37    5169   12.37    5214   27.56
    5248   27.91  5303.1    27.8  5463.1    25.5  5909.1      37  6086.8    38.7
#Mann= 3 ,-1 , 0
  4052.1      .1       0  4822.6    .035       0    5214      .1       0
Bank Sta=4822.6,5214
XS Rating Curve= 0
Exp/Cntr=.3,.1

Type RM Length L Ch R = 1 ,94280.7 ,559.4,785.1,841.1
BEGIN DESCRIPTION:
Cross Section 94280.7
END DESCRIPTION:
XS GIS Cut Line= 6
      3135282.26     13842467.34      3135018.83     13842096.75
      3134786.66       13841811.       3134438.4     13841552.03
      3134072.27     13841199.31      3133692.76     13840984.99
#Sta/Elev= 28
  3943.4    35.4  4013.4    35.4  4043.4    33.9  4063.4    32.2  4083.4    32.9
  4398.1    30.5  4618.1    27.8  4766.3    27.7  4792.9   26.37  4803.9   26.01
  4880.6   12.27  4900.2   12.21  4908.1    7.37    4909   -10.9  4960.6  -19.82
  5002.2   -16.6  5052.9  -13.73  5091.1     .93  5105.7   12.84    5130   17.11
    5152   30.61  5167.3   30.42  5200.1    30.8  5200.4    30.8  5708.8      33
  5858.8    32.4  5978.8    34.6  6144.7    38.7
#Mann= 3 ,-1 , 0
  3943.4      .1       0  4900.2    .035       0    5152      .1       0
Bank Sta=4900.2,5152
XS Rating Curve= 0
Exp/Cntr=.3,.1

Type RM Length L Ch R = 1 ,93495.6 ,850.3,700,696
BEGIN DESCRIPTION:
Cross Section 93495.6-Interpolated
END DESCRIPTION:
XS GIS Cut Line= 4
      3135352.97     13842558.31      3135439.19     13841855.28
      3135372.87     13841417.55      3135040.26     13840942.39
#Sta/Elev= 30
  3543.9    35.9  3783.9    32.5  3793.9      32  4173.9    31.3  4252.2    32.1
  4582.2    23.2  4694.9    24.2  4794.9    23.9    4840   17.65  4900.2    -.47
  4906.7   -8.94  4909.5   -9.72  4958.3  -20.43  5013.3  -16.82  5063.7  -15.27
    5085  -11.18  5097.6   -2.11  5099.9    -.27  5107.3    3.37  5122.5    5.64
  5124.9     6.1  5134.9     6.9  5154.9     9.6  5164.9    11.7  5174.9    12.3
  5184.9    13.8  5214.9    20.2  5254.9    31.2  5264.9    33.3  5274.9    34.9
#Mann= 4 ,-1 , 0
  3543.9      .2       0  3543.9      .1       0    4840    .035       0
  5214.9      .1       0
Bank Sta=4840,5214.9
XS Rating Curve= 0
Exp/Cntr=.5,.3

Type RM Length L Ch R = 1 ,92795.6 ,109,109,109
BEGIN DESCRIPTION:
Upstream Section of Bridge/Culvert/Weir
END DESCRIPTION:
XS GIS Cut Line= 4
      3136273.48      13841611.4       3136054.7     13841071.15
      3135621.61     13840477.32      3135087.87      13839760.1
#Sta/Elev= 30
  4164.1   34.81  4394.1   34.41  4401.5   35.83  4592.6   30.85  4658.3   31.36
  4738.2   29.13  4759.9   23.95  4822.3   20.48    4840    17.1  4900.2   -1.02
  4906.7   -9.49  4958.3  -20.98  5063.7  -15.82    5085  -11.73  5099.9    -.82
  5107.3    2.82  5122.5    5.09  5193.6   30.15  5202.1      31  5268.5   30.07
    5312   26.32  5339.6    25.6  5413.7   26.67  5471.3   31.71  5561.3   32.81
  5851.2   32.01  5901.2   33.71  6012.4   34.01  6102.4   31.11  6376.3   37.91
#Mann= 3 ,-1 , 0
  4164.1      .1       0    4840    .035       0  5202.1      .1       0
#XS Ineff= 2 , 0
            4500      34    5570              33
Permanent Ineff=
       F       F
Bank Sta=4840,5202.1
XS Rating Curve= 0
Exp/Cntr=.5,.3

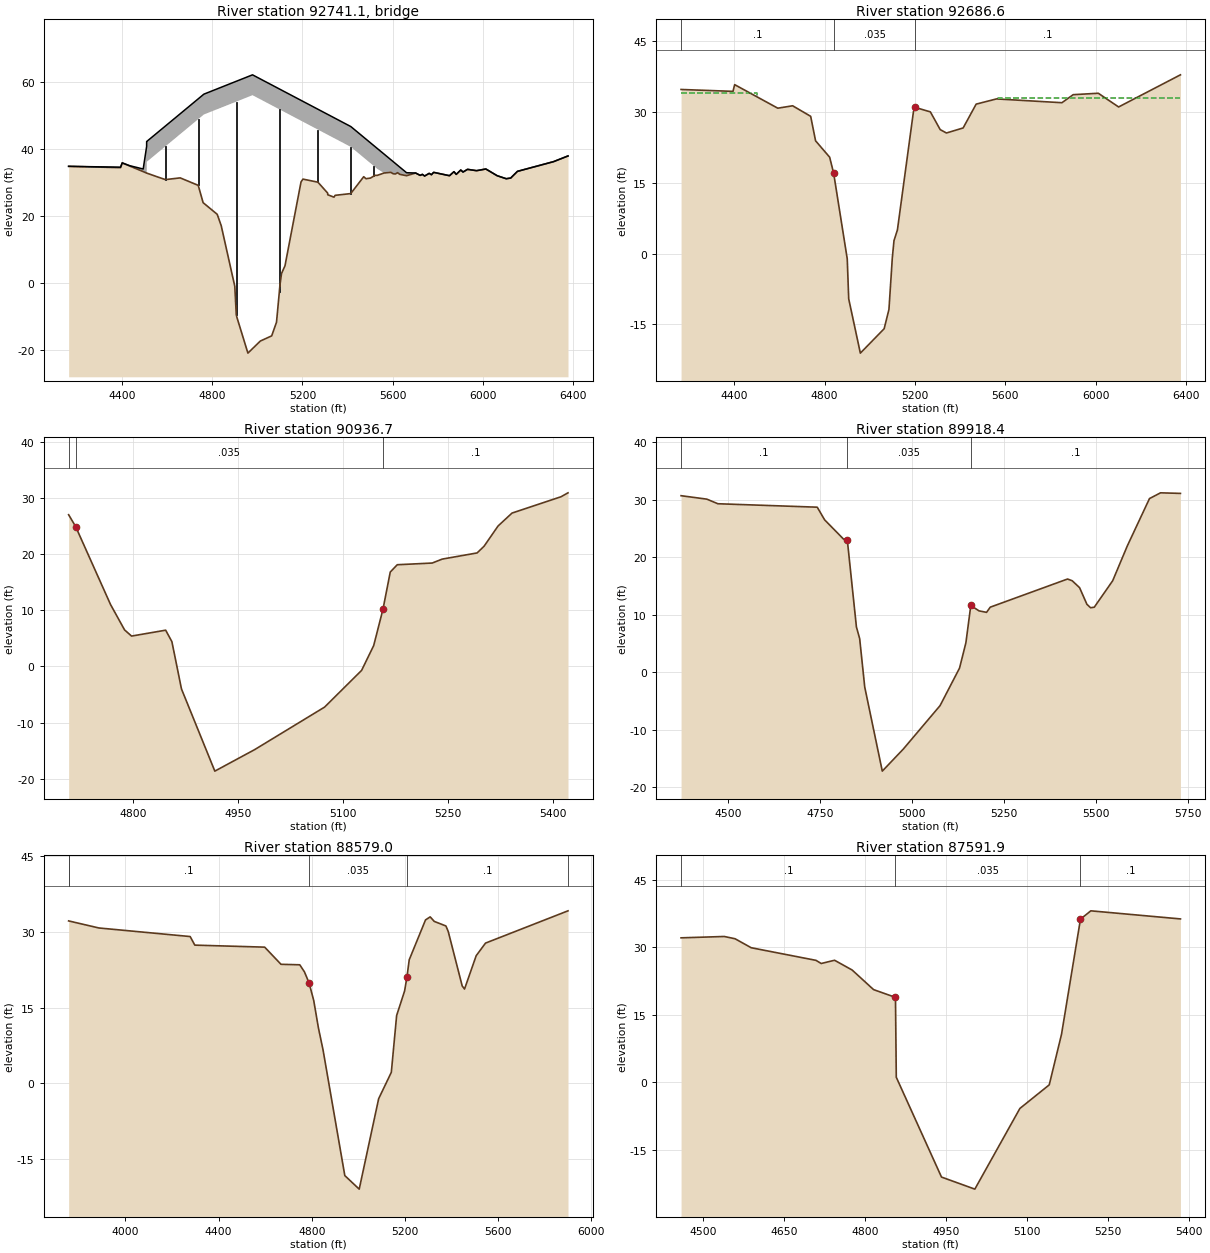
Type RM Length L Ch R = 3 ,92741.1 ,,,
BEGIN DESCRIPTION:
LOCKWOOD DRIVE
Structure ID: WOO-8
END DESCRIPTION:
Bridge Culvert--1,0,-1,-1, 0
Deck Dist Width WeirC Skew NumUp NumDn MinLoCord MaxHiCord MaxSubmerge Is_Ogee
10,89,2.6,0, 41, 41, , , .95, 0, 1,1,,
  4164.1  4394.1  4401.5  4434.4  4494.4 4509.59  4509.7 4510.11  4510.2  4763.2
  4978.7  5414.2  5531.3  5561.3  5591.3  5601.2  5611.2  5621.2  5631.2  5661.2
  5701.2  5721.2  5731.2  5741.2  5761.2  5771.2  5781.2  5851.2  5871.2  5881.2
  5901.2  5911.2  5931.2  5971.2  6012.4  6062.4  6102.4  6122.4  6152.4  6312.4
  6376.3
    34.8   34.55   35.83      35      34   40.72   42.22   42.23   42.23   56.36
   62.13   46.68   40.14   38.47   36.79   36.24   35.68   35.12   34.56   32.89
   32.81    32.1    32.4    31.9    32.7    32.3      33      32    33.2    32.4
    33.7    33.1    33.9    33.5      34      32    31.1    31.3    33.3    36.2
    37.9
    34.8    34.4   35.82    34.9   33.22    32.8    32.8   32.79   36.15   50.28
   56.05    40.6   34.06    32.8      33    32.6    32.5    32.9    32.4      32
    32.8    32.1    32.4    31.9    32.7    32.3      33      32    33.2    32.4
    33.7    33.1    33.9    33.5      34      32    31.1    31.3    33.3    36.2
    37.9
  4164.1  4394.1  4401.5  4434.4  4494.4 4509.59  4509.7 4510.11  4510.2  4763.2
  4978.7  5414.2  5531.3  5561.3  5591.3  5601.2  5611.2  5621.2  5631.2  5661.2
  5701.2  5721.2  5731.2  5741.2  5761.2  5771.2  5781.2  5851.2  5871.2  5881.2
  5901.2  5911.2  5931.2  5971.2  6012.4  6062.4  6102.4  6122.4  6152.4  6312.4
  6376.3
    34.8   34.55   35.83      35      34   40.72   42.22   42.23   42.23   56.36
   62.13   46.68   40.14   38.47   36.79   36.24   35.68   35.12   34.56   32.89
   32.81    32.1    32.4    31.9    32.7    32.3      33      32    33.2    32.4
    33.7    33.1    33.9    33.5      34      32    31.1    31.3    33.3    36.2
    37.9
    34.7    34.3   35.72    34.8   33.12    32.7    32.7   32.69   36.05   50.18
   55.95    40.5   33.96    32.7    32.9    32.5    32.4    32.8    32.3    31.9
    32.7      32    32.3    31.8    32.6    32.2    32.9    31.9    33.1    32.3
    33.6      33    33.8    33.4    33.9    31.9      31    31.2    33.2    36.1
    37.8
Pier Skew, UpSta & Num, DnSta & Num=  ,4592.6, 2 ,4592.6, 2 , 0 , 0 , 0 ,,
       3       3
   29.85   41.86
       3       3
   29.75   41.76
Pier Skew, UpSta & Num, DnSta & Num=  ,4738.2, 2 ,4738.2, 2 , 0 , 0 , 0 ,,
       3       3
   27.76   49.97
       3       3
   27.66   49.87
Pier Skew, UpSta & Num, DnSta & Num=  ,4906.7, 2 ,4906.7, 2 , 0 , 0 , 0 ,,
       5       5
   -11.2   55.19
       5       5
   -11.3   55.09
Pier Skew, UpSta & Num, DnSta & Num=  ,5097.6, 2 ,5097.6, 2 , 0 , 0 , 0 ,,
       5       5
   -5.47   52.92
       5       5
   -5.57   52.82
Pier Skew, UpSta & Num, DnSta & Num=  ,5268.5, 2 ,5268.5, 2 , 0 , 0 , 0 ,,
       4       4
   28.91   46.84
       4       4
   28.81   46.74
Pier Skew, UpSta & Num, DnSta & Num=  ,5413.7, 2 ,5413.7, 2 , 0 , 0 , 0 ,,
       3       3
   25.65   41.67
       3       3
   25.55   41.57
Pier Skew, UpSta & Num, DnSta & Num=  ,5514.7, 2 ,5514.7, 2 , 0 , 0 , 0 ,,
       3       3
   30.78   36.07
       3       3
   30.68   35.97
Pier Skew, UpSta & Num, DnSta & Num=  ,5615.5, 2 ,5615.5, 2 , 0 , 0 , 0 ,,
       3       3
   31.61   33.73
       3       3
   31.51   33.63
Abutment Skew #Up #Dn= , 2 , 2
    4510  4512.1
   36.15   32.73
    4510  4512.1
   36.05   32.63
Abutment Skew #Up #Dn= , 2 , 2
  5713.9 5715.79
   32.36    32.3
  5713.9 5715.79
   32.26    32.2
BR Coef= 1 , 1 , 0 ,1.25, 0 ,,,.8,0,2,0,
WSPro=,,,, 1 ,,,, 0 ,,,, 0 ,,,,-1 ,-1 ,-1 , 0 , 0 , 0 , 0 , 0
BR U #Sta/Elev= 87
  4164.1    34.8  4164.4    34.8  4394.1    34.4  4401.5   35.82  4434.4    34.9
  4494.4   33.22 4509.59    32.8  4509.7    32.8 4509.81   32.79  4509.9   32.79
    4510   32.79 4510.11   32.79  4510.2   32.78    4512   32.73  4512.1   32.73
  4552.9   31.76  4592.6   30.84  4631.5   31.14  4658.3   31.35  4738.2   29.12
  4759.9   23.94  4763.2   23.76  4822.3   20.47    4840   17.09  4900.2   -1.03
  4906.7    -9.5  4909.5  -10.28  4958.3  -20.99  4978.7  -19.65  5013.3  -17.38
  5063.7  -15.83    5085  -11.74  5097.6   -2.67  5099.9    -.83  5107.3    2.81
  5122.5    5.08  5193.6   30.14  5202.1   30.99  5268.5   30.06  5311.7    26.8
    5312   26.31  5339.6   25.59  5344.6   26.14  5413.7   26.66  5414.2    26.7
  5471.3    31.7  5481.3    31.1  5501.3    31.3  5521.3    32.1  5531.3    32.1
  5561.3    32.8  5591.3      33  5601.2    32.6  5611.2    32.5  5621.2    32.9
  5631.2    32.4  5661.2      32  5701.2    32.8  5713.9   32.36 5715.29   32.31
  5715.4    32.3 5715.51    32.3 5715.59    32.3  5715.7   32.29  5715.8   32.29
  5715.9   32.29  5721.2    32.1  5731.2    32.4  5741.2    31.9  5761.2    32.7
  5771.2    32.3  5781.2      33  5851.2      32  5871.2    33.2  5881.2    32.4
  5901.2    33.7  5911.2    33.1  5931.2    33.9  5971.2    33.5  6011.2      34
  6012.4      34  6062.4      32  6102.4    31.1  6122.4    31.3  6152.4    33.3
  6312.4    36.2  6376.3    37.9
BR U #Mann= 3
  4164.1      .1    4840    .035  5202.1      .1
BR U Banks=4840,5202.1
BR D #Sta/Elev= 87
  4164.1    34.7  4164.4    34.7  4394.1    34.3  4401.5   35.72  4434.4    34.8
  4494.4   33.12 4509.59    32.7  4509.7    32.7 4509.81   32.69  4509.9   32.69
    4510   32.69 4510.11   32.69  4510.2   32.68    4512   32.63  4512.1   32.63
  4552.9   31.66  4592.6   30.74  4631.5   31.04  4658.3   31.25  4738.2   29.02
  4759.9   23.84  4763.2   23.66  4822.3   20.37    4840   16.99  4900.2   -1.13
  4906.7    -9.6  4909.5  -10.38  4958.3  -21.09  4978.7  -19.75  5013.3  -17.48
  5063.7  -15.93    5085  -11.84  5097.6   -2.77  5099.9    -.93  5107.3    2.71
  5122.5    4.98  5193.6   30.04  5202.1   30.89  5268.5   29.96  5311.7    26.7
    5312   26.21  5339.6   25.49  5344.6   26.04  5413.7   26.56  5414.2    26.6
  5471.3    31.6  5481.3      31  5501.3    31.2  5521.3      32  5531.3      32
  5561.3    32.7  5591.3    32.9  5601.2    32.5  5611.2    32.4  5621.2    32.8
  5631.2    32.3  5661.2    31.9  5701.2    32.7  5713.9   32.26 5715.29   32.21
  5715.4    32.2 5715.51    32.2 5715.59    32.2  5715.7   32.19  5715.8   32.19
  5715.9   32.19  5721.2      32  5731.2    32.3  5741.2    31.8  5761.2    32.6
  5771.2    32.2  5781.2    32.9  5851.2    31.9  5871.2    33.1  5881.2    32.3
  5901.2    33.6  5911.2      33  5931.2    33.8  5971.2    33.4  6011.2    33.9
  6012.4    33.9  6062.4    31.9  6102.4      31  6122.4    31.2  6152.4    33.2
  6312.4    36.1  6376.3    37.8
BR D #Mann= 3
  4164.1      .1    4840    .035  5202.1      .1
BR D Banks=4840,5202.1
BC Design=,, 0 ,, 0 ,,,,,,
BC HTab HWMax=37.91

Type RM Length L Ch R = 1 ,92686.6 ,1749.9,1749.9,1749.9
BEGIN DESCRIPTION:
Downstream Section of Bridge/Culvert/Weir
END DESCRIPTION:
XS GIS Cut Line= 4
      3136371.68      13841564.1       3136152.9     13841023.85
      3135719.81     13840430.02      3135186.07     13839712.79
#Sta/Elev= 30
  4164.1   34.71  4394.1   34.31  4401.5   35.73  4592.6   30.75  4658.3   31.26
  4738.2   29.03  4759.9   23.85  4822.3   20.38    4840      17  4900.2   -1.12
  4906.7   -9.59  4958.3  -21.08  5063.7  -15.92    5085  -11.83  5099.9    -.92
  5107.3    2.72  5122.5    4.99  5193.6   30.05  5202.1    30.9  5268.5   29.97
    5312   26.22  5339.6    25.5  5413.7   26.57  5471.3   31.61  5561.3   32.71
  5851.2   31.91  5901.2   33.61  6012.4   33.91  6102.4   31.01  6376.3   37.81
#Mann= 3 ,-1 , 0
  4164.1      .1       0    4840    .035       0  5202.1      .1       0
#XS Ineff= 2 , 0
            4500      34    5570              33
Permanent Ineff=
       F       F
Bank Sta=4840,5202.1
XS Rating Curve= 0
Exp/Cntr=.5,.3

Type RM Length L Ch R = 1 ,90936.7 ,1075.1,1018.3,980.1
BEGIN DESCRIPTION:
Cross Section 90936.7-Interpolated
END DESCRIPTION:
XS GIS Cut Line= 3
      3137493.81     13840809.29      3137588.07     13840283.42
      3137733.26     13840177.12
#Sta/Elev= 24
  4707.8      27  4717.8    24.9  4767.8      11  4787.8     6.5  4797.8     5.4
  4846.6    6.45  4855.5     4.4  4869.2   -4.01  4916.9  -18.64  4973.9  -14.81
  5073.9   -7.24  5126.8    -.71  5144.1    3.71  5157.4   10.19  5167.8    16.8
  5177.8    18.1  5227.8    18.4    5242    19.1    5292    20.2    5302    21.4
    5322      25    5342    27.3    5412    30.2    5422    30.9
#Mann= 3 ,-1 , 0
  4707.8      .1       0  4717.8    .035       0  5157.4      .1       0
Bank Sta=4717.8,5157.4
XS Rating Curve= 0
Exp/Cntr=.3,.1

Type RM Length L Ch R = 1 ,89918.4 ,1273.9,1339.4,1374.1
BEGIN DESCRIPTION:
Cross Section 89918.4
END DESCRIPTION:
XS GIS Cut Line= 3
      3138590.75     13841248.42      3138492.53     13840190.24
      3138345.18     13839935.74
#Sta/Elev= 30
  4372.2    30.7  4442.2    30.1  4472.2    29.3  4742.2    28.7  4762.2    26.5
  4813.4   23.16  4823.9   22.97  4848.6    7.86  4857.5    5.81  4871.2    -2.6
  4918.9  -17.23  4975.9   -13.4  5075.9   -5.83  5128.8      .7  5146.1    5.12
  5159.4    11.6  5181.6   10.66  5202.2    10.4  5212.2    11.3  5422.2    16.2
  5434.9    15.9  5454.9    14.7  5474.9    11.8  5484.9    11.2  5494.9    11.3
  5544.9    15.9  5584.9      22  5644.9    30.2  5674.9    31.2    5729    31.1
#Mann= 3 ,-1 , 0
  4372.2      .1       0  4823.9    .035       0  5159.4      .1       0
Bank Sta=4823.9,5159.4
XS Rating Curve= 0
Exp/Cntr=.3,.1

Type RM Length L Ch R = 1 ,88579.0 ,1140.6,987.1,947.4
BEGIN DESCRIPTION:
Cross Section 88579.0-Interpolated
END DESCRIPTION:
XS GIS Cut Line= 5
      3139774.75     13841713.35      3139790.67     13841251.74
      3139801.28     13840721.16       3139907.4     13840153.43
      3140241.67     13839686.51
#Sta/Elev= 30
  3756.1    32.2  3886.1    30.8    4278    29.1    4298    27.4    4598      27
    4668    23.6  4748.7    23.5  4768.7    22.1  4788.7    19.9  4808.7    16.4
  4828.7      11  4848.7     6.6  4942.1  -18.29  5003.9  -20.97  5087.4   -3.05
  5141.8    2.19  5164.6   13.44  5198.7    18.3  5208.7      21  5218.7    24.5
  5288.7    32.4  5308.7      33  5326.2    32.1  5376.2    31.2  5386.2    30.1
  5446.2    19.3  5456.2    18.7  5506.2    25.3  5546.2    27.8  5900.5    34.2
#Mann= 5 ,-1 , 0
  3756.1      .2       0  3756.1      .1       0  4788.7    .035       0
  5208.7      .1       0  5900.5      .2       0
Bank Sta=4788.7,5208.7
XS Rating Curve= 0
Exp/Cntr=.3,.1

Type RM Length L Ch R = 1 ,87591.9 ,852.8,931.7,817
BEGIN DESCRIPTION:
Cross Section 87591.9
END DESCRIPTION:
XS GIS Cut Line= 3
       3140906.7     13841359.15      3140824.54     13841112.69
       3140638.8     13840473.31
#Sta/Elev= 19
  4459.4    32.1  4539.4    32.4  4559.4    31.9  4589.4    29.9  4709.4    27.1
  4719.2    26.4  4743.9   27.12  4776.5   24.95  4816.2    20.6  4856.8   18.87
  4858.3    1.13  4942.1  -21.04  5003.9  -23.72  5087.4    -5.8  5141.8    -.56
  5164.6   10.69  5199.7   36.25  5218.9    38.1    5385    36.3
#Mann= 3 ,-1 , 0
  4459.4      .1       0  4856.8    .035       0  5199.7      .1       0
Bank Sta=4856.8,5199.7
XS Rating Curve= 0
Exp/Cntr=.5,.3

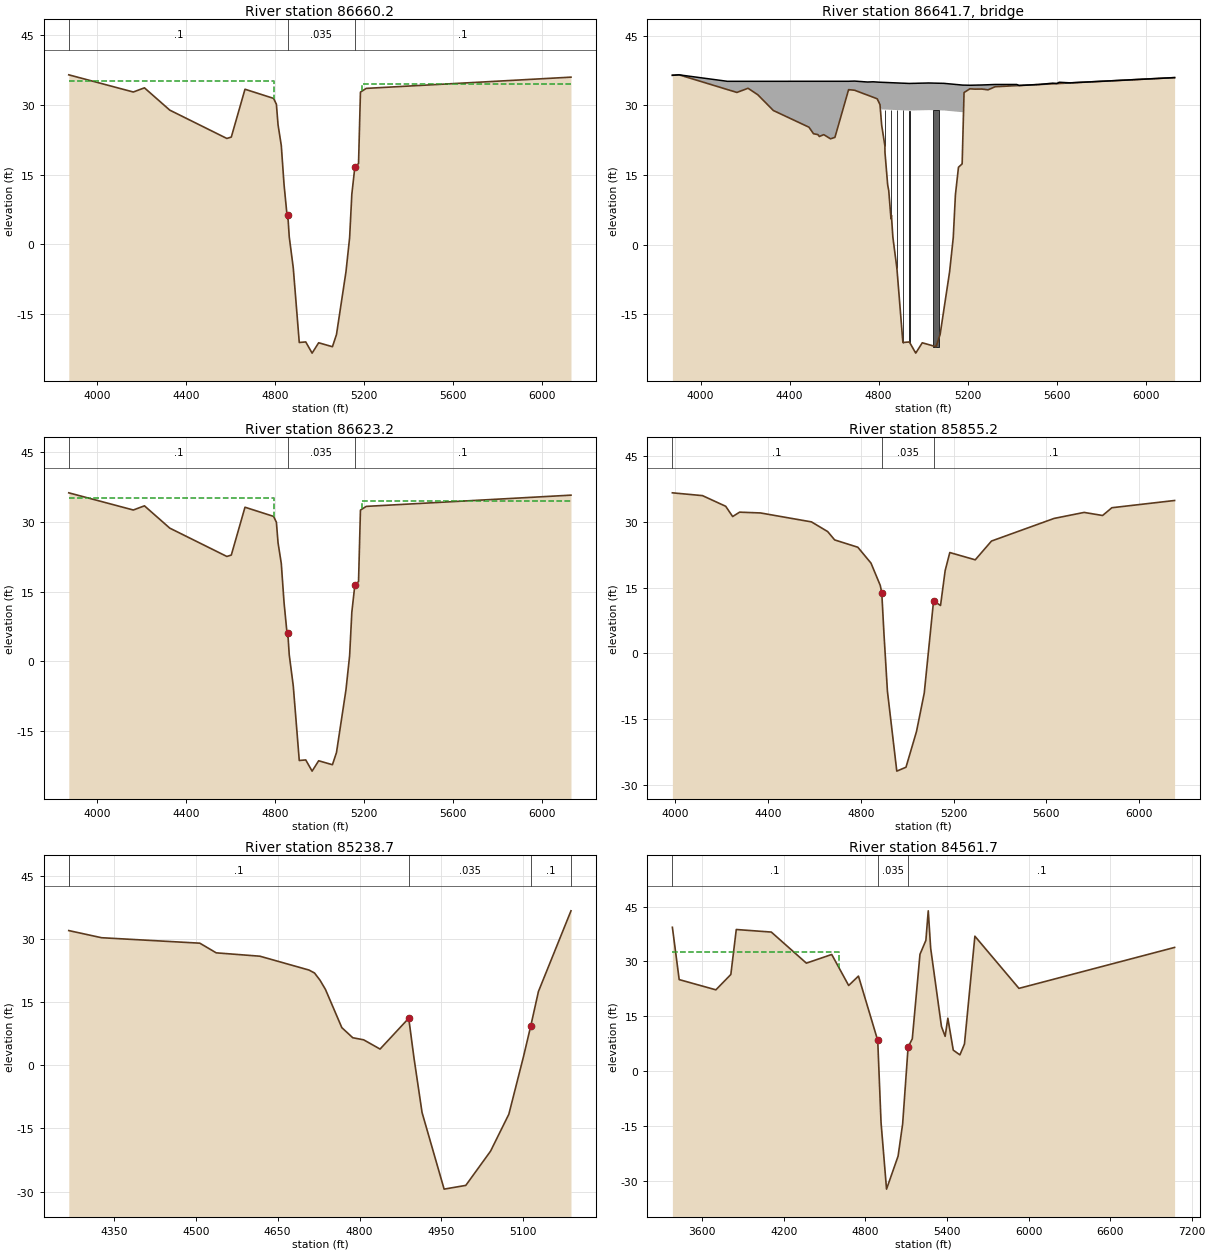
Type RM Length L Ch R = 1 ,86660.2 ,37,37,37
BEGIN DESCRIPTION:
Upstream Section of Bridge/Culvert/Weir
END DESCRIPTION:
XS GIS Cut Line= 6
       3141910.3     13841176.48      3141689.49     13840814.31
      3141564.47     13840585.71        3141268.     13840024.91
      3141164.41     13839832.03      3140803.65     13839210.52
#Sta/Elev= 30
  3873.7    36.5  4163.7    32.8  4213.7    33.7  4327.5    28.9    4584    22.8
    4604    23.1  4665.5    33.4  4793.8   31.43  4806.6   30.17    4814   25.76
  4828.6   21.28    4841   12.87  4855.9    5.55  4857.9    6.33  4864.3    1.63
  4882.4   -5.06  4909.4  -21.13  4938.5  -21.01  4967.1  -23.42  4996.5  -21.19
  5058.4  -22.04  5076.6  -19.42  5119.3   -5.89  5135.7    1.48  5145.5   10.76
  5159.2   16.67  5175.7   17.39  5184.3   32.78  5210.2   33.58  6130.3      36
#Mann= 3 ,-1 , 0
  3873.7      .1       0  4857.9    .035       0  5159.2      .1       0
#XS Ineff= 2 , 0
            4795    35.2    5190            34.5
Permanent Ineff=
       F       F
Bank Sta=4857.9,5159.2
XS Rating Curve= 0
Exp/Cntr=.5,.3

Type RM Length L Ch R = 3 ,86641.7 ,,,
BEGIN DESCRIPTION:
HOUSTON BELT AND TERMINAL RR
Structure ID: WOO-7
END DESCRIPTION:
Bridge Culvert--1,0,-1,-1, 0
Deck Dist Width WeirC Skew NumUp NumDn MinLoCord MaxHiCord MaxSubmerge Is_Ogee
10,17,2.6,0, 39, 39, , , .95, 0, 1,1,,
  3873.7  3903.7  4121.1  4163.7  4213.7  4257.5  4327.5  4487.5  4507.5  4527.5
    4534    4554    4584    4604  4665.5  4691.9  4750.6  4776.1  4793.8  4806.6
    4814  4937.3  5025.2  5094.3 5179.09  5179.2  5184.3  5210.2  5264.2  5292.1
  5323.9  5421.1  5431.7  5521.7  5581.7  5601.7  5611.7  5661.7  6130.3
    36.5    36.6    35.2    35.2    35.2    35.2    35.2   35.21   35.21   35.21
   35.21   35.21   35.21   35.21   35.21   35.25   35.05    35.1   35.04      35
   34.99   34.74   34.84   34.76   34.38   34.38   34.38   34.35   34.41   34.46
   34.52   34.52    34.3   34.52    34.8   34.72      35   34.87      36
    36.5    36.6   33.42    32.8    33.7    32.3    28.9    25.3    23.9    23.7
    23.3    23.7    22.8    23.1    33.4   33.28   32.22   31.76   31.43   30.17
   29.14   28.89   28.99   28.91   28.53   23.65   32.78   33.58   33.53   33.36
   34.03   34.27   34.29   34.51   34.66   34.71   34.73   34.86      36
  3873.7  3903.7  4121.1  4163.7  4213.7  4257.5  4327.5  4487.5  4507.5  4527.5
    4534    4554    4584    4604  4665.5  4691.9  4750.6  4776.1  4793.8  4806.6
    4814  4937.3  5025.2  5094.3 5179.09  5179.2  5184.3  5210.2  5264.2  5292.1
  5323.9  5421.1  5431.7  5521.7  5581.7  5601.7  5611.7  5661.7  6130.3
    36.5    36.6    35.2    35.2    35.2    35.2    35.2   35.21   35.21   35.21
   35.21   35.21   35.21   35.21   35.21   35.25   35.05    35.1   35.04      35
   34.99   34.74   34.84   34.76   34.38   34.38   34.38   34.35   34.41   34.46
   34.52   34.52    34.3   34.52    34.8   34.72      35   34.87      36
   36.35   36.45   33.27   32.65   33.55   32.15   28.75   25.15   23.75   23.55
   23.15   23.55   22.65   22.95   33.25   33.13   32.07   31.61   31.28   30.02
   28.99   28.74   28.84   28.76   28.38    23.5   32.63   33.43   33.38   33.21
   33.88   34.12   34.14   34.36   34.51   34.56   34.58   34.71   35.85
Pier Skew, UpSta & Num, DnSta & Num=  ,4828.6, 2 ,4828.6, 2 , 0 , 0 , 0 ,,
       2       2
   18.47    30.1
       2       2
   18.32   29.95
Pier Skew, UpSta & Num, DnSta & Num=  ,4855.9, 2 ,4855.9, 2 , 0 , 0 , 0 ,,
       2       2
    4.94   30.04
       2       2
    4.79   29.89
Pier Skew, UpSta & Num, DnSta & Num=  ,4882.3, 2 ,4882.3, 2 , 0 , 0 , 0 ,,
       2       2
    -6.6   29.98
       2       2
   -6.75   29.83
Pier Skew, UpSta & Num, DnSta & Num=  ,4909.5, 2 ,4909.5, 2 , 0 , 0 , 0 ,,
       2       2
  -22.13   29.94
       2       2
  -22.28   29.79
Pier Skew, UpSta & Num, DnSta & Num=  ,4938.5, 2 ,4938.5, 2 , 0 , 0 , 0 ,,
       7       7
   -22.3    29.9
       7       7
  -22.45   29.75
Pier Skew, UpSta & Num, DnSta & Num=  ,5058.4, 2 ,5058.4, 2 , 0 , 0 , 0 ,,
      24      24
  -22.87   29.95
      24      24
  -23.02    29.8
Abutment Skew #Up #Dn= , 2 , 2
  4800.2  4828.9
   30.78   19.88
  4800.2  4828.9
   30.63   19.73
Abutment Skew #Up #Dn= , 2 , 2
  5175.8 5179.29
   17.57   28.53
  5175.8 5179.29
   17.42   28.38
BR Coef= 1 , 1 , 0 ,1.25, 0 ,,,.8,0,2,0,
WSPro=,,,, 1 ,,,, 0 ,,,, 0 ,,,,-1 ,-1 ,-1 , 0 , 0 , 0 , 0 , 0
BR U #Sta/Elev= 103
  3873.7    36.5  3903.7    36.6  4121.1   33.42  4163.7    32.8  4213.7    33.7
  4257.5    32.3  4327.5    28.9  4487.5    25.3  4507.5    23.9  4527.5    23.7
    4534    23.3    4554    23.7    4584    22.8    4604    23.1  4663.8   33.12
  4665.5    33.4  4665.6    33.4  4691.9   33.28  4692.5   33.27  4721.2   32.75
  4730.6   32.58  4750.6   32.22  4768.5    31.9  4776.1   31.76  4793.8   31.43
  4800.1   30.81  4800.2    30.8 4800.31   30.79  4800.4   30.78  4806.6   30.17
    4814   25.76  4827.8   21.53  4828.6   21.28  4828.8   20.35  4828.9   19.88
    4841   12.87  4845.9   11.61  4855.4    5.85  4855.9    5.55  4857.9    6.33
  4864.3    1.63  4882.3   -5.06  4882.4   -5.06  4882.7   -5.24  4909.4  -21.13
  4909.5  -21.13  4910.3  -21.13  4937.3  -21.01  4938.2  -21.01 4938.29  -21.01
  4938.4  -21.01  4938.5  -21.01 4938.61  -21.02  4956.1  -22.49  4966.7  -23.39
  4967.1  -23.42  4996.5  -21.19  5025.2  -21.58  5058.3  -22.04  5058.4  -22.04
  5066.2  -20.92  5076.6  -19.42  5094.3  -13.81  5119.3   -5.89  5135.7    1.48
  5145.5   10.76 5149.29   12.39  5149.4   12.44 5149.51   12.49  5158.2   16.24
  5159.2   16.67  5175.7   17.39  5175.8   17.57 5179.09   23.46  5179.2   23.65
  5179.3   23.83  5184.3   32.78  5210.2   33.58  5212.8   33.57  5233.7   33.51
  5243.1   33.52  5264.2   33.53    5273   33.48  5292.1   33.36  5323.9   34.03
  5324.5   34.03  5421.1   34.27  5431.7   34.29  5471.7   34.39  5481.7   34.42
  5511.7   34.49  5521.7   34.51  5581.7   34.66  5601.7   34.71  5611.7   34.73
  5661.7   34.86  5811.7   35.22  5821.7   35.25  5841.7   35.29  6031.7   35.76
  6051.7   35.81  6091.7   35.91  6130.3      36
BR U #Mann= 3
  3873.7      .1  4857.9    .035  5159.2      .1
BR U Banks=4857.9,5159.2
BR D #Sta/Elev= 103
  3873.7   36.35  3903.7   36.45  4121.1   33.27  4163.7   32.65  4213.7   33.55
  4257.5   32.15  4327.5   28.75  4487.5   25.15  4507.5   23.75  4527.5   23.55
    4534   23.15    4554   23.55    4584   22.65    4604   22.95  4663.8   32.97
  4665.5   33.25  4665.6   33.25  4691.9   33.13  4692.5   33.12  4721.2    32.6
  4730.6   32.43  4750.6   32.07  4768.5   31.75  4776.1   31.61  4793.8   31.28
  4800.1   30.66  4800.2   30.65 4800.31   30.64  4800.4   30.63  4806.6   30.02
    4814   25.61  4827.8   21.38  4828.6   21.13  4828.8    20.2  4828.9   19.73
    4841   12.72  4845.9   11.46  4855.4     5.7  4855.9     5.4  4857.9    6.18
  4864.3    1.48  4882.3   -5.21  4882.4   -5.21  4882.7   -5.39  4909.4  -21.28
  4909.5  -21.28  4910.3  -21.28  4937.3  -21.16  4938.2  -21.16 4938.29  -21.16
  4938.4  -21.16  4938.5  -21.16 4938.61  -21.17  4956.1  -22.64  4966.7  -23.54
  4967.1  -23.57  4996.5  -21.34  5025.2  -21.73  5058.3  -22.19  5058.4  -22.19
  5066.2  -21.07  5076.6  -19.57  5094.3  -13.96  5119.3   -6.04  5135.7    1.33
  5145.5   10.61 5149.29   12.24  5149.4   12.29 5149.51   12.34  5158.2   16.09
  5159.2   16.52  5175.7   17.24  5175.8   17.42 5179.09   23.31  5179.2    23.5
  5179.3   23.68  5184.3   32.63  5210.2   33.43  5212.8   33.42  5233.7   33.36
  5243.1   33.37  5264.2   33.38    5273   33.33  5292.1   33.21  5323.9   33.88
  5324.5   33.88  5421.1   34.12  5431.7   34.14  5471.7   34.24  5481.7   34.27
  5511.7   34.34  5521.7   34.36  5581.7   34.51  5601.7   34.56  5611.7   34.58
  5661.7   34.71  5811.7   35.07  5821.7    35.1  5841.7   35.14  6031.7   35.61
  6051.7   35.66  6091.7   35.76  6130.3   35.85
BR D #Mann= 3
  3873.7      .1  4857.9    .035  5159.2      .1
BR D Banks=4857.9,5159.2
BC Design=,, 0 ,, 0 ,,,,,,
BC HTab HWMax=36.6

Type RM Length L Ch R = 1 ,86623.2 ,768,768,768
BEGIN DESCRIPTION:
Downstream Section of Bridge/Culvert/Weir
END DESCRIPTION:
XS GIS Cut Line= 6
       3141937.8     13841151.72      3141716.99     13840789.55
      3141591.97     13840560.95       3141295.5     13840000.15
      3141191.91     13839807.27      3140831.15     13839185.76
#Sta/Elev= 30
  3873.7   36.31  4163.7   32.61  4213.7   33.51  4327.5   28.71    4584   22.61
    4604   22.91  4665.5   33.21  4793.8   31.24  4806.6   29.98    4814   25.57
  4828.6   21.09    4841   12.68  4855.9    5.36  4857.9    6.14  4864.3    1.44
  4882.4   -5.25  4909.4  -21.32  4938.5   -21.2  4967.1  -23.61  4996.5  -21.38
  5058.4  -22.23  5076.6  -19.61  5119.3   -6.08  5135.7    1.29  5145.5   10.57
  5159.2   16.48  5175.7    17.2  5184.3   32.59  5210.2   33.39  6130.3   35.81
#Mann= 3 ,-1 , 0
  3873.7      .1       0  4857.9    .035       0  5159.2      .1       0
#XS Ineff= 2 , 0
            4795    35.2    5190            34.5
Permanent Ineff=
       F       F
Bank Sta=4857.9,5159.2
XS Rating Curve= 0
Exp/Cntr=.5,.3

Type RM Length L Ch R = 1 ,85855.2 ,441.5,616.5,741.4
BEGIN DESCRIPTION:
Cross Section 85855.2-Interpolated
END DESCRIPTION:
XS GIS Cut Line= 5
      3141925.25     13840797.65      3142089.37     13839977.07
      3141974.48     13839594.13      3141624.37     13839183.84
      3141389.14     13838872.02
#Sta/Elev= 30
  3986.8   36.64  4116.8      36  4216.8   33.57  4246.8   31.23  4276.8   32.23
  4366.8   32.05  4586.8   30.01  4656.8    27.8  4686.8    25.9  4786.8   24.23
  4843.6   20.61  4883.6   15.52  4890.1   13.83  4899.7    4.38  4914.5   -8.61
  4954.9  -26.84  4994.6  -25.95  5039.9  -17.81  5073.4   -9.02  5113.6   12.02
  5143.6   10.94  5163.6   18.91  5183.6   23.02  5293.4   21.36  5363.4   25.64
  5633.4    30.8  5762.8   32.17  5842.8   31.47  5882.8   33.24  6153.4   34.89
#Mann= 3 ,-1 , 0
  3986.8      .1       0  4890.1    .035       0  5113.6      .1       0
Bank Sta=4890.1,5113.6
XS Rating Curve= 0
Exp/Cntr=.3,.1

Type RM Length L Ch R = 1 ,85238.7 ,1075.4,677,562.6
BEGIN DESCRIPTION:
Cross Section 85238.7-Interpolated
END DESCRIPTION:
XS GIS Cut Line= 2
      3142119.94     13840625.65      3142689.74     13839903.82
#Sta/Elev= 24
  4267.6    32.1  4327.6    30.4  4507.6    29.1  4537.6    26.8  4617.6      26
  4707.6    22.7  4717.6      22  4727.6    20.3  4737.6    18.1  4767.6       9
  4787.6     6.6  4807.6     6.1  4837.6     3.9  4890.1   11.24  4899.7    1.79
  4914.5   -11.2  4954.9  -29.43  4994.6  -28.54  5039.9   -20.4  5073.4  -11.61
  5100.3    2.14  5113.6    9.43  5127.6    17.6  5187.2    36.8
#Mann= 5 ,-1 , 0
  4267.6      .2       0  4267.6      .1       0  4890.1    .035       0
  5113.6      .1       0  5187.2      .2       0
Bank Sta=4890.1,5113.6
XS Rating Curve= 0
Exp/Cntr=.5,.3

Type RM Length L Ch R = 1 ,84561.7 ,60.6,60.6,60.6
BEGIN DESCRIPTION:
Upstream Section of Bridge/Culvert/Weir
END DESCRIPTION:
XS GIS Cut Line= 6
      3144025.91     13841637.17      3143725.78     13840898.19
      3143419.73     13840532.29      3142961.52     13840132.93
      3142800.82     13839829.27      3141572.77     13839026.61
#Sta/Elev= 30
  3379.5   39.34  3429.5   25.04  3699.5   22.24  3809.5   26.44  3849.5   38.74
  4107.2   38.04  4365.2   29.54  4551.7   31.91  4676.3   23.43  4748.4      26
  4890.1     8.4  4914.5  -14.04  4954.9  -32.27  5039.9  -23.24  5073.4  -14.45
  5113.6    6.59  5144.4    8.84    5201   31.97  5244.3   35.76  5261.8   43.85
  5279.6   33.61    5359   12.21    5386    9.52    5406   14.47  5445.8    5.74
  5494.7    4.45  5528.2    7.42  5604.9   36.91    5929   22.64  7074.1   33.84
#Mann= 3 ,-1 , 0
  3379.5      .1       0  4890.1    .035       0  5113.6      .1       0
#XS Ineff= 2 , 0
            4605   32.65  5575.5            25.6
Permanent Ineff=
       F       F
Bank Sta=4890.1,5113.6
XS Rating Curve= 0
Exp/Cntr=.5,.3