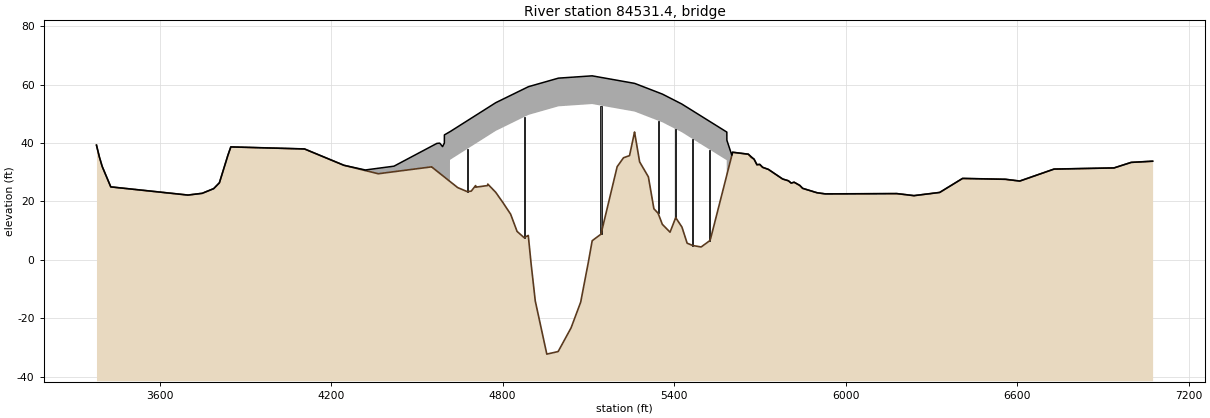
HEC-RAS study W100-00-00.prj: W100-00-00

--- W100-00-00.g01 (geometry) --- (continued)

Type RM Length L Ch R = 3 ,84531.4 ,,,
BEGIN DESCRIPTION:
NORTH WAYSIDE ROAD
Structure ID: WOO-5
END DESCRIPTION:
Bridge Culvert--1,0,-1,-1, 0
Deck Dist Width WeirC Skew NumUp NumDn MinLoCord MaxHiCord MaxSubmerge Is_Ogee
10,40.6,2.6,0, 60, 60, , , .95, 0, 1,1,,
  3379.5  3389.5  3399.5  3429.5  3699.5  3749.5  3789.5  3809.5  3839.5  3849.5
  4107.2  4245.2  4320.2  4365.2  4420.2  4551.7  4570.2  4580.2  4590.2 4596.49
  4596.6 4616.11  4616.2  4776.3  4890.6  4995.5  5113.5  5262.3  5359.5    5427
 5584.19  5584.3  5584.7 5584.81  5602.2  5604.9  5659.9  5679.9  5689.9  5699.9
  5709.9  5729.9  5779.9  5799.9  5809.9  5819.9  5839.9  5849.9  5899.9    5929
  6179.3  6239.3  6329.3  6409.3  6559.3  6609.3  6729.3  6939.3  6999.3  7074.1
    39.3    35.3      32      25    22.2    22.8    24.4    26.4    35.9    38.7
      38    32.4    30.8   31.39    32.1   38.94    39.9      40    38.8   40.02
   42.82   43.92   43.92   53.86   59.34   62.27   63.06   60.47   56.79   53.41
   43.81    43.8   43.79   40.99   35.84   36.87    36.2    34.5    32.6    32.7
    31.7      31    27.7    27.1    26.3    26.6    25.5    24.5      23    22.6
    22.7      22    23.1    27.9    27.6      27    31.1    31.5    33.4    33.8
    39.3    35.3      32      25    22.2    22.8    24.4    26.4    35.9    38.7
      38    32.4   30.59    29.5    30.2   31.87   30.43   29.65   28.88   28.39
   28.38   26.86   34.25   44.19   49.67    52.6   53.39    50.8   47.12   43.74
   34.14   28.95    29.1   29.15   35.83   36.87    36.2    34.5    32.6    32.7
    31.7      31    27.7    27.1    26.3    26.6    25.5    24.5      23    22.6
    22.7      22    23.1    27.9    27.6      27    31.1    31.5    33.4    33.8
  3379.5  3389.5  3399.5  3429.5  3699.5  3749.5  3789.5  3809.5  3839.5  3849.5
  4107.2  4245.2  4365.2  4420.2  4551.7  4570.2  4580.2  4590.2 4596.49  4596.6
 4616.11  4616.2  4776.3  4890.6  4995.5  5113.5  5262.3  5359.5    5427 5584.19
  5584.3  5584.7 5584.81  5602.2  5604.9  5659.9  5669.9  5679.9  5689.9  5699.9
  5709.9  5729.9  5779.9  5799.9  5809.9  5819.9  5839.9  5849.9  5899.9    5929
  6179.3  6239.3  6329.3  6409.3  6559.3  6609.3  6729.3  6939.3  6999.3  7074.1
   42.56   38.56   35.26   28.26   25.46   26.06   27.66   29.66   39.16   41.96
   41.26   35.66   32.76   33.46   38.94    39.9      40    38.8   40.02   42.82
   43.92   43.92   53.86   59.34   62.27   63.06   60.47   56.79   53.41   43.81
    43.8   43.79   40.99   39.09   40.13   39.46   38.36   37.76   35.86   35.96
   34.96   34.26   30.96   30.36   29.56   29.86   28.76   27.76   26.26   25.86
   25.96   25.26   26.36   31.16   30.86   30.26   34.36   34.76   36.66   37.06
   42.56   38.56   35.26   28.26   25.46   26.06   27.66   29.66   39.16   41.96
   41.26   35.66   32.76   33.46   35.13   33.69   32.91   32.14   31.65   31.64
   30.12   37.51   47.45   52.93   55.86   56.65   54.06   50.38      47    37.4
   32.21   32.36   32.41   39.09   40.13   39.46   38.36   37.76   35.86   35.96
   34.96   34.26   30.96   30.36   29.56   29.86   28.76   27.76   26.26   25.86
   25.96   25.26   26.36   31.16   30.86   30.26   34.36   34.76   36.66   37.06
Pier Skew, UpSta & Num, DnSta & Num=  ,4676.3, 2 ,4676.3, 2 , 0 , 0 , 0 ,,
       4       4
   22.41   39.13
       4       4
   25.67   42.39
Pier Skew, UpSta & Num, DnSta & Num=  ,4875.5, 2 ,4875.5, 2 , 0 , 0 , 0 ,,
       4       4
    6.71   50.05
       4       4
    9.97   53.31
Pier Skew, UpSta & Num, DnSta & Num=  ,5144.4, 2 ,5144.4, 2 , 0 , 0 , 0 ,,
       4       4
    7.65   53.89
       4       4
   10.91   57.15
Pier Skew, UpSta & Num, DnSta & Num=  ,5344.2, 2 ,5344.2, 2 , 0 , 0 , 0 ,,
       4       4
   14.46   48.78
       4       4
   17.72   52.04
Pier Skew, UpSta & Num, DnSta & Num=  ,5406, 2 ,5406, 2 , 0 , 0 , 0 ,,
       4       4
   13.02   45.89
       4       4
   16.28   49.15
Pier Skew, UpSta & Num, DnSta & Num=  ,5465.6, 2 ,5465.6, 2 , 0 , 0 , 0 ,,
       4       4
    3.88    42.5
       4       4
    7.14   45.76
Pier Skew, UpSta & Num, DnSta & Num=  ,5524.9, 2 ,5524.9, 2 , 0 , 0 , 0 ,,
       4       4
    5.43   38.88
       4       4
    8.69   42.14
Abutment Skew #Up #Dn= , 2 , 2
    4616  4643.1
   34.25   24.76
    4616  4643.1
   37.51   28.02
Abutment Skew #Up #Dn= , 2 , 2
  5528.3 5584.39
    7.42   34.14
  5528.3 5584.39
   10.68    37.4
BR Coef= 1 , 1 , 0 ,1.25, 0 ,,,.8,0,2,0,
WSPro=,,,, 1 ,,,, 0 ,,,, 0 ,,,,-1 ,-1 ,-1 , 0 , 0 , 0 , 0 , 0
BR U #Sta/Elev= 111
  3379.5    39.3  3389.5    35.3  3399.5      32  3429.5      25  3699.5    22.2
  3749.5    22.8  3789.5    24.4  3809.5    26.4  3839.5    35.9  3849.5    38.7
  4107.2      38  4245.2    32.4  4320.2   30.59  4365.2    29.5  4420.2    30.2
  4551.6   31.86  4551.7   31.87  4570.2   30.43  4580.2   29.65  4590.2   28.88
 4596.49   28.39  4596.6   28.38 4596.71   28.37  4596.8   28.36    4616   26.87
 4616.11   26.86  4616.2   26.85    4643   24.77  4643.1   24.76  4676.3   23.39
  4676.4   23.39  4690.4   23.54  4705.9   25.45  4706.9   24.91  4747.8   25.46
  4748.4   25.96  4776.3   23.13  4776.7   23.07  4801.7   19.58  4828.2   15.67
  4850.9    9.74  4875.5    7.61  4890.1    8.36  4890.6    7.87  4899.7   -1.09
  4914.5  -14.08  4954.9  -32.31  4994.6  -31.42  4995.5  -31.26  5039.9  -23.28
  5073.4  -14.49  5100.3    -.74  5113.5     6.5  5113.6    6.55  5144.4     8.8
    5201   31.93  5223.2   34.98  5244.3   35.72  5261.8   43.81  5262.3   43.52
  5279.6   33.57  5310.2   28.44  5329.5   17.51  5344.2   15.97    5359   12.17
  5359.5   12.12    5386    9.48  5405.6   14.42    5406   14.43    5427   11.33
  5427.6   11.24  5445.8     5.7  5465.6    4.91  5494.7    4.41  5524.9    6.57
  5528.2    7.38  5528.3    7.42 5584.19   28.91  5584.3   28.95  5584.4   28.99
  5584.5   29.03 5584.59   29.06  5584.7    29.1 5584.81   29.15  5602.2   35.83
  5604.9   36.87  5659.9    36.2  5669.9    35.1  5679.9    34.5  5689.9    32.6
  5699.9    32.7  5709.9    31.7  5729.9      31  5779.9    27.7  5799.9    27.1
  5809.9    26.3  5819.9    26.6  5839.9    25.5  5849.9    24.5  5899.9      23
    5929    22.6  6179.3    22.7  6239.3      22  6329.3    23.1  6409.3    27.9
  6559.3    27.6  6609.3      27  6729.3    31.1  6939.3    31.5  6999.3    33.4
  7074.1    33.8
BR U #Mann= 3
  3379.5      .1  4890.1    .035  5113.6      .1
BR U Banks=4890.1,5113.6
BR D #Sta/Elev= 111
  3379.5   42.56  3389.5   38.56  3399.5   35.26  3429.5   28.26  3699.5   25.46
  3749.5   26.06  3789.5   27.66  3809.5   29.66  3839.5   39.16  3849.5   41.96
  4107.2   41.26  4245.2   35.66  4320.2   33.85  4365.2   32.76  4420.2   33.46
  4551.6   35.12  4551.7   35.13  4570.2   33.69  4580.2   32.91  4590.2   32.14
 4596.49   31.65  4596.6   31.64 4596.71   31.63  4596.8   31.62    4616   30.13
 4616.11   30.12  4616.2   30.11    4643   28.03  4643.1   28.02  4676.3   26.65
  4676.4   26.65  4690.4    26.8  4705.9   28.71  4706.9   28.17  4747.8   28.72
  4748.4   29.22  4776.3   26.39  4776.7   26.33  4801.7   22.84  4828.2   18.93
  4850.9      13  4875.5   10.87  4890.1   11.62  4890.6   11.13  4899.7    2.17
  4914.5  -10.82  4954.9  -29.05  4994.6  -28.16  4995.5     -28  5039.9  -20.02
  5073.4  -11.23  5100.3    2.52  5113.5    9.76  5113.6    9.81  5144.4   12.06
    5201   35.19  5223.2   38.24  5244.3   38.98  5261.8   47.07  5262.3   46.78
  5279.6   36.83  5310.2    31.7  5329.5   20.77  5344.2   19.23    5359   15.43
  5359.5   15.38    5386   12.74  5405.6   17.68    5406   17.69    5427   14.59
  5427.6    14.5  5445.8    8.96  5465.6    8.17  5494.7    7.67  5524.9    9.83
  5528.2   10.64  5528.3   10.68 5584.19   32.17  5584.3   32.21  5584.4   32.25
  5584.5   32.29 5584.59   32.32  5584.7   32.36 5584.81   32.41  5602.2   39.09
  5604.9   40.13  5659.9   39.46  5669.9   38.36  5679.9   37.76  5689.9   35.86
  5699.9   35.96  5709.9   34.96  5729.9   34.26  5779.9   30.96  5799.9   30.36
  5809.9   29.56  5819.9   29.86  5839.9   28.76  5849.9   27.76  5899.9   26.26
    5929   25.86  6179.3   25.96  6239.3   25.26  6329.3   26.36  6409.3   31.16
  6559.3   30.86  6609.3   30.26  6729.3   34.36  6939.3   34.76  6999.3   36.66
  7074.1   37.06
BR D #Mann= 3
  3379.5      .1  4890.1    .035  5113.6      .1
BR D Banks=4890.1,5113.6
BC Design=,, 0 ,, 0 ,,,,,,
BC HTab HWMax=43.85