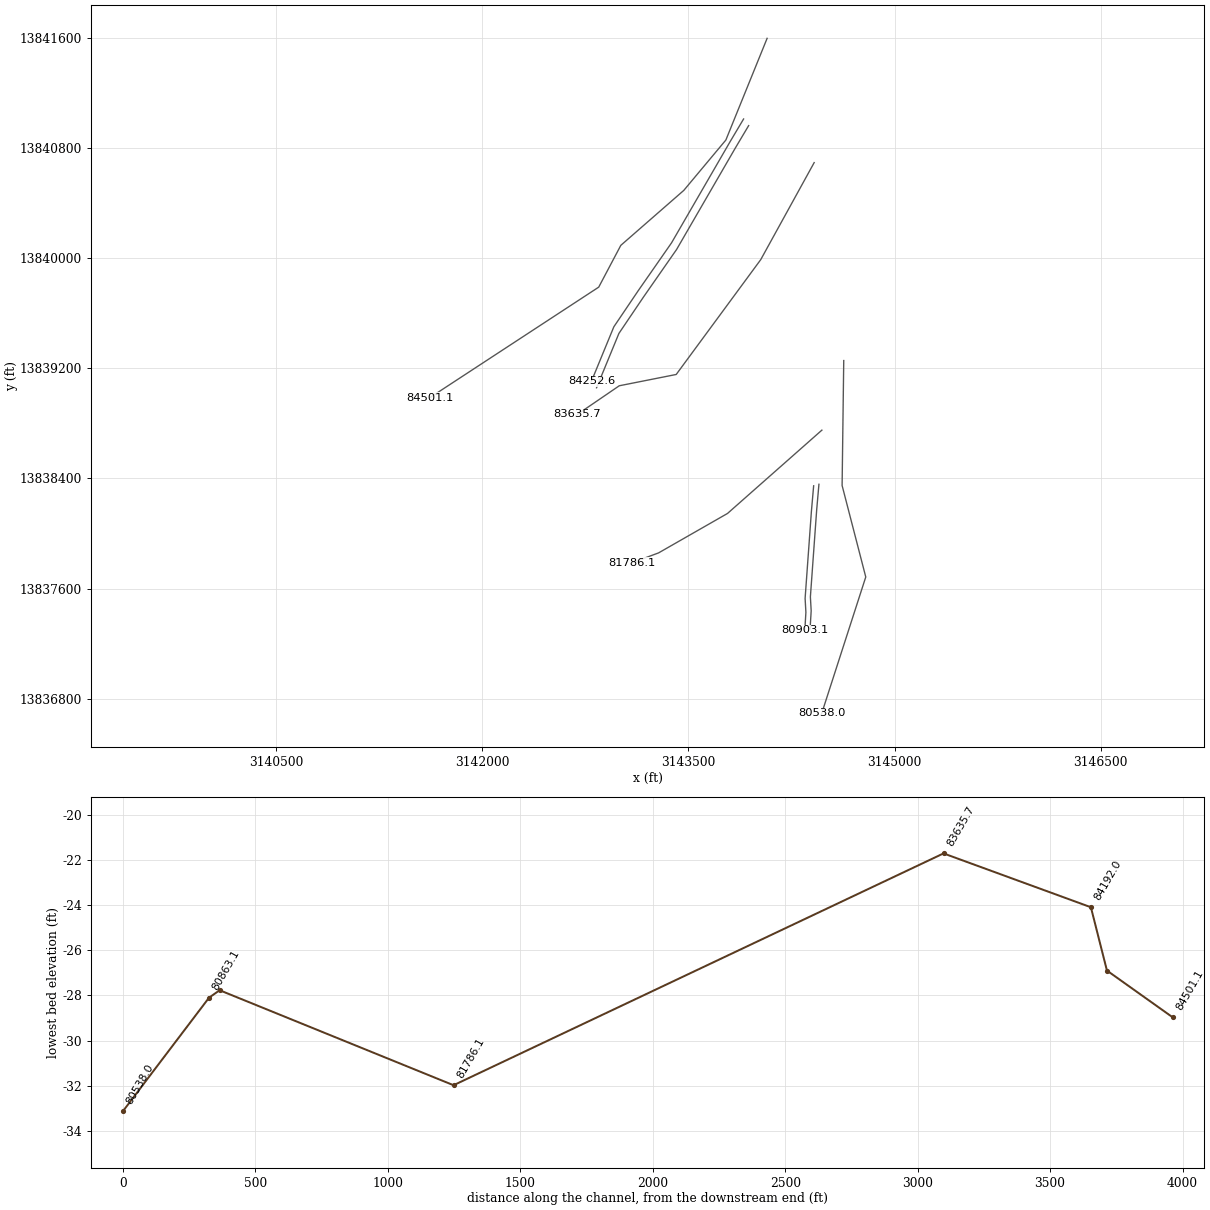
HEC-RAS study W100-00-00.prj: W100-00-00

--- W100-00-00.g01 (geometry) --- (continued)

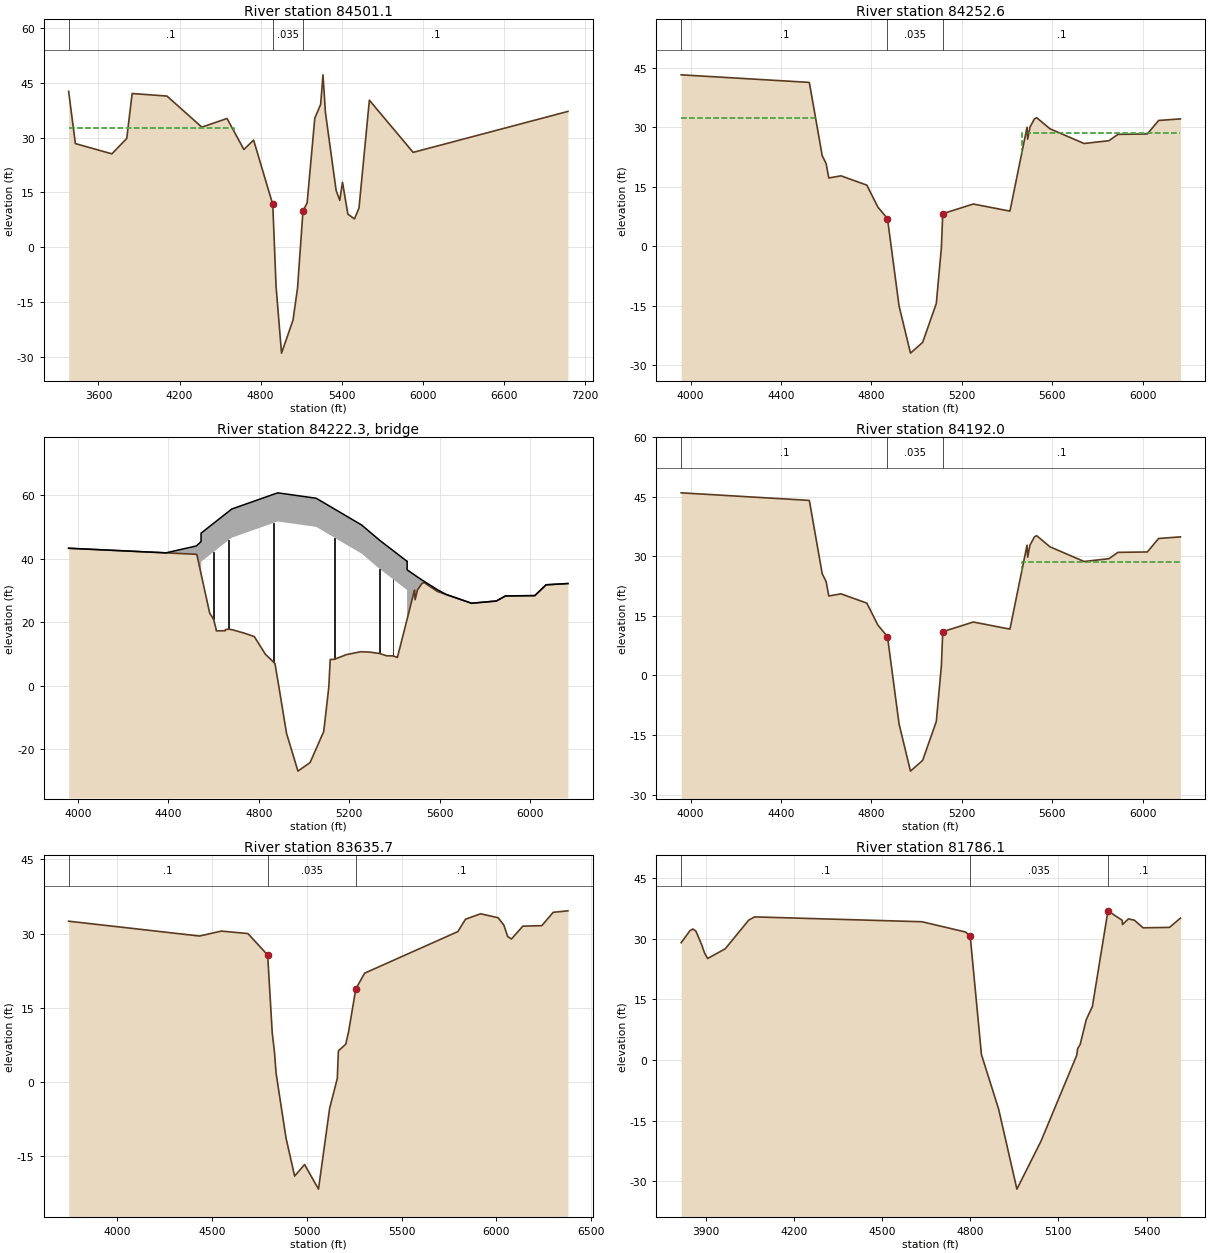
Type RM Length L Ch R = 1 ,84501.1 ,248.5,248.5,248.5
BEGIN DESCRIPTION:
Downstream Section of Bridge/Culvert/Weir
END DESCRIPTION:
XS GIS Cut Line= 6
      3144071.97     13841597.79      3143771.84     13840858.81
      3143465.79     13840492.91      3143007.58     13840093.55
      3142846.88     13839789.89      3141618.83     13838987.23
#Sta/Elev= 30
  3379.5   42.64  3429.5   28.34  3699.5   25.54  3809.5   29.74  3849.5   42.04
  4107.2   41.34  4365.2   32.84  4551.7   35.21  4676.3   26.73  4748.4    29.3
  4890.1    11.7  4914.5  -10.74  4954.9  -28.97  5039.9  -19.94  5073.4  -11.15
  5113.6    9.89  5144.4   12.14    5201   35.27  5244.3   39.06  5261.8   47.15
  5279.6   36.91    5359   15.51    5386   12.82    5406   17.77  5445.8    9.04
  5494.7    7.75  5528.2   10.72  5604.9   40.21    5929   25.94  7074.1   37.14
#Mann= 3 ,-1 , 0
  3379.5      .1       0  4890.1    .035       0  5113.6      .1       0
#XS Ineff= 2 , 0
            4605   32.65  5575.5            25.6
Permanent Ineff=
       F       F
Bank Sta=4890.1,5113.6
XS Rating Curve= 0
Exp/Cntr=.5,.3

Type RM Length L Ch R = 1 ,84252.6 ,60.6,60.6,60.6
BEGIN DESCRIPTION:
Upstream Section of Bridge/Culvert/Weir
END DESCRIPTION:
XS GIS Cut Line= 6
      3143900.76     13841011.66      3143802.97     13840847.42
      3143376.71     13840111.87      3143135.02     13839765.13
      3142956.88     13839501.67      3142794.26     13839106.74
#Sta/Elev= 30
  3958.7   43.22  4523.6   41.32  4526.1    41.2  4582.8   22.83  4600.1   20.87
  4611.9   17.23  4665.7   17.77  4780.2   15.43    4829    9.91  4871.6    6.98
  4922.8  -15.01  4973.3   -26.9  5027.1   -24.2  5087.5  -14.41    5110    -.34
  5116.1    8.23  5251.3   10.67  5413.4    8.88    5489   30.02  5491.8   27.02
  5501.8   30.02  5521.8   32.12  5531.8   32.42  5590.6   29.62  5741.3   25.92
  5851.3   26.62  5891.3   28.22  6021.3   28.32  6071.3   31.72  6167.8   32.12
#Mann= 3 ,-1 , 0
  3958.7      .1       0  4871.6    .035       0  5116.1      .1       0
#XS Ineff= 2 , 0
          4553.5    32.4    5465            28.5
Permanent Ineff=
       F       F
Bank Sta=4871.6,5116.1
XS Rating Curve= 0
Exp/Cntr=.5,.3

Type RM Length L Ch R = 3 ,84222.3 ,,,
BEGIN DESCRIPTION:
STAFF SGT M. GARCIA
Structure ID: W00-4
END DESCRIPTION:
Bridge Culvert--1,0,-1,-1, 0
Deck Dist Width WeirC Skew NumUp NumDn MinLoCord MaxHiCord MaxSubmerge Is_Ogee
10,40.6,2.6,0, 31, 30, , , .95, 0, 1,1,,
  3958.7  4389.4  4523.6  4526.1 4544.59  4544.7 4545.21  4545.3  4680.3  4883.7
  5053.9  5254.9  5333.3 5455.99  5456.1  5456.4 5456.51    5489  5489.1  5491.8
  5501.8  5521.8  5531.8  5590.6  5629.6  5741.3  5851.3  5891.3  6021.3  6071.3
  6167.8
    43.3   41.86   44.03   44.19   45.38   48.08   48.08   48.08   55.64   60.74
   59.04   50.63    45.9   39.19   39.18    39.2    36.5   34.92   34.91   34.78
   34.28   33.33   32.88   30.25   28.75      26    26.7    28.3    28.4    31.8
    32.2
    43.3   41.85    41.4   41.28   35.29   35.25   35.09   39.07   46.63   51.73
   50.03   41.62   36.89   30.18    20.9   20.98   21.01    30.1    30.1    27.1
    30.1    32.2    32.5    29.7   28.74      26    26.7    28.3    28.4    31.8
    32.2
  3958.7  4523.6  4526.1 4544.59  4544.7 4545.21  4545.3  4680.3  4883.7  5053.9
  5254.9  5333.3 5455.99  5456.1  5456.4 5456.51    5489  5489.1  5491.8  5501.8
  5513.3  5521.8  5531.8  5590.6  5741.3  5851.3  5891.3  6021.3  6071.3  6167.8
   45.98   44.08   44.19   45.38   48.08   48.08   48.08   55.64   60.74   59.04
   50.63    45.9   39.19   39.18    39.2    36.5   34.92   34.91   34.78   34.28
   33.99   34.88   35.18   32.38   28.68   29.38   30.98   31.08   34.48   34.88
   45.98   44.08   43.96   37.97   37.93   37.77   41.75   49.31   54.41   52.71
    44.3   39.57   32.86   23.58   23.66   23.69   32.78   32.78   29.78   32.78
   33.99   34.88   35.18   32.38   28.68   29.38   30.98   31.08   34.48   34.88
Pier Skew, UpSta & Num, DnSta & Num=  ,4600.1, 2 ,4600.1, 2 , 0 , 0 , 0 ,,
       4       4
   19.39   43.25
       4       4
   22.07   45.93
Pier Skew, UpSta & Num, DnSta & Num=  ,4665.6, 2 ,4665.6, 2 , 0 , 0 , 0 ,,
       4       4
   16.82   46.92
       4       4
    19.5    49.6
Pier Skew, UpSta & Num, DnSta & Num=  ,4864.3, 2 ,4864.3, 2 , 0 , 0 , 0 ,,
       4       4
    6.43    52.3
       4       4
    9.11   54.98
Pier Skew, UpSta & Num, DnSta & Num=  ,5134.2, 2 ,5134.2, 2 , 0 , 0 , 0 ,,
       4       4
    7.35   47.76
       4       4
   10.03   50.44
Pier Skew, UpSta & Num, DnSta & Num=  ,5333.2, 2 ,5333.2, 2 , 0 , 0 , 0 ,,
       4       4
    9.17   38.02
       4       4
   11.85    40.7
Pier Skew, UpSta & Num, DnSta & Num=  ,5394, 2 ,5394, 2 , 0 , 0 , 0 ,,
       4       4
    8.39   34.68
       4       4
   11.07   37.36
Abutment Skew #Up #Dn= , 2 , 2
  4545.1  4582.7
   39.07   22.94
  4545.1  4582.7
   41.75   25.62
Abutment Skew #Up #Dn= , 2 , 2
  5413.3 5456.19
    8.96   30.18
  5413.3 5456.19
   11.64   32.86
BR Coef= 1 , 1 , 0 ,1.25, 0 ,,,.8,0,2,0,
WSPro=,,,, 1 ,,,, 0 ,,,, 0 ,,,,-1 ,-1 ,-1 , 0 , 0 , 0 , 0 , 0
BR U #Sta/Elev= 74
  3958.7    43.3  4098.7   42.83  4148.7   42.66    4151   42.65    4231   42.38
    4341   42.01  4389.4   41.85  4523.6    41.4  4526.1   41.28 4544.59   35.29
  4544.7   35.25 4544.81   35.22 4545.21   35.09  4545.3   35.06  4545.4   35.03
  4545.5   34.99  4582.7   22.94  4582.8   22.91  4600.1   20.95  4611.3   17.83
  4611.9   17.31  4651.5   17.35  4652.5   17.69  4665.7   17.85  4680.3   17.69
  4683.2   17.66  4736.1   16.59  4780.2   15.51    4829    9.99  4864.4    7.56
  4871.6    7.06  4883.7    1.96  4890.1    -.74  4922.8  -14.93  4973.3  -26.82
  5027.1  -24.12  5053.9  -19.78  5087.5  -14.33    5110    -.26  5116.1    8.31
  5134.3    8.36  5188.1    9.84  5251.3   10.75  5254.9   10.74  5290.7   10.63
  5333.2   10.21  5333.3   10.21  5366.4    9.46  5394.1    9.44  5413.3    8.96
  5413.4    8.96 5455.99   20.87  5456.1    20.9  5456.2   20.93 5456.29   20.95
  5456.4   20.98 5456.51   21.01  5456.8    21.1    5489    30.1  5489.1    30.1
  5491.8    27.1  5501.8    30.1  5513.3   31.31  5513.5   31.33  5521.8    32.2
  5531.8    32.5  5590.6    29.7  5629.6   28.74  5741.3      26  5851.3    26.7
  5891.3    28.3  6021.3    28.4  6071.3    31.8  6167.8    32.2
BR U #Mann= 3
  3958.7      .1  4871.6    .035  5116.1      .1
BR U Banks=4871.6,5116.1
BR D #Sta/Elev= 74
  3958.7   45.98  4098.7   45.51  4148.7   45.34    4151   45.33    4231   45.06
    4341   44.69  4389.4   44.53  4523.6   44.08  4526.1   43.96 4544.59   37.97
  4544.7   37.93 4544.81    37.9 4545.21   37.77  4545.3   37.74  4545.4   37.71
  4545.5   37.67  4582.7   25.62  4582.8   25.59  4600.1   23.63  4611.3   20.51
  4611.9   19.99  4651.5   20.03  4652.5   20.37  4665.7   20.53  4680.3   20.37
  4683.2   20.34  4736.1   19.27  4780.2   18.19    4829   12.67  4864.4   10.24
  4871.6    9.74  4883.7    4.64  4890.1    1.94  4922.8  -12.25  4973.3  -24.14
  5027.1  -21.44  5053.9   -17.1  5087.5  -11.65    5110    2.42  5116.1   10.99
  5134.3   11.04  5188.1   12.52  5251.3   13.43  5254.9   13.42  5290.7   13.31
  5333.2   12.89  5333.3   12.89  5366.4   12.14  5394.1   12.12  5413.3   11.64
  5413.4   11.64 5455.99   23.55  5456.1   23.58  5456.2   23.61 5456.29   23.63
  5456.4   23.66 5456.51   23.69  5456.8   23.78    5489   32.78  5489.1   32.78
  5491.8   29.78  5501.8   32.78  5513.3   33.99  5513.5   34.01  5521.8   34.88
  5531.8   35.18  5590.6   32.38  5629.6   31.42  5741.3   28.68  5851.3   29.38
  5891.3   30.98  6021.3   31.08  6071.3   34.48  6167.8   34.88
BR D #Mann= 3
  3958.7      .1  4871.6    .035  5116.1      .1
BR D Banks=4871.6,5116.1
BC Design=,, 0 ,, 0 ,,,,,,
BC HTab HWMax=43.22

Type RM Length L Ch R = 1 ,84192.0 ,556.3,556.3,556.3
BEGIN DESCRIPTION:
Downstream Section of Bridge/Culvert/Weir
END DESCRIPTION:
XS GIS Cut Line= 6
       3143937.6     13840963.55      3143839.81      13840799.3
      3143413.55     13840063.75      3143171.86     13839717.01
      3142993.72     13839453.55      3142831.11     13839058.62
#Sta/Elev= 30
  3958.7   46.02  4523.6   44.12  4526.1      44  4582.8   25.63  4600.1   23.67
  4611.9   20.03  4665.7   20.57  4780.2   18.23    4829   12.71  4871.6    9.78
  4922.8  -12.21  4973.3   -24.1  5027.1   -21.4  5087.5  -11.61    5110    2.46
  5116.1   11.03  5251.3   13.47  5413.4   11.68    5489   32.82  5491.8   29.82
  5501.8   32.82  5521.8   34.92  5531.8   35.22  5590.6   32.42  5741.3   28.72
  5851.3   29.42  5891.3   31.02  6021.3   31.12  6071.3   34.52  6167.8   34.92
#Mann= 3 ,-1 , 0
  3958.7      .1       0  4871.6    .035       0  5116.1      .1       0
#XS Ineff= 2 , 0
          4553.5    32.4    5465            28.5
Permanent Ineff=
       F       F
Bank Sta=4871.6,5116.1
XS Rating Curve= 0
Exp/Cntr=.5,.3

Type RM Length L Ch R = 1 ,83635.7 ,1823.5,1849.6,1764.4
BEGIN DESCRIPTION:
Cross Section 83635.7
END DESCRIPTION:
XS GIS Cut Line= 5
      3144414.32     13840694.77      3144025.54     13839989.68
      3143410.61     13839155.27      3142996.27     13839073.12
      3142692.66     13838865.95
#Sta/Elev= 30
  3745.2    32.5  4435.2    29.5  4550.4    30.5  4690.4      30  4794.3   25.65
  4818.5    9.85  4830.3       6  4838.4    1.82  4890.8  -11.33  4936.5  -19.08
  4988.9  -16.74  5062.2  -21.72  5120.9   -5.38  5161.5     .71  5167.1    6.26
  5206.2    7.62  5221.3   10.22  5258.9   18.81  5305.7   21.99  5796.9    30.4
  5836.9    32.9  5916.9      34  6009.3    33.2  6039.3    31.7  6059.3    29.4
  6079.3    28.9  6139.3    31.5  6239.3    31.6  6299.3    34.3  6376.9    34.6
#Mann= 3 ,-1 , 0
  3745.2      .1       0  4794.3    .035       0  5258.9      .1       0
Bank Sta=4794.3,5258.9
XS Rating Curve= 0
Exp/Cntr=.3,.1

Type RM Length L Ch R = 1 ,81786.1 ,672.1,883,1044.3
BEGIN DESCRIPTION:
Cross Section 81786.1
END DESCRIPTION:
XS GIS Cut Line= 4
      3144470.42     13838750.76       3143783.8     13838145.33
      3143282.42     13837858.82      3143088.08      13837786.7
#Sta/Elev= 30
  3815.3      29  3845.3      32  3855.3    32.4  3865.3    31.9  3885.3    28.5
  3895.3    26.4  3905.3    25.1  3965.3    27.5  4045.3    34.6  4065.3    35.4
  4635.3    34.2    4784   31.65  4799.7   30.55  4837.8    1.34  4896.4  -12.18
  4958.6  -31.97  5040.8  -20.07  5162.2    1.14  5165.6    2.84    5174    3.83
  5194.9   10.01  5215.6   13.22  5268.7    36.9  5317.1   34.55  5318.2    33.5
  5338.2    34.9  5358.2    34.6  5388.2    32.7  5478.2    32.8  5515.5    35.1
#Mann= 3 ,-1 , 0
  3815.3      .1       0  4799.7    .035       0  5268.7      .1       0
Bank Sta=4799.7,5268.7
XS Rating Curve= 0
Exp/Cntr=.5,.3

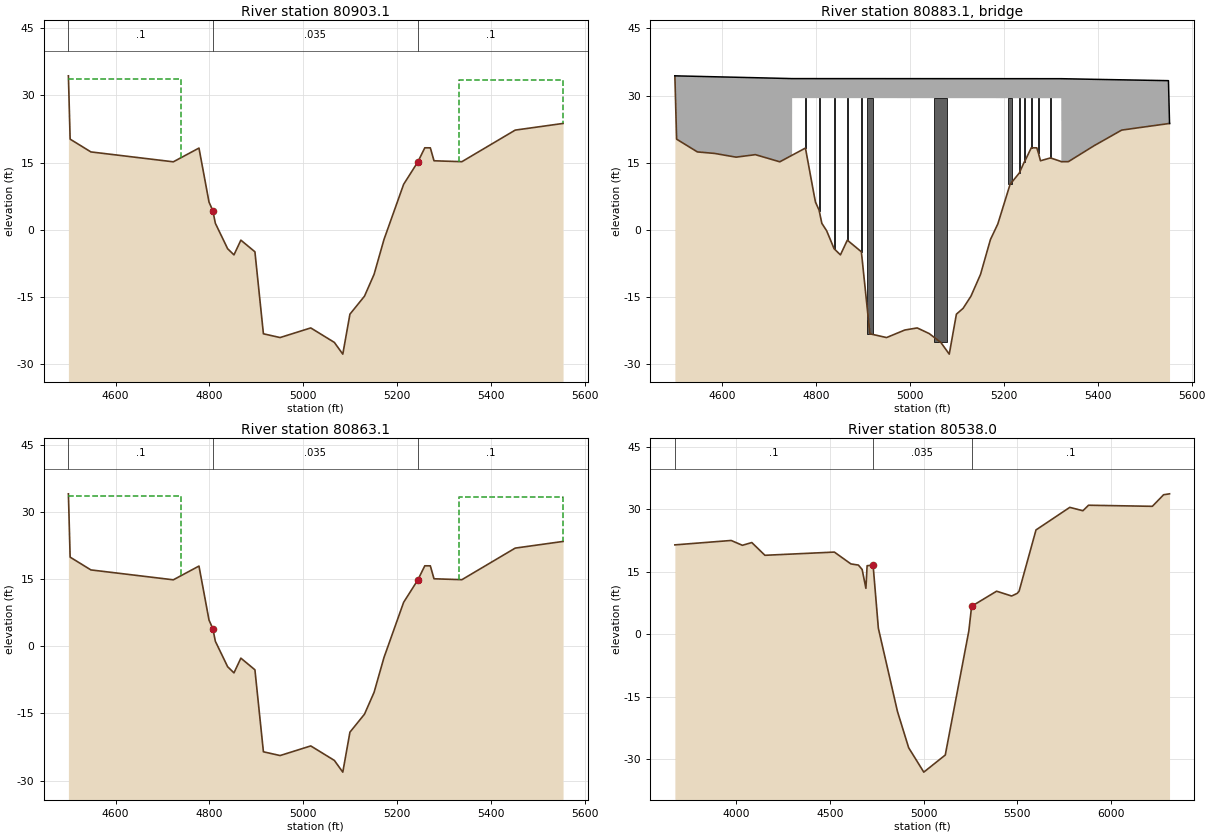
Type RM Length L Ch R = 1 ,80903.1 ,40,40,40
BEGIN DESCRIPTION:
Upstream Section of Bridge/Culvert/Weir
END DESCRIPTION:
XS GIS Cut Line= 5
      3144410.52      13838346.2      3144394.08     13838159.55
      3144348.37     13837528.19      3144354.08     13837426.78
      3144346.18     13837295.77
#Sta/Elev= 30
 4499.69   34.37  4503.4   20.25    4504   20.19  4547.6   17.38  4723.1   15.17
  4777.7   18.24  4799.1    6.17  4807.1    4.29  4812.6    1.44  4838.7   -4.23
  4852.2   -5.61  4866.9   -2.32  4896.8   -4.92  4914.9  -23.23  4950.4  -24.07
  5015.7  -21.92  5065.9  -25.15  5083.9  -27.77  5099.1  -18.85  5130.1  -14.83
  5150.5   -9.96  5171.6   -2.18  5213.4   10.14  5243.7   15.15  5258.5    18.3
  5270.3   18.29  5278.1    15.4  5337.5    15.2    5451   22.25  5552.9   23.74
#Mann= 3 ,-1 , 0
 4499.69      .1       0  4807.1    .035       0  5243.7      .1       0
#XS Ineff= 2 , 0
            4740    33.6    5332            33.4
Permanent Ineff=
       F       F
Bank Sta=4807.1,5243.7
XS Rating Curve= 0
Exp/Cntr=.5,.3

Type RM Length L Ch R = 3 ,80883.1 ,,,
BEGIN DESCRIPTION:
SOUTHERN PACIFIC RAILROAD
Structure ID: W00-3
END DESCRIPTION:
Bridge Culvert--1,0,-1,-1, 0
Deck Dist Width WeirC Skew NumUp NumDn MinLoCord MaxHiCord MaxSubmerge Is_Ogee
10,20,2.6,0, 18, 18, , , .95, 0, 1,1,,
 4499.69  4503.4    4504  4547.6  4584.4  4630.1    4671  4723.1 4749.31  4749.4
 5322.39  5322.5  5322.8  5337.5  5391.9    5451 5550.61  5552.9
   34.42   34.41   34.41    34.3   34.21    34.1      34   33.87    33.8    33.8
   33.78   33.78   33.78   33.75   33.64   33.53   33.34   23.79
   34.42    20.3   20.24   17.43   17.09   16.26   16.82   15.22   16.69   29.44
   29.42   15.25   15.24   15.25   18.79    22.3   23.76   23.79
 4499.69  4503.4    4504  4547.6  4584.4  4630.1    4671  4723.1 4749.31  4749.4
 5322.39  5322.5  5322.8  5337.5  5391.9    5451 5550.61  5552.9
   34.42   34.41   34.41    34.3   34.21    34.1      34   33.87    33.8    33.8
   33.78   33.78   33.78   33.75   33.64   33.53   33.34   23.79
   34.19   20.07   20.01    17.2   16.86   16.03   16.59   14.99   16.46   29.21
   29.19   15.02   15.01   15.02   18.56   22.07   23.53   23.56
Pier Skew, UpSta & Num, DnSta & Num=  ,4777.7, 2 ,4777.7, 2 , 0 , 0 , 0 ,,
     1.2     1.2
   16.95   30.44
     1.2     1.2
   16.72   30.21
Pier Skew, UpSta & Num, DnSta & Num=  ,4807.2, 2 ,4807.2, 2 , 0 , 0 , 0 ,,
       2       2
    2.68   30.44
       2       2
    2.45   30.21
Pier Skew, UpSta & Num, DnSta & Num=  ,4838.7, 2 ,4838.7, 2 , 0 , 0 , 0 ,,
       2       2
   -5.28   30.44
       2       2
   -5.51   30.21
Pier Skew, UpSta & Num, DnSta & Num=  ,4866.9, 2 ,4866.9, 2 , 0 , 0 , 0 ,,
       2       2
   -3.49   30.44
       2       2
   -3.72   30.21
Pier Skew, UpSta & Num, DnSta & Num=  ,4896.8, 2 ,4896.8, 2 , 0 , 0 , 0 ,,
       2       2
   -6.88   30.44
       2       2
   -7.11   30.21
Pier Skew, UpSta & Num, DnSta & Num=  ,4914.9, 2 ,4914.9, 2 , 0 , 0 , 0 ,,
      14      14
  -24.35   30.44
      14      14
  -24.58   30.21
Pier Skew, UpSta & Num, DnSta & Num=  ,5065.9, 2 ,5065.9, 2 , 0 , 0 , 0 ,,
    28.5    28.5
  -28.17   30.43
    28.5    28.5
   -28.4    30.2
Pier Skew, UpSta & Num, DnSta & Num=  ,5213.4, 2 ,5213.4, 2 , 0 , 0 , 0 ,,
       8       8
    7.84   30.42
       8       8
    7.61   30.19
Pier Skew, UpSta & Num, DnSta & Num=  ,5232.9, 2 ,5232.9, 2 , 0 , 0 , 0 ,,
     1.2     1.2
   11.62   30.42
     1.2     1.2
   11.39   30.19
Pier Skew, UpSta & Num, DnSta & Num=  ,5244.2, 2 ,5244.2, 2 , 0 , 0 , 0 ,,
     1.2     1.2
   14.18   30.42
     1.2     1.2
   13.95   30.19
Pier Skew, UpSta & Num, DnSta & Num=  ,5258.5, 2 ,5258.5, 2 , 0 , 0 , 0 ,,
     1.2     1.2
   17.22   30.42
     1.2     1.2
   16.99   30.19
Pier Skew, UpSta & Num, DnSta & Num=  ,5273.8, 2 ,5273.8, 2 , 0 , 0 , 0 ,,
     3.5     3.5
   15.46   30.42
     3.5     3.5
   15.23   30.19
Pier Skew, UpSta & Num, DnSta & Num=  ,5299.4, 2 ,5299.4, 2 , 0 , 0 , 0 ,,
     1.2     1.2
   15.07   30.42
     1.2     1.2
   14.84   30.19
Abutment Skew #Up #Dn= , 2 , 2
  4749.2  4799.2
   29.44     6.2
  4749.2  4799.2
   29.21    5.97
BR Coef= 1 , 1 , 0 ,1.25, 0 ,,,.8,0,2,0,
WSPro=,,,, 1 ,,,, 0 ,,,, 0 ,,,,-1 ,-1 ,-1 , 0 , 0 , 0 , 0 , 0
BR U #Sta/Elev= 70
 4499.69   34.42  4499.8      34 4499.91   33.58  4503.4    20.3    4504   20.24
  4547.6   17.43    4561   17.31  4584.4   17.09  4613.5   16.56  4630.1   16.26
  4666.9   16.76    4671   16.82  4723.1   15.22  4735.8   15.93  4738.8    16.1
  4749.2   16.69 4749.31   16.69  4749.4    16.7  4777.7   18.29  4796.3    7.72
  4799.1    6.22  4799.2     6.2  4807.1    4.34  4807.2    4.18  4812.6    1.49
  4822.9    -.18  4838.7   -4.18  4852.2   -5.56  4866.9   -2.27  4896.8   -4.87
  4912.3  -20.55  4914.9  -23.18  4950.4  -24.02  4974.2  -22.99  4989.2  -22.34
  5015.7  -21.87  5041.2  -23.13  5065.9   -25.1  5083.9  -27.72  5099.1   -18.8
  5113.4  -17.49  5130.1  -14.78  5150.5   -9.91  5171.6   -2.13  5184.2     .66
  5187.3    1.35  5213.4   10.19  5217.3   10.69  5232.9    12.7  5243.7    15.2
  5244.2   15.21  5258.5   18.35  5270.3   18.34  5273.8   17.15  5278.1   15.45
  5299.4   16.09  5319.9   15.37  5322.3   15.26 5322.39   15.26  5322.5   15.25
  5322.6   15.25  5322.8   15.24  5337.5   15.25  5391.9   18.79    5451    22.3
  5486.6   22.82 5550.39   23.75  5550.5   23.75 5550.61   23.76  5552.9   23.79
BR U #Mann= 3
 4499.69      .1  4807.1    .035  5243.7      .1
BR U Banks=4807.1,5243.7
BR D #Sta/Elev= 70
 4499.69   34.19  4499.8   33.77 4499.91   33.35  4503.4   20.07    4504   20.01
  4547.6    17.2    4561   17.08  4584.4   16.86  4613.5   16.33  4630.1   16.03
  4666.9   16.53    4671   16.59  4723.1   14.99  4735.8    15.7  4738.8   15.87
  4749.2   16.46 4749.31   16.46  4749.4   16.47  4777.7   18.06  4796.3    7.49
  4799.1    5.99  4799.2    5.97  4807.1    4.11  4807.2    3.95  4812.6    1.26
  4822.9    -.41  4838.7   -4.41  4852.2   -5.79  4866.9    -2.5  4896.8    -5.1
  4912.3  -20.78  4914.9  -23.41  4950.4  -24.25  4974.2  -23.22  4989.2  -22.57
  5015.7   -22.1  5041.2  -23.36  5065.9  -25.33  5083.9  -27.95  5099.1  -19.03
  5113.4  -17.72  5130.1  -15.01  5150.5  -10.14  5171.6   -2.36  5184.2     .43
  5187.3    1.12  5213.4    9.96  5217.3   10.46  5232.9   12.47  5243.7   14.97
  5244.2   14.98  5258.5   18.12  5270.3   18.11  5273.8   16.92  5278.1   15.22
  5299.4   15.86  5319.9   15.14  5322.3   15.03 5322.39   15.03  5322.5   15.02
  5322.6   15.02  5322.8   15.01  5337.5   15.02  5391.9   18.56    5451   22.07
  5486.6   22.59 5550.39   23.52  5550.5   23.52 5550.61   23.53  5552.9   23.56
BR D #Mann= 3
 4499.69      .1  4807.1    .035  5243.7      .1
BR D Banks=4807.1,5243.7
BC Design=,, 0 ,, 0 ,,,,,,
BC HTab HWMax=34.37

Type RM Length L Ch R = 1 ,80863.1 ,325.1,325.1,325.1
BEGIN DESCRIPTION:
Downstream Section of Bridge/Culvert/Weir
END DESCRIPTION:
XS GIS Cut Line= 5
      3144448.94     13838357.34       3144432.5     13838170.69
      3144386.79     13837539.33       3144392.5     13837437.92
       3144384.6      13837306.9
#Sta/Elev= 30
 4499.69   34.04  4503.4   19.92    4504   19.86  4547.6   17.05  4723.1   14.84
  4777.7   17.91  4799.1    5.84  4807.1    3.96  4812.6    1.11  4838.7   -4.56
  4852.2   -5.94  4866.9   -2.65  4896.8   -5.25  4914.9  -23.56  4950.4   -24.4
  5015.7  -22.25  5065.9  -25.48  5083.9   -28.1  5099.1  -19.18  5130.1  -15.16
  5150.5  -10.29  5171.6   -2.51  5213.4    9.81  5243.7   14.82  5258.5   17.97
  5270.3   17.96  5278.1   15.07  5337.5   14.87    5451   21.92  5552.9   23.41
#Mann= 3 ,-1 , 0
 4499.69      .1       0  4807.1    .035       0  5243.7      .1       0
#XS Ineff= 2 , 0
            4740    33.6    5332            33.4
Permanent Ineff=
       F       F
Bank Sta=4807.1,5243.7
XS Rating Curve= 0
Exp/Cntr=.5,.3

Type RM Length L Ch R = 1 ,80538.0 ,0,0,0
BEGIN DESCRIPTION:
Cross Section 80538.0
Located At: SER186
END DESCRIPTION:
XS GIS Cut Line= 4
      3144629.43     13839256.32      3144617.56     13838348.34
      3144789.66     13837683.68       3144469.2     13836692.62
#Sta/Elev= 30
  3674.4   21.45  3974.4   22.51  4034.4   21.35  4084.4   22.01  4154.4   18.95
  4524.4   19.72  4612.5   16.88  4652.5    16.6  4672.5   15.54  4692.5   11.02
  4698.9   16.45  4730.8   16.58  4758.9    1.42  4860.6  -18.54  4920.4  -27.27
    5001  -33.12  5115.5  -29.01  5241.1     .81  5255.8     6.7    5389   10.33
    5469    9.17    5499    9.81    5509   10.35    5599   25.04    5779   30.46
    5849   29.65    5879   30.97    6219   30.71    6279   33.49  6310.6   33.71
#Mann= 3 ,-1 , 0
  3674.4      .1       0  4730.8    .035       0  5255.8      .1       0
Bank Sta=4730.8,5255.8
XS Rating Curve= 0
Exp/Cntr=.3,.1

Chan Stop Cuts=-1